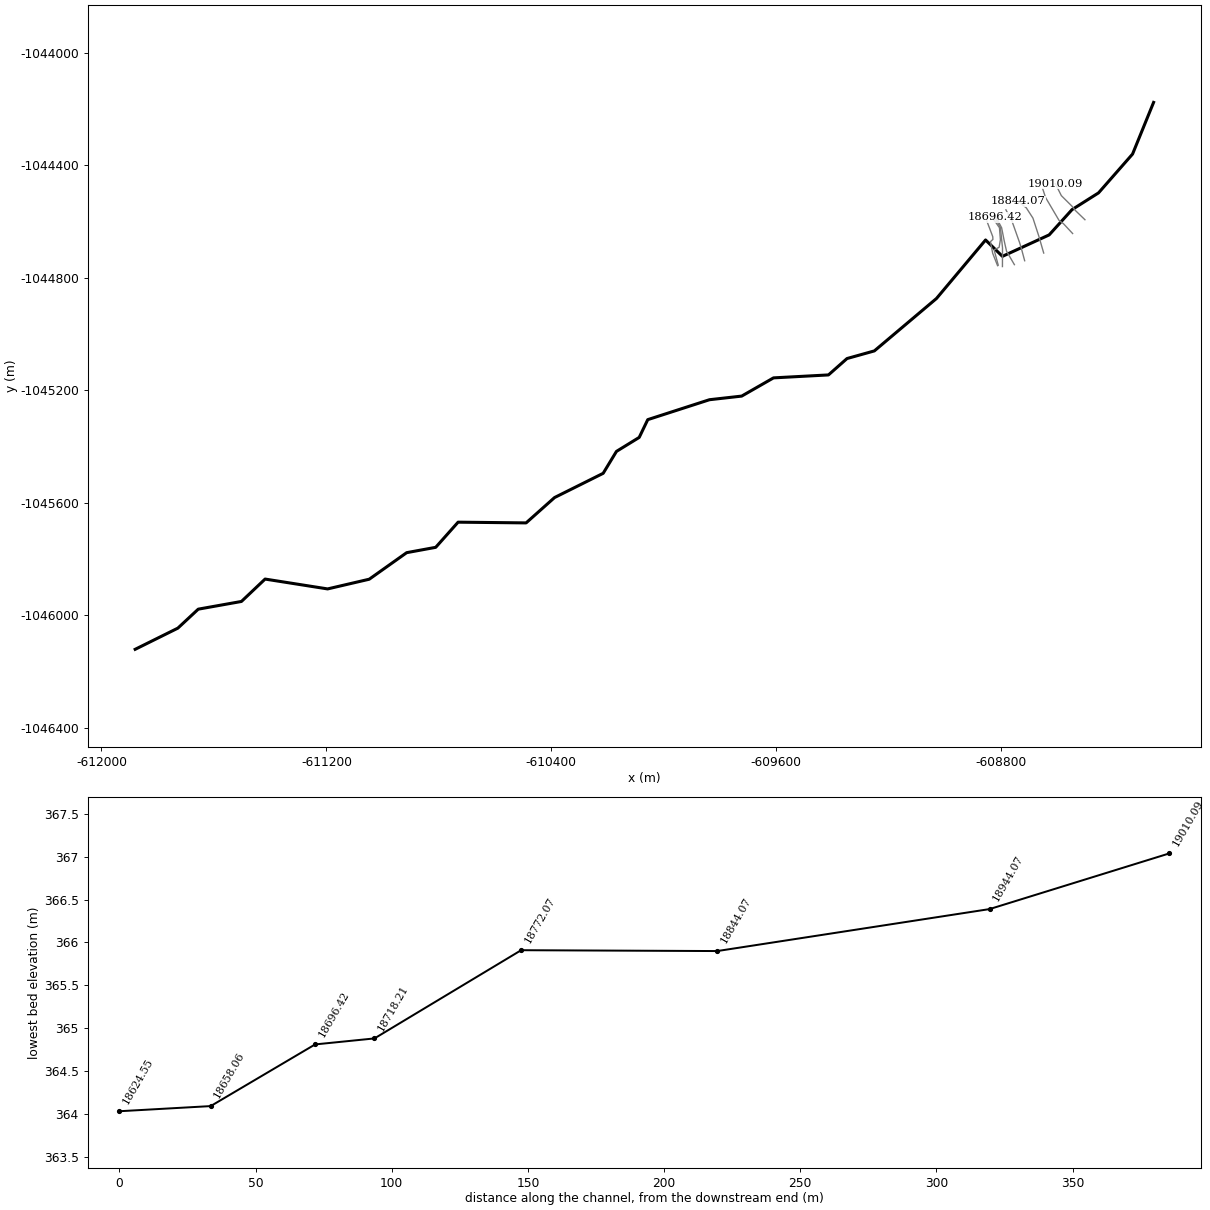
--- PPO_Kvasiny_efektiv.prj (project) ---

Proj Title=PPO_Kvasiny_efektivita
Current Plan=p14
Default Exp/Contr=0.3,0.1
SI Units
Geom File=g06
Geom File=g07
Geom File=g08
Geom File=g09
Geom File=g10
Geom File=g04
Geom File=g05
Geom File=g01
Geom File=g02
Geom File=g11
Geom File=g12
Geom File=g13
Geom File=g14
Geom File=g15
Flow File=f03
Flow File=f01
Flow File=f02
Flow File=f04
Flow File=f05
Flow File=f06
Unsteady File=u01
Unsteady File=u02
Unsteady File=u03
Unsteady File=u05
Plan File=p06
Plan File=p01
Plan File=p02
Plan File=p03
Plan File=p04
Plan File=p09
Plan File=p10
Plan File=p05
Plan File=p08
Plan File=p07
Plan File=p12
Plan File=p11
Plan File=p13
Plan File=p14
Y Axis Title=Elevation
X Axis Title(PF)=Main Channel Distance
X Axis Title(XS)=Station
BEGIN DESCRIPTION:
END DESCRIPTION:
DSS File=..\__VELKA_VODA\2879_PPO_Kvasiny\HEC_RAS_akt\PPO_Kvasiny_po_UR.dss
DSS Export Rating Curves= 0
DSS Export Rating Curve Sorted= 0
DSS Export Volume Flow Curves= 0
DXF Filename=..\__VELKA_VODA\2879_PPO_Kvasiny\HEC_RAS\Kvasiny_DUR.
DXF OffsetX= 0
DXF OffsetY= 0
DXF ScaleX= 1
DXF ScaleY= 10

--- PPO_Kvasiny_efektiv.p14 (plan) ---

Plan Title=N-Q20_bez_SO02
Program Version=5.03
Short Identifier=N-Q20_bez_SO02
Geom File=g15
Flow File=f04
Mixed Flow
K Sum by GR= 0
Std Step Tol= 0.001
Critical Tol= 0.001
Num of Std Step Trials= 20
Max Error Tol= 0.1
Flow Tol Ratio= 0.001
Split Flow NTrial= 30
Split Flow Tol= 0.006
Split Flow Ratio= 0.02
Log Output Level= 0
Friction Slope Method= 1
Unsteady Friction Slope Method= 2
Unsteady Bridges Friction Slope Method= 1
Parabolic Critical Depth
Global Vel Dist= 2 , 3 , 2
Global Log Level= 0
CheckData=True
Encroach Param=-1 ,0,0, 0
Computation Interval=1MIN
Output Interval=1HOUR
Instantaneous Interval=1HOUR
Mapping Interval=1HOUR
Run HTab= 0
Run UNet= 0
Run Sediment= 0
Run PostProcess= 0
Run WQNet= 0
Run RASMapper=-1
UNET Theta= 1
UNET Theta Warmup= 1
UNET ZTol= 0.006
UNET ZSATol= 0.006
UNET MxIter= 20
UNET Max Iter WO Improvement= 0
UNET MaxInSteps= 0
UNET DtIC= 0
UNET DtMin= 0
UNET MaxCRTS= 20
UNET WFStab= 2
UNET SFStab= 1
UNET WFX= 1
UNET SFX= 1
UNET DSS MLevel= 4
UNET Pardiso=0
UNET DZMax Abort= 30
UNET Use Existing IB Tables=-1
UNET Froude Reduction=False
UNET Froude Limit= 0.8
UNET Froude Power= 4
UNET Time Slicing=0,0, 5
UNET D1 Cores= 0
UNET D2 Coriolis=0
UNET D2 Cores= 0
UNET D2 Theta= 1
UNET D2 Theta Warmup= 1
UNET D2 Z Tol= 0.003
UNET D2 Volume Tol= 0.003
UNET D2 Max Iterations= 20
UNET D2 Equation= 0
UNET D2 RampUpFraction=0.1
UNET D2 TimeSlices= 1
UNET D2 BCVolumeCheck=0
UNET D1D2 MaxIter= 0
UNET D1D2 ZTol=0.003
UNET D1D2 QTol=0.1
UNET D1D2 MinQTol=0.03
Write IC File= 0
Write IC File at Fixed DateTime=0
Write IC File at Sim End=0
Echo Input=False
Echo Parameters=False
Echo Output=False
Write Detailed= 0
HDF Write Warmup=0
HDF Write Time Slices=0
HDF Flush=0
HDF Face Node Velocities=0
HDF Compression= 1
HDF Chunk Size= 1
HDF Spatial Parts= 1
HDF Use Max Rows=0
HDF Fixed Rows= 1
Calibration Method= 0
Calibration Iterations= 20
Calibration Max Change=0.05
Calibration Tolerance=0.2
Calibration Maximum=1.5
Calibration Minimum=0.5
Calibration Optimization Method= 1
WQ AD Non Conservative
WQ ULTIMATE=-1
WQ Max Comp Step=1HOUR
WQ Output Interval=15MIN
WQ Output Selected Increments= 0
WQ Output face flow=0
WQ Output face velocity=0
WQ Output face area=0
WQ Output face dispersion=0
WQ Output cell volume=0
WQ Output cell surface area=0
WQ Output cell continuity=0
WQ Output cumulative cell continuity=0
WQ Output face conc=0
WQ Output face dconc_dx=0
WQ Output face courant=0
WQ Output face peclet=0
WQ Output face adv mass=0
WQ Output face disp mass=0
WQ Output cell mass=0
WQ Output cell source sink temp=0
WQ Output nsm pathways=0
WQ Output nsm derived pathways=0
WQ Output MaxMinRange=-1
WQ Daily Max Min Mean=-1
WQ Daily Range=0
WQ Daily Time=0
WQ Create Restart=0
WQ Fixed Restart=0
WQ System Summary=0
WQ Write To DSS=0
WQ Use Fixed Temperature=0
Sorting and Armoring Iterations= 10
XS Update Threshold= 0.02
Bed Roughness Predictor= 0
Hydraulics Update Threshold= 0.02
Energy Slope Method= 1
Volume Change Method= 1
Sediment Retention Method= 0
XS Weighting Method= 0
Number of US Weighted Cross Sections= 1
Number of DS Weighted Cross Sections= 1
Upstream XS Weight=0
Main XS Weight=1
Downstream XS Weight=0
Number of DS XS's Weighted with US Boundary= 1
Upstream Boundary Weight= 1
Weight of XSs Associated with US Boundary= 0
Number of US XS's Weighted with DS Boundary= 1
Downstream Boundary Weight= 0.5
Weight of XSs Associated with DS Boundary= 0.5
Percentile Method= 0
Sediment Output Level= 4
Mass or Volume Output= 0
Output Increment Type= 1
Profile and TS Output Increment= 1
XS Output Flag= 0
XS Output Increment= 10
Write Gradation File= 0
Read Gradation Hotstart= 0
Write HDF5 File= 1
Write DSS Sediment File= 0
SV Curve= 0
Specific Gage Flag= 0

--- PPO_Kvasiny_efektiv.p01 (plan) ---

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Plan Title=S-Q10
Short Identifier=S-Q10
Geom File=g07
Flow File=f02
Std Step Tol= 0.0003
Critical Tol= 0.0003
Num of Std Step Trials= 40
Flow Tol Ratio= 0.0001
Split Flow NTrial= 60
Split Flow Tol= 0.001
Split Flow Ratio= 0.0002
Calc Critical at every XS
Secant Critical Depth
Computation Interval=1HOUR
UNET ZSATol= 0.015
UNET Froude Limit= 1
UNET Froude Power= 10
DSS File=dss
Volume Change Method= 0
Upstream XS Weight=0.25
Main XS Weight=0.5
Downstream XS Weight=0.25
Profile and TS Output Increment= 10

--- PPO_Kvasiny_efektiv.p02 (plan) ---

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Plan Title=S-Q20
Short Identifier=S-Q20
Geom File=g08
Flow File=f04
Std Step Tol= 0.0003
Critical Tol= 0.0003
Num of Std Step Trials= 40
Flow Tol Ratio= 0.0001
Split Flow NTrial= 60
Split Flow Tol= 0.001
Split Flow Ratio= 0.0002
Calc Critical at every XS
Secant Critical Depth
Global Vel Dist= 1 , 3 , 1
Computation Interval=1HOUR
UNET ZSATol= 0.015
UNET Froude Limit= 1
UNET Froude Power= 10
DSS File=dss
Volume Change Method= 0
Upstream XS Weight=0.25
Main XS Weight=0.5
Downstream XS Weight=0.25
Profile and TS Output Increment= 10

--- PPO_Kvasiny_efektiv.p03 (plan) ---

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Plan Title=S-Q50
Short Identifier=S-Q50
Geom File=g09
Flow File=f05
Num of Std Step Trials= 40
Split Flow NTrial= 60
Split Flow Tol= 0.001
Split Flow Ratio= 0.002
Calc Critical at every XS
Secant Critical Depth
Computation Interval=1HOUR
UNET ZSATol= 0.015
UNET Froude Limit= 1
UNET Froude Power= 10
DSS File=dss
Volume Change Method= 0
Upstream XS Weight=0.25
Main XS Weight=0.5
Downstream XS Weight=0.25
Profile and TS Output Increment= 10

--- PPO_Kvasiny_efektiv.p04 (plan) ---

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Plan Title=S-Q100
Short Identifier=S-Q100
Geom File=g10
Flow File=f06
Num of Std Step Trials= 40
Split Flow NTrial= 60
Split Flow Tol= 0.001
Split Flow Ratio= 0.002
Calc Critical at every XS
Secant Critical Depth
Computation Interval=1HOUR
UNET ZSATol= 0.015
UNET Froude Limit= 1
UNET Froude Power= 10
DSS File=dss
Volume Change Method= 0
Upstream XS Weight=0.25
Main XS Weight=0.5
Downstream XS Weight=0.25
Profile and TS Output Increment= 10

--- PPO_Kvasiny_efektiv.p05 (plan) ---

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Plan Title=N-Q5
Short Identifier=N-Q5
Geom File=g01
Flow File=f01
Calc Critical at every XS

--- PPO_Kvasiny_efektiv.p06 (plan) ---

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Plan Title=S-Q5
Short Identifier=S-Q5
Geom File=g06
Flow File=f01
Std Step Tol= 0.0003
Critical Tol= 0.0003
Num of Std Step Trials= 40
Flow Tol Ratio= 0.0001
Split Flow NTrial= 60
Split Flow Tol= 0.001
Split Flow Ratio= 0.0002
Calc Critical at every XS
Secant Critical Depth
Computation Interval=1HOUR
UNET ZSATol= 0.015
UNET Froude Limit= 1
UNET Froude Power= 10
DSS File=dss
Volume Change Method= 0
Upstream XS Weight=0.25
Main XS Weight=0.5
Downstream XS Weight=0.25
Profile and TS Output Increment= 10

--- PPO_Kvasiny_efektiv.p07 (plan) ---

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Plan Title=N-Q20
Short Identifier=N-Q20
Geom File=g11
Flow File=f04
Calc Critical at every XS
Secant Critical Depth
DSS File=dss

--- PPO_Kvasiny_efektiv.p08 (plan) ---

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Plan Title=N-Q10
Short Identifier=N-Q10
Geom File=g02
Flow File=f02

--- PPO_Kvasiny_efektiv.p09 (plan) ---

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Plan Title=A1
Short Identifier=A1
Simulation Date=29JUN2017,0000,29JUN2017,0200
Geom File=g04
Flow File=u02
Subcritical Flow
Std Step Tol= 0.003
Critical Tol= 0.003
Global Vel Dist= 0 , 0 , 0
Computation Interval=5SEC
Output Interval=1MIN
Instantaneous Interval=5MIN
Mapping Interval=4MIN
Run HTab= 1
Run UNet= 1
Run PostProcess= 1
Run RASMapper= 0
UNET Froude Reduction=True
DSS File=dss
Stage Flow Hydrograph=Bela            ,Bela_reach      ,19010.09
Stage Flow Hydrograph=Bela            ,Bela_reach      ,18944.07
Stage Flow Hydrograph=Bela            ,Bela_reach      ,18844.07
Stage Flow Hydrograph=Bela            ,Bela_reach      ,18772.07
Stage Flow Hydrograph=Bela            ,Bela_reach      ,18718.21
Stage Flow Hydrograph=Bela            ,Bela_reach      ,18696.42
Stage Flow Hydrograph=Bela            ,Bela_reach      ,18658.06
Stage Flow Hydrograph=Bela            ,Bela_reach      ,18624.55
Stage Flow Hydrograph=Bela            ,Bela_reach      ,18586.06
Stage Flow Hydrograph=Bela            ,Bela_reach      ,18579.06
Stage Flow Hydrograph=Bela            ,Bela_reach      ,18566.06
Stage Flow Hydrograph=Bela            ,Bela_reach      ,18533.27
Stage Flow Hydrograph=Bela            ,Bela_reach      ,18520.9
Stage Flow Hydrograph=Bela            ,Bela_reach      ,18498.6
Stage Flow Hydrograph=Bela            ,Bela_reach      ,18495.51
Stage Flow Hydrograph=Bela            ,Bela_reach      ,18470.63
Stage Flow Hydrograph=Bela            ,Bela_reach      ,18465.26
Stage Flow Hydrograph=Bela            ,Bela_reach      ,18447.77
Stage Flow Hydrograph=Bela            ,Bela_reach      ,18431.84
Stage Flow Hydrograph=Bela            ,Bela_reach      ,18416.83
Stage Flow Hydrograph=Bela            ,Bela_reach      ,18397.53
Stage Flow Hydrograph=Bela            ,Bela_reach      ,18390.36
Stage Flow Hydrograph=Bela            ,Bela_reach      ,18374.77
Stage Flow Hydrograph=Bela            ,Bela_reach      ,18361.61
Stage Flow Hydrograph=Bela            ,Bela_reach      ,18350.04
Stage Flow Hydrograph=Bela            ,Bela_reach      ,18348.04
Stage Flow Hydrograph=Bela            ,Bela_reach      ,18341.17
Stage Flow Hydrograph=Bela            ,Bela_reach      ,18337.36
Stage Flow Hydrograph=Bela            ,Bela_reach      ,18322.93
Stage Flow Hydrograph=Bela            ,Bela_reach      ,18306.53
Stage Flow Hydrograph=Bela            ,Bela_reach      ,18294.98
Stage Flow Hydrograph=Bela            ,Bela_reach      ,18279.06
Stage Flow Hydrograph=Bela            ,Bela_reach      ,18273.75
Stage Flow Hydrograph=Bela            ,Bela_reach      ,18264.04
Stage Flow Hydrograph=Bela            ,Bela_reach      ,18251.33
Stage Flow Hydrograph=Bela            ,Bela_reach      ,18239.54
Stage Flow Hydrograph=Bela            ,Bela_reach      ,18224.5
Stage Flow Hydrograph=Bela            ,Bela_reach      ,18206.04
Stage Flow Hydrograph=Bela            ,Bela_reach      ,18201.06
Stage Flow Hydrograph=Bela            ,Bela_reach      ,18178.04
Stage Flow Hydrograph=Bela            ,Bela_reach      ,18144.81
Stage Flow Hydrograph=Bela            ,Bela_reach      ,18087.28
Stage Flow Hydrograph=Bela            ,Bela_reach      ,18070.04
Stage Flow Hydrograph=Bela            ,Bela_reach      ,18044.69
Stage Flow Hydrograph=Bela            ,Bela_reach      ,18006.85
Stage Flow Hydrograph=Bela            ,Bela_reach      ,17958.03
Stage Flow Hydrograph=Bela            ,Bela_reach      ,17953.06
Stage Flow Hydrograph=Bela            ,Bela_reach      ,17934.03
Stage Flow Hydrograph=Bela            ,Bela_reach      ,17859.59
Stage Flow Hydrograph=Bela            ,Bela_reach      ,17857.16
Stage Flow Hydrograph=Bela            ,Bela_reach      ,17840.02
Stage Flow Hydrograph=Bela            ,Bela_reach      ,17782.89
Stage Flow Hydrograph=Bela            ,Bela_reach      ,17720.02
Stage Flow Hydrograph=Bela            ,Bela_reach      ,17714.08
Stage Flow Hydrograph=Bela            ,Bela_reach      ,17692.02
Stage Flow Hydrograph=Bela            ,Bela_reach      ,17647.97
Stage Flow Hydrograph=Bela            ,Bela_reach      ,17602.02
Stage Flow Hydrograph=Bela            ,Bela_reach      ,17556.69
Stage Flow Hydrograph=Bela            ,Bela_reach      ,17514.01
Stage Flow Hydrograph=Bela            ,Bela_reach      ,17511.2
Stage Flow Hydrograph=Bela            ,Bela_reach      ,17500.01
Stage Flow Hydrograph=Bela            ,Bela_reach      ,17440.04
Stage Flow Hydrograph=Bela            ,Bela_reach      ,17378
Stage Flow Hydrograph=Bela            ,Bela_reach      ,17375.01
Stage Flow Hydrograph=Bela            ,Bela_reach      ,17366
Stage Flow Hydrograph=Bela            ,Bela_reach      ,17340.65
Stage Flow Hydrograph=Bela            ,Bela_reach      ,17318.97
Stage Flow Hydrograph=Bela            ,Bela_reach      ,17291.99
Stage Flow Hydrograph=Bela            ,Bela_reach      ,17259.19
Stage Flow Hydrograph=Bela            ,Bela_reach      ,17233.92
Stage Flow Hydrograph=Bela            ,Bela_reach      ,17217.4
Stage Flow Hydrograph=Bela            ,Bela_reach      ,17199.2
Stage Flow Hydrograph=Bela            ,Bela_reach      ,17182.49
Stage Flow Hydrograph=Bela            ,Bela_reach      ,17160.8
Stage Flow Hydrograph=Bela            ,Bela_reach      ,17145.99
Stage Flow Hydrograph=Bela            ,Bela_reach      ,17113.28
Stage Flow Hydrograph=Bela            ,Bela_reach      ,17089.04
Stage Flow Hydrograph=Bela            ,Bela_reach      ,17072.46
Stage Flow Hydrograph=Bela            ,Bela_reach      ,17059.68
Stage Flow Hydrograph=Bela            ,Bela_reach      ,17042.5
Stage Flow Hydrograph=Bela            ,Bela_reach      ,17022.69
Stage Flow Hydrograph=Bela            ,Bela_reach      ,16998.19
Stage Flow Hydrograph=Bela            ,Bela_reach      ,16987.28
Stage Flow Hydrograph=Bela            ,Bela_reach      ,16981.23
Stage Flow Hydrograph=Bela            ,Bela_reach      ,16972.87
Stage Flow Hydrograph=Bela            ,Bela_reach      ,16965.79
Stage Flow Hydrograph=Bela            ,Bela_reach      ,16958.19
Stage Flow Hydrograph=Bela            ,Bela_reach      ,16953.35
Stage Flow Hydrograph=Bela            ,Bela_reach      ,16947.94
Stage Flow Hydrograph=Bela            ,Bela_reach      ,16933.84
Stage Flow Hydrograph=Bela            ,Bela_reach      ,16908.96
Stage Flow Hydrograph=Bela            ,Bela_reach      ,16890.01
Stage Flow Hydrograph=Bela            ,Bela_reach      ,16865
Stage Flow Hydrograph=Bela            ,Bela_reach      ,16839.98
Stage Flow Hydrograph=Bela            ,Bela_reach      ,16821.12
Stage Flow Hydrograph=Bela            ,Bela_reach      ,16779.33
Stage Flow Hydrograph=Bela            ,Bela_reach      ,16751.94
Stage Flow Hydrograph=Bela            ,Bela_reach      ,16730.52
Stage Flow Hydrograph=Bela            ,Bela_reach      ,16725.7
Stage Flow Hydrograph=Bela            ,Bela_reach      ,16711.55
Stage Flow Hydrograph=Bela            ,Bela_reach      ,16685.61
Stage Flow Hydrograph=Bela            ,Bela_reach      ,16667.18
Stage Flow Hydrograph=Bela            ,Bela_reach      ,16661.4
Stage Flow Hydrograph=Bela            ,Bela_reach      ,16654.54
Stage Flow Hydrograph=Bela            ,Bela_reach      ,16647.88
Stage Flow Hydrograph=Bela            ,Bela_reach      ,16641.56
Stage Flow Hydrograph=Bela            ,Bela_reach      ,16625.96
Stage Flow Hydrograph=Bela            ,Bela_reach      ,16605.36
Stage Flow Hydrograph=Bela            ,Bela_reach      ,16585.06
Stage Flow Hydrograph=Bela            ,Bela_reach      ,16568.98
Stage Flow Hydrograph=Bela            ,Bela_reach      ,16555.88
Stage Flow Hydrograph=Bela            ,Bela_reach      ,16534.61
Stage Flow Hydrograph=Bela            ,Bela_reach      ,16530.05
Stage Flow Hydrograph=Bela            ,Bela_reach      ,16526.03
Stage Flow Hydrograph=Bela            ,Bela_reach      ,16521.83
Stage Flow Hydrograph=Bela            ,Bela_reach      ,16518.81
Stage Flow Hydrograph=Bela            ,Bela_reach      ,16515.82
Stage Flow Hydrograph=Bela            ,Bela_reach      ,16512.96
Stage Flow Hydrograph=Bela            ,Bela_reach      ,16510
Stage Flow Hydrograph=Bela            ,Bela_reach      ,16506.91
Stage Flow Hydrograph=Bela            ,Bela_reach      ,16496.64
Stage Flow Hydrograph=Bela            ,Bela_reach      ,16484.82
Stage Flow Hydrograph=Bela            ,Bela_reach      ,16457.95
Stage Flow Hydrograph=Bela            ,Bela_reach      ,16428.81
Stage Flow Hydrograph=Bela            ,Bela_reach      ,16401.95
Stage Flow Hydrograph=Bela            ,Bela_reach      ,16400.07
Stage Flow Hydrograph=Bela            ,Bela_reach      ,16391.95
Stage Flow Hydrograph=Bela            ,Bela_reach      ,16373.55
Stage Flow Hydrograph=Bela            ,Bela_reach      ,16338.53
Stage Flow Hydrograph=Bela            ,Bela_reach      ,16313.36
Stage Flow Hydrograph=Bela            ,Bela_reach      ,16285.94
Stage Flow Hydrograph=Bela            ,Bela_reach      ,16264.13
Stage Flow Hydrograph=Bela            ,Bela_reach      ,16241.06
Stage Flow Hydrograph=Bela            ,Bela_reach      ,16217.94
Stage Flow Hydrograph=Bela            ,Bela_reach      ,16203.55
Stage Flow Hydrograph=Bela            ,Bela_reach      ,16186.97
Stage Flow Hydrograph=Bela            ,Bela_reach      ,16165.19
Stage Flow Hydrograph=Bela            ,Bela_reach      ,16140.98
Stage Flow Hydrograph=Bela            ,Bela_reach      ,16119.07
Stage Flow Hydrograph=Bela            ,Bela_reach      ,16106.59
Stage Flow Hydrograph=Bela            ,Bela_reach      ,16074.51
Stage Flow Hydrograph=Bela            ,Bela_reach      ,16056.34
Stage Flow Hydrograph=Bela            ,Bela_reach      ,16030.82
Stage Flow Hydrograph=Bela            ,Bela_reach      ,16007.74
Stage Flow Hydrograph=Bela            ,Bela_reach      ,16000.73
Stage Flow Hydrograph=Bela            ,Bela_reach      ,15989.93
Stage Flow Hydrograph=Bela            ,Bela_reach      ,15967.45
Stage Flow Hydrograph=Bela            ,Bela_reach      ,15957.93
Stage Flow Hydrograph=Bela            ,Bela_reach      ,15943.28
Stage Flow Hydrograph=Bela            ,Bela_reach      ,15934.58
Stage Flow Hydrograph=Bela            ,Bela_reach      ,15928.39
Stage Flow Hydrograph=Bela            ,Bela_reach      ,15916.88
Stage Flow Hydrograph=Bela            ,Bela_reach      ,15887.99
Stage Flow Hydrograph=Bela            ,Bela_reach      ,15868.15
Stage Flow Hydrograph=Bela            ,Bela_reach      ,15856.69
Stage Flow Hydrograph=Bela            ,Bela_reach      ,15829.9
Stage Flow Hydrograph=Bela            ,Bela_reach      ,15810.7
Stage Flow Hydrograph=Bela            ,Bela_reach      ,15786.92
Stage Flow Hydrograph=Bela            ,Bela_reach      ,15766.56
Stage Flow Hydrograph=Bela            ,Bela_reach      ,15754.75
Stage Flow Hydrograph=Bela            ,Bela_reach      ,15743.46
Stage Flow Hydrograph=Bela            ,Bela_reach      ,15729.91
Stage Flow Hydrograph=Bela            ,Bela_reach      ,15707.91
Stage Flow Hydrograph=Bela            ,Bela_reach      ,15704.01
Stage Flow Hydrograph=Bela            ,Bela_reach      ,15698.34
Stage Flow Hydrograph=Bela            ,Bela_reach      ,15681.9
Stage Flow Hydrograph=Bela            ,Bela_reach      ,15631.9
Stage Flow Hydrograph=Bela            ,Bela_reach      ,15561.9
Stage Flow Hydrograph=Bela            ,Bela_reach      ,15497.89
Stage Flow Hydrograph=Bela            ,Bela_reach      ,15429.05
Stage Flow Hydrograph=Bela            ,Bela_reach      ,15373.89

--- PPO_Kvasiny_efektiv.p10 (plan) ---

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Plan Title=A2
Short Identifier=A2
Simulation Date=29JUN2017,0000,29JUN2017,0200
Geom File=g05
Flow File=u03
Subcritical Flow
Std Step Tol= 0.003
Critical Tol= 0.003
Global Vel Dist= 0 , 0 , 0
Computation Interval=3SEC
Output Interval=1MIN
Instantaneous Interval=5MIN
Mapping Interval=4MIN
Run HTab= 1
Run UNet= 1
Run PostProcess= 1
Run RASMapper= 1
UNET Froude Reduction=True
DSS File=dss
Stage Flow Hydrograph=Bela            ,Bela_reach      ,19010.09
Stage Flow Hydrograph=Bela            ,Bela_reach      ,18944.07
Stage Flow Hydrograph=Bela            ,Bela_reach      ,18844.07
Stage Flow Hydrograph=Bela            ,Bela_reach      ,18772.07
Stage Flow Hydrograph=Bela            ,Bela_reach      ,18718.21
Stage Flow Hydrograph=Bela            ,Bela_reach      ,18696.42
Stage Flow Hydrograph=Bela            ,Bela_reach      ,18658.06
Stage Flow Hydrograph=Bela            ,Bela_reach      ,18624.55
Stage Flow Hydrograph=Bela            ,Bela_reach      ,18586.06
Stage Flow Hydrograph=Bela            ,Bela_reach      ,18579.06
Stage Flow Hydrograph=Bela            ,Bela_reach      ,18566.06
Stage Flow Hydrograph=Bela            ,Bela_reach      ,18533.27
Stage Flow Hydrograph=Bela            ,Bela_reach      ,18520.9
Stage Flow Hydrograph=Bela            ,Bela_reach      ,18498.6
Stage Flow Hydrograph=Bela            ,Bela_reach      ,18495.51
Stage Flow Hydrograph=Bela            ,Bela_reach      ,18470.63
Stage Flow Hydrograph=Bela            ,Bela_reach      ,18465.26
Stage Flow Hydrograph=Bela            ,Bela_reach      ,18447.77
Stage Flow Hydrograph=Bela            ,Bela_reach      ,18431.84
Stage Flow Hydrograph=Bela            ,Bela_reach      ,18416.83
Stage Flow Hydrograph=Bela            ,Bela_reach      ,18397.53
Stage Flow Hydrograph=Bela            ,Bela_reach      ,18390.36
Stage Flow Hydrograph=Bela            ,Bela_reach      ,18374.77
Stage Flow Hydrograph=Bela            ,Bela_reach      ,18361.61
Stage Flow Hydrograph=Bela            ,Bela_reach      ,18350.04
Stage Flow Hydrograph=Bela            ,Bela_reach      ,18348.04
Stage Flow Hydrograph=Bela            ,Bela_reach      ,18341.17
Stage Flow Hydrograph=Bela            ,Bela_reach      ,18337.36
Stage Flow Hydrograph=Bela            ,Bela_reach      ,18322.93
Stage Flow Hydrograph=Bela            ,Bela_reach      ,18306.53
Stage Flow Hydrograph=Bela            ,Bela_reach      ,18294.98
Stage Flow Hydrograph=Bela            ,Bela_reach      ,18279.06
Stage Flow Hydrograph=Bela            ,Bela_reach      ,18273.75
Stage Flow Hydrograph=Bela            ,Bela_reach      ,18264.04
Stage Flow Hydrograph=Bela            ,Bela_reach      ,18251.33
Stage Flow Hydrograph=Bela            ,Bela_reach      ,18239.54
Stage Flow Hydrograph=Bela            ,Bela_reach      ,18224.5
Stage Flow Hydrograph=Bela            ,Bela_reach      ,18206.04
Stage Flow Hydrograph=Bela            ,Bela_reach      ,18201.06
Stage Flow Hydrograph=Bela            ,Bela_reach      ,18178.04
Stage Flow Hydrograph=Bela            ,Bela_reach      ,18144.81
Stage Flow Hydrograph=Bela            ,Bela_reach      ,18087.28
Stage Flow Hydrograph=Bela            ,Bela_reach      ,18070.04
Stage Flow Hydrograph=Bela            ,Bela_reach      ,18044.69
Stage Flow Hydrograph=Bela            ,Bela_reach      ,18006.85
Stage Flow Hydrograph=Bela            ,Bela_reach      ,17958.03
Stage Flow Hydrograph=Bela            ,Bela_reach      ,17953.06
Stage Flow Hydrograph=Bela            ,Bela_reach      ,17934.03
Stage Flow Hydrograph=Bela            ,Bela_reach      ,17859.59
Stage Flow Hydrograph=Bela            ,Bela_reach      ,17857.16
Stage Flow Hydrograph=Bela            ,Bela_reach      ,17840.02
Stage Flow Hydrograph=Bela            ,Bela_reach      ,17782.89
Stage Flow Hydrograph=Bela            ,Bela_reach      ,17720.02
Stage Flow Hydrograph=Bela            ,Bela_reach      ,17714.08
Stage Flow Hydrograph=Bela            ,Bela_reach      ,17692.02
Stage Flow Hydrograph=Bela            ,Bela_reach      ,17647.97
Stage Flow Hydrograph=Bela            ,Bela_reach      ,17602.02
Stage Flow Hydrograph=Bela            ,Bela_reach      ,17556.69
Stage Flow Hydrograph=Bela            ,Bela_reach      ,17514.01
Stage Flow Hydrograph=Bela            ,Bela_reach      ,17511.2
Stage Flow Hydrograph=Bela            ,Bela_reach      ,17500.01
Stage Flow Hydrograph=Bela            ,Bela_reach      ,17440.04
Stage Flow Hydrograph=Bela            ,Bela_reach      ,17378
Stage Flow Hydrograph=Bela            ,Bela_reach      ,17375.01
Stage Flow Hydrograph=Bela            ,Bela_reach      ,17366
Stage Flow Hydrograph=Bela            ,Bela_reach      ,17340.65
Stage Flow Hydrograph=Bela            ,Bela_reach      ,17318.97
Stage Flow Hydrograph=Bela            ,Bela_reach      ,17291.99
Stage Flow Hydrograph=Bela            ,Bela_reach      ,17259.19
Stage Flow Hydrograph=Bela            ,Bela_reach      ,17233.92
Stage Flow Hydrograph=Bela            ,Bela_reach      ,17217.4
Stage Flow Hydrograph=Bela            ,Bela_reach      ,17199.2
Stage Flow Hydrograph=Bela            ,Bela_reach      ,17182.49
Stage Flow Hydrograph=Bela            ,Bela_reach      ,17160.8
Stage Flow Hydrograph=Bela            ,Bela_reach      ,17145.99
Stage Flow Hydrograph=Bela            ,Bela_reach      ,17113.28
Stage Flow Hydrograph=Bela            ,Bela_reach      ,17089.04
Stage Flow Hydrograph=Bela            ,Bela_reach      ,17072.46
Stage Flow Hydrograph=Bela            ,Bela_reach      ,17059.68
Stage Flow Hydrograph=Bela            ,Bela_reach      ,17042.5
Stage Flow Hydrograph=Bela            ,Bela_reach      ,17022.69
Stage Flow Hydrograph=Bela            ,Bela_reach      ,16998.19
Stage Flow Hydrograph=Bela            ,Bela_reach      ,16987.28
Stage Flow Hydrograph=Bela            ,Bela_reach      ,16981.23
Stage Flow Hydrograph=Bela            ,Bela_reach      ,16972.87
Stage Flow Hydrograph=Bela            ,Bela_reach      ,16965.79
Stage Flow Hydrograph=Bela            ,Bela_reach      ,16958.19
Stage Flow Hydrograph=Bela            ,Bela_reach      ,16953.35
Stage Flow Hydrograph=Bela            ,Bela_reach      ,16947.94
Stage Flow Hydrograph=Bela            ,Bela_reach      ,16933.84
Stage Flow Hydrograph=Bela            ,Bela_reach      ,16908.96
Stage Flow Hydrograph=Bela            ,Bela_reach      ,16890.01
Stage Flow Hydrograph=Bela            ,Bela_reach      ,16865
Stage Flow Hydrograph=Bela            ,Bela_reach      ,16839.98
Stage Flow Hydrograph=Bela            ,Bela_reach      ,16821.12
Stage Flow Hydrograph=Bela            ,Bela_reach      ,16779.33
Stage Flow Hydrograph=Bela            ,Bela_reach      ,16751.94
Stage Flow Hydrograph=Bela            ,Bela_reach      ,16730.52
Stage Flow Hydrograph=Bela            ,Bela_reach      ,16725.7
Stage Flow Hydrograph=Bela            ,Bela_reach      ,16711.55
Stage Flow Hydrograph=Bela            ,Bela_reach      ,16685.61
Stage Flow Hydrograph=Bela            ,Bela_reach      ,16667.18
Stage Flow Hydrograph=Bela            ,Bela_reach      ,16661.4
Stage Flow Hydrograph=Bela            ,Bela_reach      ,16654.54
Stage Flow Hydrograph=Bela            ,Bela_reach      ,16647.88
Stage Flow Hydrograph=Bela            ,Bela_reach      ,16641.56
Stage Flow Hydrograph=Bela            ,Bela_reach      ,16625.96
Stage Flow Hydrograph=Bela            ,Bela_reach      ,16605.36
Stage Flow Hydrograph=Bela            ,Bela_reach      ,16585.06
Stage Flow Hydrograph=Bela            ,Bela_reach      ,16568.98
Stage Flow Hydrograph=Bela            ,Bela_reach      ,16555.88
Stage Flow Hydrograph=Bela            ,Bela_reach      ,16534.61
Stage Flow Hydrograph=Bela            ,Bela_reach      ,16530.05
Stage Flow Hydrograph=Bela            ,Bela_reach      ,16526.03
Stage Flow Hydrograph=Bela            ,Bela_reach      ,16521.83
Stage Flow Hydrograph=Bela            ,Bela_reach      ,16518.81
Stage Flow Hydrograph=Bela            ,Bela_reach      ,16515.82
Stage Flow Hydrograph=Bela            ,Bela_reach      ,16512.96
Stage Flow Hydrograph=Bela            ,Bela_reach      ,16510
Stage Flow Hydrograph=Bela            ,Bela_reach      ,16506.91
Stage Flow Hydrograph=Bela            ,Bela_reach      ,16496.64
Stage Flow Hydrograph=Bela            ,Bela_reach      ,16484.82
Stage Flow Hydrograph=Bela            ,Bela_reach      ,16457.95
Stage Flow Hydrograph=Bela            ,Bela_reach      ,16428.81
Stage Flow Hydrograph=Bela            ,Bela_reach      ,16401.95
Stage Flow Hydrograph=Bela            ,Bela_reach      ,16400.07
Stage Flow Hydrograph=Bela            ,Bela_reach      ,16391.95
Stage Flow Hydrograph=Bela            ,Bela_reach      ,16373.55
Stage Flow Hydrograph=Bela            ,Bela_reach      ,16338.53
Stage Flow Hydrograph=Bela            ,Bela_reach      ,16313.36
Stage Flow Hydrograph=Bela            ,Bela_reach      ,16285.94
Stage Flow Hydrograph=Bela            ,Bela_reach      ,16264.13
Stage Flow Hydrograph=Bela            ,Bela_reach      ,16241.06
Stage Flow Hydrograph=Bela            ,Bela_reach      ,16217.94
Stage Flow Hydrograph=Bela            ,Bela_reach      ,16203.55
Stage Flow Hydrograph=Bela            ,Bela_reach      ,16186.97
Stage Flow Hydrograph=Bela            ,Bela_reach      ,16165.19
Stage Flow Hydrograph=Bela            ,Bela_reach      ,16140.98
Stage Flow Hydrograph=Bela            ,Bela_reach      ,16119.07
Stage Flow Hydrograph=Bela            ,Bela_reach      ,16106.59
Stage Flow Hydrograph=Bela            ,Bela_reach      ,16074.51
Stage Flow Hydrograph=Bela            ,Bela_reach      ,16056.34
Stage Flow Hydrograph=Bela            ,Bela_reach      ,16030.82
Stage Flow Hydrograph=Bela            ,Bela_reach      ,16007.74
Stage Flow Hydrograph=Bela            ,Bela_reach      ,16000.73
Stage Flow Hydrograph=Bela            ,Bela_reach      ,15989.93
Stage Flow Hydrograph=Bela            ,Bela_reach      ,15967.45
Stage Flow Hydrograph=Bela            ,Bela_reach      ,15957.93
Stage Flow Hydrograph=Bela            ,Bela_reach      ,15943.28
Stage Flow Hydrograph=Bela            ,Bela_reach      ,15934.58
Stage Flow Hydrograph=Bela            ,Bela_reach      ,15928.39
Stage Flow Hydrograph=Bela            ,Bela_reach      ,15916.88
Stage Flow Hydrograph=Bela            ,Bela_reach      ,15887.99
Stage Flow Hydrograph=Bela            ,Bela_reach      ,15868.15
Stage Flow Hydrograph=Bela            ,Bela_reach      ,15856.69
Stage Flow Hydrograph=Bela            ,Bela_reach      ,15829.9
Stage Flow Hydrograph=Bela            ,Bela_reach      ,15810.7
Stage Flow Hydrograph=Bela            ,Bela_reach      ,15786.92
Stage Flow Hydrograph=Bela            ,Bela_reach      ,15766.56
Stage Flow Hydrograph=Bela            ,Bela_reach      ,15754.75
Stage Flow Hydrograph=Bela            ,Bela_reach      ,15743.46
Stage Flow Hydrograph=Bela            ,Bela_reach      ,15729.91
Stage Flow Hydrograph=Bela            ,Bela_reach      ,15707.91
Stage Flow Hydrograph=Bela            ,Bela_reach      ,15704.01
Stage Flow Hydrograph=Bela            ,Bela_reach      ,15698.34
Stage Flow Hydrograph=Bela            ,Bela_reach      ,15681.9
Stage Flow Hydrograph=Bela            ,Bela_reach      ,15631.9
Stage Flow Hydrograph=Bela            ,Bela_reach      ,15561.9
Stage Flow Hydrograph=Bela            ,Bela_reach      ,15497.89
Stage Flow Hydrograph=Bela            ,Bela_reach      ,15429.05
Stage Flow Hydrograph=Bela            ,Bela_reach      ,15373.89

--- PPO_Kvasiny_efektiv.p11 (plan) ---

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Plan Title=N-Q100
Short Identifier=N-Q100
Geom File=g13
Flow File=f06
Calc Critical at every XS
Secant Critical Depth
DSS File=dss

--- PPO_Kvasiny_efektiv.f04 (steady flow) ---

Flow Title=Q20
Program Version=5.03
Number of Profiles= 1
Profile Names=Q20
River Rch & RM=Bela,Bela_reach      ,19010.09
    40.9
River Rch & RM=Bela,Bela_reach      ,17378
    42.3
Boundary for River Rch & Prof#=Bela,Bela_reach      , 1
Up Type= 1
Up Known WS=369.11
Dn Type= 1
Dn Known WS=335.87
DSS Import GetInterval= 0
DSS Import GetPeak= 0
DSS Import FillOption= 0

--- PPO_Kvasiny_efektiv.f01 (steady flow) ---

Flow Title=Q5
Program Version=5.03
Number of Profiles= 1
Profile Names=Q5
River Rch & RM=Bela,Bela_reach      ,19010.09
    20.3
River Rch & RM=Bela,Bela_reach      ,17378
    21.3
Boundary for River Rch & Prof#=Bela,Bela_reach      , 1
Up Type= 1
Up Known WS=368.5
Dn Type= 1
Dn Known WS=335.17
DSS Import GetInterval= 0
DSS Import GetPeak= 0
DSS Import FillOption= 0

--- PPO_Kvasiny_efektiv.f02 (steady flow) ---

Flow Title=Q10
Program Version=5.03
Number of Profiles= 1
Profile Names=Q10
River Rch & RM=Bela,Bela_reach      ,19010.09
    29.5
River Rch & RM=Bela,Bela_reach      ,17378
    30.7
Boundary for River Rch & Prof#=Bela,Bela_reach      , 1
Up Type= 1
Up Known WS=368.81
Dn Type= 1
Dn Known WS=335.51
DSS Import GetInterval= 0
DSS Import GetPeak= 0
DSS Import FillOption= 0

--- PPO_Kvasiny_efektiv.f03 (steady flow) ---

Flow Title=QN
Program Version=5.03
Number of Profiles= 5
Profile Names=Q5,Q10,Q20,Q50,Q100
River Rch & RM=Bela,Bela_reach      ,19010.09
    20.3    29.5    40.9    59.5    76.8
River Rch & RM=Bela,Bela_reach      ,17378
    21.3    30.7    42.3    61.3    78.8
Boundary for River Rch & Prof#=Bela,Bela_reach      , 1
Up Type= 3
Up Slope=0.007
Dn Type= 3
Dn Slope=0.0155
Boundary for River Rch & Prof#=Bela,Bela_reach      , 2
Up Type= 3
Up Slope=0.007
Dn Type= 3
Dn Slope=0.0155
Boundary for River Rch & Prof#=Bela,Bela_reach      , 3
Up Type= 3
Up Slope=0.007
Dn Type= 3
Dn Slope=0.0155
Boundary for River Rch & Prof#=Bela,Bela_reach      , 4
Up Type= 3
Up Slope=0.007
Dn Type= 3
Dn Slope=0.0155
Boundary for River Rch & Prof#=Bela,Bela_reach      , 5
Up Type= 3
Up Slope=0.007
Dn Type= 3
Dn Slope=0.0155
DSS Import GetInterval= 0
DSS Import GetPeak= 0
DSS Import FillOption= 0

--- PPO_Kvasiny_efektiv.f05 (steady flow) ---

Flow Title=Q50
Program Version=5.03
Number of Profiles= 1
Profile Names=Q50
River Rch & RM=Bela,Bela_reach      ,19010.09
    59.5
River Rch & RM=Bela,Bela_reach      ,17378
    61.3
Boundary for River Rch & Prof#=Bela,Bela_reach      , 1
Up Type= 1
Up Known WS=369.6
Dn Type= 1
Dn Known WS=336.4
DSS Import GetInterval= 0
DSS Import GetPeak= 0
DSS Import FillOption= 0

--- PPO_Kvasiny_efektiv.f06 (steady flow) ---

Flow Title=Q100
Program Version=5.03
Number of Profiles= 1
Profile Names=Q100
River Rch & RM=Bela,Bela_reach      ,19010.09
    76.8
River Rch & RM=Bela,Bela_reach      ,17378
    78.8
Boundary for River Rch & Prof#=Bela,Bela_reach      , 1
Up Type= 1
Up Known WS=369.8
Dn Type= 1
Dn Known WS=336.75
DSS Import GetInterval= 0
DSS Import GetPeak= 0
DSS Import FillOption= 0

--- PPO_Kvasiny_efektiv.u01 (unsteady flow) ---

Flow Title=Q10_unst
Program Version=5.03
Use Restart= 0
Boundary Location=Bela            ,Bela_reach      ,19010.09,        ,                ,                ,                ,
Interval=5MIN
Flow Hydrograph= 100
      15      20      25      30      40      60    78.8    78.8    78.8    78.8
    78.8    78.8    78.8    78.8    78.8    78.8    78.8    78.8    78.8    78.8
    78.8    78.8    78.8    78.8    78.8    78.8    78.8    78.8    78.8    78.8
    78.8    78.8    78.8    78.8    78.8    78.8    78.8    78.8    78.8    78.8
    78.8    78.8    78.8    78.8    78.8    78.8    78.8    78.8    78.8    78.8
    78.8    78.8    78.8    78.8    78.8    78.8    78.8    78.8    78.8    78.8
    78.8    78.8    78.8    78.8    78.8    78.8    78.8    78.8    78.8    78.8
    78.8    78.8    78.8    78.8    78.8    78.8    78.8    78.8    78.8    78.8
    78.8    78.8    78.8    78.8    78.8    78.8    78.8    78.8    78.8    78.8
    78.8    78.8    78.8    78.8    78.8    78.8    78.8    78.8    78.8    78.8
Use DSS=False
Use Fixed Start Time=False
Is Critical Boundary=False
Boundary Location=Bela            ,Bela_reach      ,15373.89,        ,                ,                ,                ,
Interval=1DAY
Stage Hydrograph= 3
  335.51  335.51  335.51
Use DSS=False
Use Fixed Start Time=False
Is Critical Boundary=False
Boundary Location=Bela            ,Bela_reach      ,17440.04,        ,                ,                ,                ,
Interval=1DAY
Lateral Inflow Hydrograph= 3
     1.2     1.2     1.2
Use DSS=False
Use Fixed Start Time=False
Is Critical Boundary=False

--- PPO_Kvasiny_efektiv.u02 (unsteady flow) ---

Flow Title=A1
Program Version=5.03
Use Restart= 0
Boundary Location=Bela            ,Bela_reach      ,19010.09,        ,                ,                ,                ,
Interval=5MIN
Flow Hydrograph= 100
      15      20      25      30    78.8    78.8    78.8    78.8    78.8    78.8
    78.8    78.8    78.8    78.8    78.8    78.8    78.8    78.8    78.8    78.8
    78.8    78.8    78.8    78.8    78.8    78.8    78.8    78.8    78.8    78.8
    78.8    78.8    78.8    78.8    78.8    78.8    78.8    78.8    78.8    78.8
    78.8    78.8    78.8    78.8    78.8    78.8    78.8    78.8    78.8    78.8
    78.8    78.8    78.8    78.8    78.8    78.8    78.8    78.8    78.8    78.8
    78.8    78.8    78.8    78.8    78.8    78.8    78.8    78.8    78.8    78.8
    78.8    78.8    78.8    78.8    78.8    78.8    78.8    78.8    78.8    78.8
    78.8    78.8    78.8    78.8    78.8    78.8    78.8    78.8    78.8    78.8
    78.8    78.8    78.8    78.8    78.8    78.8    78.8    78.8    78.8    78.8
Use DSS=False
Use Fixed Start Time=False
Is Critical Boundary=False
Boundary Location=Bela            ,Bela_reach      ,15373.89,        ,                ,                ,                ,
Interval=1DAY
Stage Hydrograph= 3
  335.51  335.51  335.51
Use DSS=False
Use Fixed Start Time=False
Is Critical Boundary=False
Boundary Location=Bela            ,Bela_reach      ,17440.04,        ,                ,                ,                ,
Interval=1DAY
Lateral Inflow Hydrograph= 3
     1.2     1.2     1.2
Use DSS=False
Use Fixed Start Time=False
Is Critical Boundary=False

--- PPO_Kvasiny_efektiv.u03 (unsteady flow) ---

Flow Title=A2
Program Version=5.03
Use Restart= 0
Initial Flow Loc=Bela            ,Bela_reach      ,19010.09,10
Boundary Location=Bela            ,Bela_reach      ,19010.09,        ,                ,                ,                ,
Interval=5MIN
Flow Hydrograph= 100
      15      20      25      30    78.8    78.8    78.8    78.8    78.8    78.8
    78.8    78.8    78.8    78.8    78.8    78.8    78.8    78.8    78.8    78.8
    78.8    78.8    78.8    78.8    78.8    78.8    78.8    78.8    78.8    78.8
    78.8    78.8    78.8    78.8    78.8    78.8    78.8    78.8    78.8    78.8
    78.8    78.8    78.8    78.8    78.8    78.8    78.8    78.8    78.8    78.8
    78.8    78.8    78.8    78.8    78.8    78.8    78.8    78.8    78.8    78.8
    78.8    78.8    78.8    78.8    78.8    78.8    78.8    78.8    78.8    78.8
    78.8    78.8    78.8    78.8    78.8    78.8    78.8    78.8    78.8    78.8
    78.8    78.8    78.8    78.8    78.8    78.8    78.8    78.8    78.8    78.8
    78.8    78.8    78.8    78.8    78.8    78.8    78.8    78.8    78.8    78.8
Use DSS=False
Use Fixed Start Time=False
Is Critical Boundary=False
Boundary Location=Bela            ,Bela_reach      ,15373.89,        ,                ,                ,                ,
Interval=1DAY
Stage Hydrograph= 3
  335.51  335.51  335.51
Use DSS=False
Use Fixed Start Time=False
Is Critical Boundary=False
Boundary Location=Bela            ,Bela_reach      ,17440.04,        ,                ,                ,                ,
Interval=1DAY
Lateral Inflow Hydrograph= 3
     1.2     1.2     1.2
Use DSS=False
Use Fixed Start Time=False
Is Critical Boundary=False

--- PPO_Kvasiny_efektiv.u05 (unsteady flow) ---

Flow Title=Q20_Un
Program Version=5.03
Use Restart= 0
Boundary Location=Bela            ,Bela_reach      ,19010.09,        ,                ,                ,                ,
Interval=5MIN
Flow Hydrograph= 100
      20    22.5      25    27.5      30    32.5      35    37.5      40    40.9
    40.9    40.9    40.9    40.9    40.9    40.9    40.9    40.9    40.9    40.9
    40.9    40.9    40.9    40.9    40.9    40.9    40.9    40.9    40.9    40.9
    40.9    40.9    40.9    40.9    40.9    40.9    40.9    40.9    40.9    40.9
    40.9    40.9    40.9    40.9    40.9    40.9    40.9    40.9    40.9    40.9
    40.9    40.9    40.9    40.9    40.9    40.9    40.9    40.9    40.9    40.9
    40.9    40.9    40.9    40.9    40.9    40.9    40.9    40.9    40.9    40.9
    40.9    40.9    40.9    40.9    40.9    40.9    40.9    40.9    40.9    40.9
    40.9    40.9    40.9    40.9    40.9    40.9    40.9    40.9    40.9    40.9
    40.9    40.9    40.9    40.9    40.9    40.9    40.9    40.9    40.9    40.9
Use DSS=False
Use Fixed Start Time=False
Is Critical Boundary=False
Boundary Location=Bela            ,Bela_reach      ,15373.89,        ,                ,                ,                ,
Friction Slope=0.01
Boundary Location=Bela            ,Bela_reach      ,17440.04,        ,                ,                ,                ,
Interval=1DAY
Lateral Inflow Hydrograph= 3
     1.4     1.4     1.4
Use DSS=False
Use Fixed Start Time=False
Is Critical Boundary=False

--- PPO_Kvasiny_efektiv.g15 (geometry) ---

Geom Title=N-Q20_bez_SO02
Program Version=5.03

River Reach=Bela            ,Bela_reach
Reach XY= 30
    -608258.5691   -1044176.4596-608333.35999999     -1044360.16
      -608454.35      -1044498.2      -608548.67     -1044557.83
      -608629.89     -1044647.63-608796.03999999     -1044723.89
-608856.07999999     -1044665.71       -609030.6     -1044873.75
      -609251.53     -1045060.16      -609348.73      -1045087.3
      -609414.69     -1045145.55       -609610.1     -1045156.04
-609723.21999999     -1045220.84-609837.85999999     -1045233.73
      -610057.25     -1045304.56      -610087.68     -1045367.77
      -610168.57     -1045417.49-610215.82999999     -1045495.44
-610388.62999999     -1045581.56      -610489.84     -1045671.74
-610731.69999999     -1045669.15-610811.28999999     -1045758.61
      -610914.55     -1045777.58      -611047.64       -1045872.
    -611195.6472   -1045906.4994-611417.96999999     -1045871.47
-611502.07999999     -1045951.08-611655.69999999      -1045978.5
      -611728.16     -1046045.97    -611879.9978   -1046121.2762

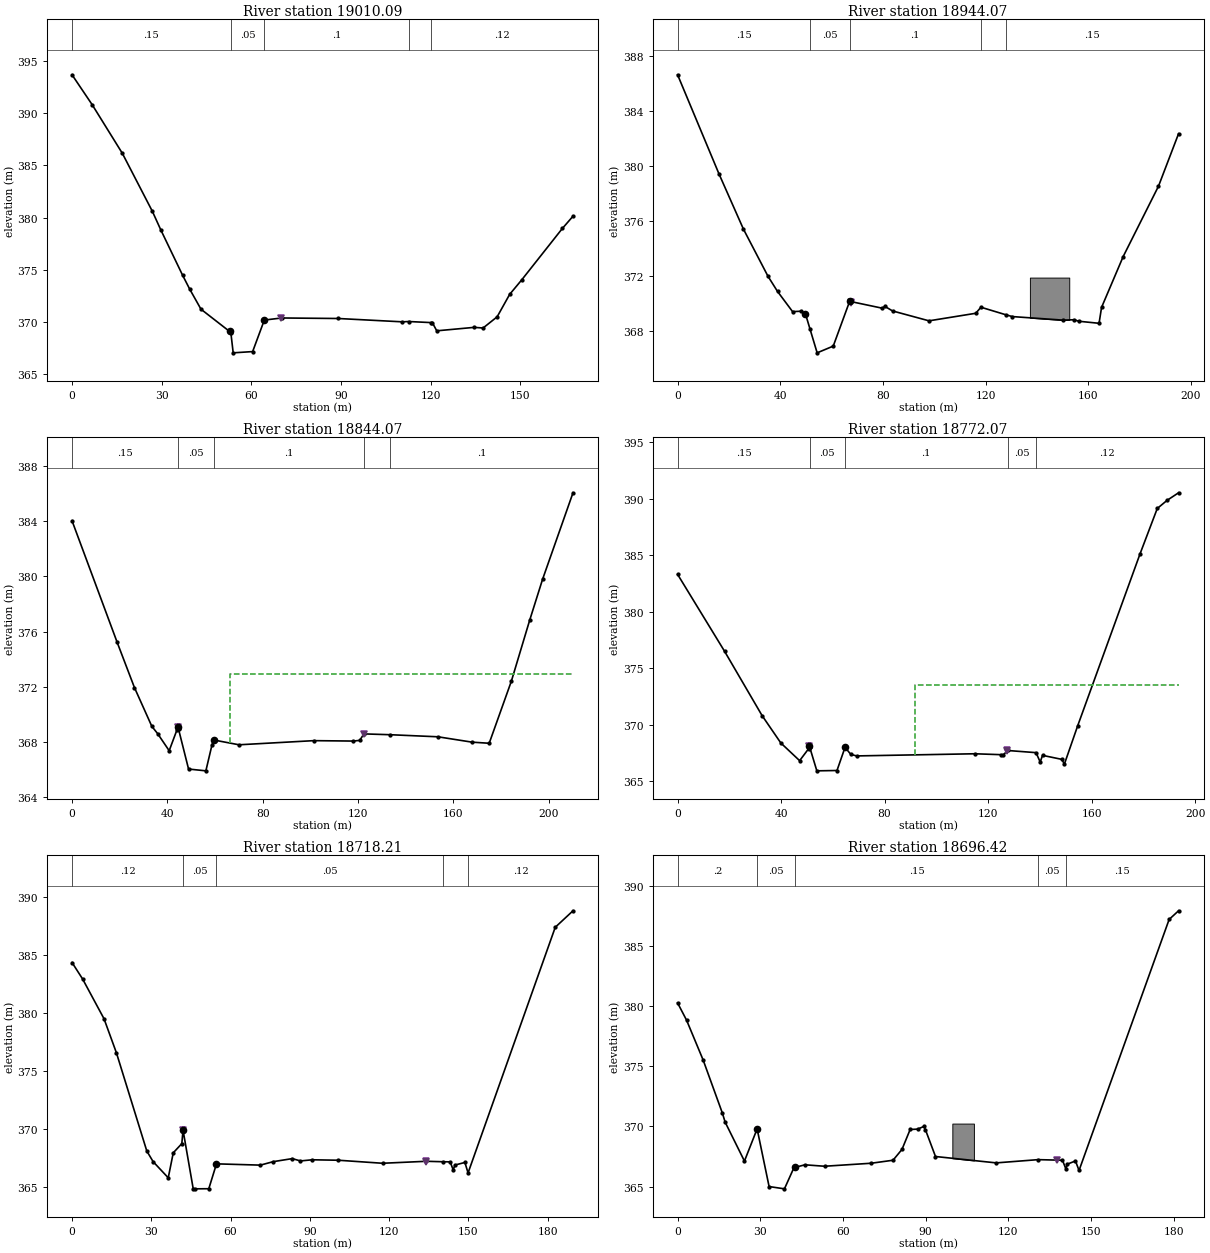
Type RM Length L Ch R = 1 ,19010.09,63.81,66.01,58.86
XS GIS Cut Line= 5
-608502.66209999   -1044593.6857    -608536.6251   -1044560.8986
     -608549.118   -1044545.2805    -608586.5786   -1044508.0775
     -608607.896   -1044465.4426
#Sta/Elev= 28
       0  393.68    6.75  390.81   16.83  386.16    26.9  380.59   29.66  378.85
   36.98  374.49   39.39  373.14   43.16  371.22   52.73  369.09   53.15 368.985
   53.94  367.04   60.45  367.16   64.36  370.18    64.4370.1805   70.18  370.38
   89.09  370.33   110.6  370.01  112.68  370.04     120  369.94  120.58  369.94
  122.07  369.15  134.59  369.48  137.58  369.42  142.28  370.49  146.47  372.64
  150.45  374.01  164.12  378.96  167.67  380.13
#Mann= 5 ,-1 , 0
       0     .15       0   53.15     .05       0    64.4      .1       0
  112.68     .05       0     120     .12       0
Levee=0,,,-1,69.94,370.38,,
Bank Sta=52.73,64.36
XS Rating Curve= 0 ,0
Exp/Cntr=0.3,0.1

Type RM Length L Ch R = 1 ,18944.07,107.06,100,81.52
XS GIS Cut Line= 5
    -608546.4782   -1044642.7763-608578.86259999   -1044608.0005
     -608594.864   -1044596.0024    -608642.9144   -1044514.1948
    -608653.0656   -1044483.0645
#Sta/Elev= 29
       0  386.63   16.09  379.43   25.66  375.39   35.22  371.96   38.92  370.86
   44.79  369.39   48.23  369.42    49.8  369.23   51.56368.1339   54.36  366.39
   60.63  366.88   67.02  370.14   67.03370.1393   79.71  369.64   80.76  369.77
   83.72  369.44   97.93  368.72  116.15  369.27  118.16  369.71   127.9369.1595
  130.38  369.03  150.14  368.77  154.47   368.8  156.24  368.69  164.17  368.54
  165.15   369.7  173.57   373.4  187.32  378.52  195.14  382.34
#Mann= 5 ,-1 , 0
       0     .15       0   51.56     .05       0   67.03      .1       0
  118.16     .05       0   127.9     .15       0
Levee=0,,,-1,67.44,370.01,,
#Block Obstruct= 1 ,-1
  137.23  152.56371.8682
Bank Sta=49.8,67.02
XS Rating Curve= 0 ,0
Exp/Cntr=0.3,0.1

Type RM Length L Ch R = 1 ,18844.07,72.16,72,73.34
XS GIS Cut Line= 6
-608649.34349999   -1044712.1427    -608661.1943   -1044671.2681
    -608666.6842   -1044652.0363-608687.57959999     -1044587.96
    -608711.2657   -1044551.4157    -608740.0273   -1044528.7448
#Sta/Elev= 28
       0  384.04   18.89  375.24   26.18  371.94   33.47  369.13    35.9   368.6
   40.75  367.36   44.03  368.88   44.31  369.11   44.35  369.09   44.67  368.93
   48.88  366.03   56.14   365.9   58.65  367.74   59.34  368.14   59.46368.1367
   70.03  367.79  101.43  368.09     118  368.06  120.69  368.11  122.41  368.58
  133.48  368.52  153.46  368.37  167.81  367.98  174.98   367.9  184.29  372.41
  191.95  376.82  197.36  379.79  210.13  386.07
#Mann= 5 ,-1 , 0
       0     .15       0   44.35     .05       0   59.46      .1       0
  122.41     .05       0  133.48      .1       0
Levee=-1,44.3,369.1,-1,122.55,368.54,,
#XS Ineff= 2 , 0
                            66.4           372.9
Permanent Ineff=
       F       F
Bank Sta=44.31,59.34
XS Rating Curve= 0 ,0
Exp/Cntr=0.3,0.1

Type RM Length L Ch R = 1 ,18772.07,49.5,53.87,46.34
XS GIS Cut Line= 5
-608717.01799999   -1044739.5508    -608729.3973    -1044693.413
    -608735.3242   -1044674.3114    -608762.3599   -1044598.1112
    -608783.6774   -1044558.5216
#Sta/Elev= 28
       0  383.29   18.17  376.48   32.67  370.79   39.91  368.37   47.16  366.81
   50.67  367.88   50.91  368.11   50.99368.0506   53.81  365.91    61.6  365.94
    64.7367.9844   64.71  367.99   66.95  367.36   69.23  367.23  114.85  367.42
     125  367.34  125.72  367.28   127.5  367.71  138.51  367.52  140.12  366.69
  141.02  367.28  148.38  366.93  149.49  366.52  154.63  369.91  178.71  385.11
  185.36  389.12  189.15  389.84  193.59  390.51
#Mann= 5 ,-1 , 0
       0     .15       0   50.99     .05       0    64.7      .1       0
   127.5     .05       0  138.51     .12       0
Levee=-1,50.87,368.11,-1,127.37,367.79,,
#XS Ineff= 2 , 0
                            91.8          373.46
Permanent Ineff=
       F       F
Bank Sta=50.91,64.71
XS Rating Curve= 0 ,0
Exp/Cntr=0.3,0.1

Type RM Length L Ch R = 1 ,18718.21,29.06,21.79,6.52
XS GIS Cut Line= 5
-608753.54699999   -1044753.4637     -608781.487   -1044705.5211
    -608789.4245   -1044670.2786    -608798.9496    -1044622.336
-608821.80959999   -1044578.8384
#Sta/Elev= 30
       0  384.35    4.01  382.93   12.11  379.51   16.79  376.59   28.31  368.13
   30.69  367.22   36.42  365.83   38.32  367.98   41.56  368.77   42.02  369.93
   45.86   364.9   46.37  364.88   51.77  364.89   54.68  367.03   71.29  366.92
    76.2  367.22   83.37  367.48   86.48  367.28   90.94  367.38  100.86  367.34
  117.53  367.08  134.11  367.25  140.49  367.21  143.13   367.2  144.27  366.52
  144.99  366.93  148.71  367.15  149.91  366.25  182.91  387.38  189.63   388.8
#Mann= 5 ,-1 , 0
       0     .12       0   42.02     .05       0   54.68     .05       0
  140.49     .05       0  149.91     .12       0
Levee=-1,42.02,369.93,-1,134.06,367.22,,
Bank Sta=42.02,54.68
XS Rating Curve= 0 ,0
Exp/Cntr=0.3,0.1

Type RM Length L Ch R = 1 ,18696.42,50.22,38.35,4.09
XS GIS Cut Line= 4
-608796.05849999    -1044760.252    -608795.7939   -1044693.8414
    -608803.2023   -1044622.1392    -608824.1044   -1044584.3037
#Sta/Elev= 30
       0  380.28    3.25  378.85    9.27  375.53   16.25  371.11   17.25  370.36
   24.25  367.12   28.85   369.8   33.19     365   38.76  364.81   42.24  366.59
    42.5  366.59   46.19  366.81   53.31  366.69   70.21  366.94   78.14  367.19
   81.39  368.09   84.36  369.75   87.08  369.78   89.29     370   89.92  369.72
   93.55   367.5  115.58  366.97  130.78  367.24  139.61  367.19  140.83  366.48
  141.43  366.87  144.32  367.13  145.62  366.34   178.3  387.23  181.72  387.95
#Mann= 5 ,-1 , 0
       0      .2       0   28.85     .05       0    42.5     .15       0
  130.78     .05       0  140.83     .15       0
Levee=0,,,-1,137.53,367.22,,
#Block Obstruct= 1 ,-1
   99.66  107.48370.2419
Bank Sta=28.85,42.5
XS Rating Curve= 0 ,0
Exp/Cntr=0.3,0.1

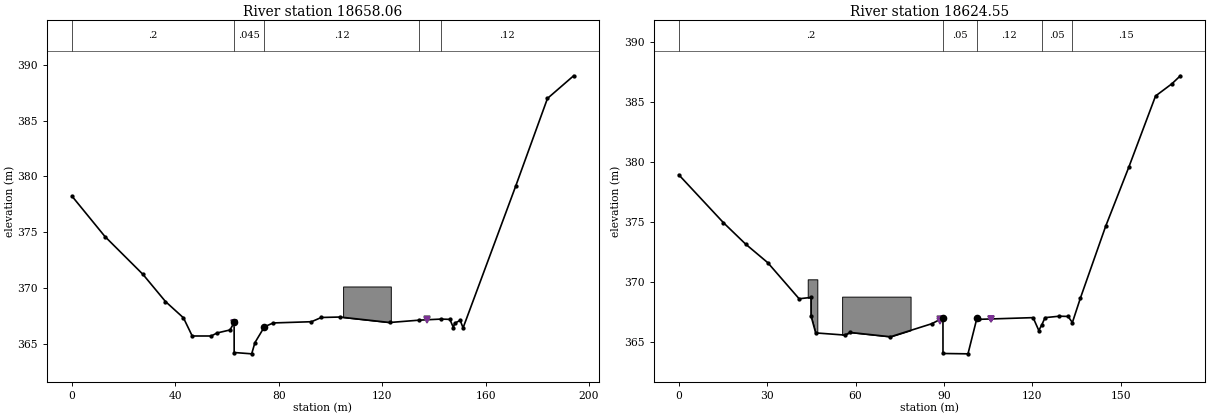
Type RM Length L Ch R = 1 ,18658.06,22,33.51,26.87
XS GIS Cut Line= 6
-608811.08549999    -1044755.116     -608825.589   -1044701.0257
    -608807.8792   -1044691.7325-608803.30299999   -1044664.7705
    -608806.6867   -1044622.1356-608834.09479999   -1044582.8844
#Sta/Elev= 30
       0  378.22   12.72  374.61   27.41  371.22   36.15  368.78    43.1  367.32
    46.5  365.69   53.84  365.69   56.09  365.96   61.11  366.23   62.71   366.9
   62.73  364.21   69.51  364.09   70.75  365.09   74.45  366.52   74.46366.5206
   77.86  366.86   92.64  366.97   96.45  367.35  103.66  367.39  122.92   366.9
  134.34  367.11   142.8367.2064  146.19  367.18  147.55  366.45  148.03  366.83
  150.17  367.09  151.31  366.42  171.67  379.13  183.96  386.99  194.08  389.02
#Mann= 5 ,-1 , 0
       0      .2       0   62.71    .045       0   74.46     .12       0
  134.34     .05       0   142.8     .12       0
Levee=-1,62.62,366.83,-1,137.53,367.18,,
#Block Obstruct= 1 ,-1
  104.88  123.34370.1295
Bank Sta=62.71,74.45
XS Rating Curve= 0 ,0
Exp/Cntr=0.3,0.1

Type RM Length L Ch R = 1 ,18624.55,27.54,38.49,47.2
XS GIS Cut Line= 6
    -608813.3292   -1044757.0751-608830.65819999   -1044713.3605
     -608838.708   -1044671.6675    -608829.9133   -1044663.7088
    -608830.5483   -1044653.6758    -608851.3869   -1044598.6741
#Sta/Elev= 30
       0  378.92   15.14  374.94   22.67  373.16    30.2  371.61   40.84  368.61
   44.87  368.72   44.88  367.19   46.46  365.77   56.35  365.59   58.15  365.81
   71.85  365.45   85.93  366.54   89.66  367.02   89.67  364.06   98.15  364.03
   101.2  367.01  101.96   366.9  120.26  367.04  122.19  365.97  123.18  366.43
  124.31  367.04  129.18  367.16  132.12  367.14  133.58  366.63  136.31  368.67
  144.85  374.62  152.76  379.57  161.81  385.47  167.38  386.49  170.22  387.15
#Mann= 5 ,-1 , 0
       0      .2       0   89.66     .05       0   101.2     .12       0
  123.18     .05       0  133.58     .15       0
Levee=-1,88.75,366.79,-1,105.8,366.93,,
#Block Obstruct= 2 ,-1
   43.76   47.02 370.226   55.44   78.67368.7872
Bank Sta=89.66,101.2
XS Rating Curve= 0 ,0
Exp/Cntr=0.3,0.1