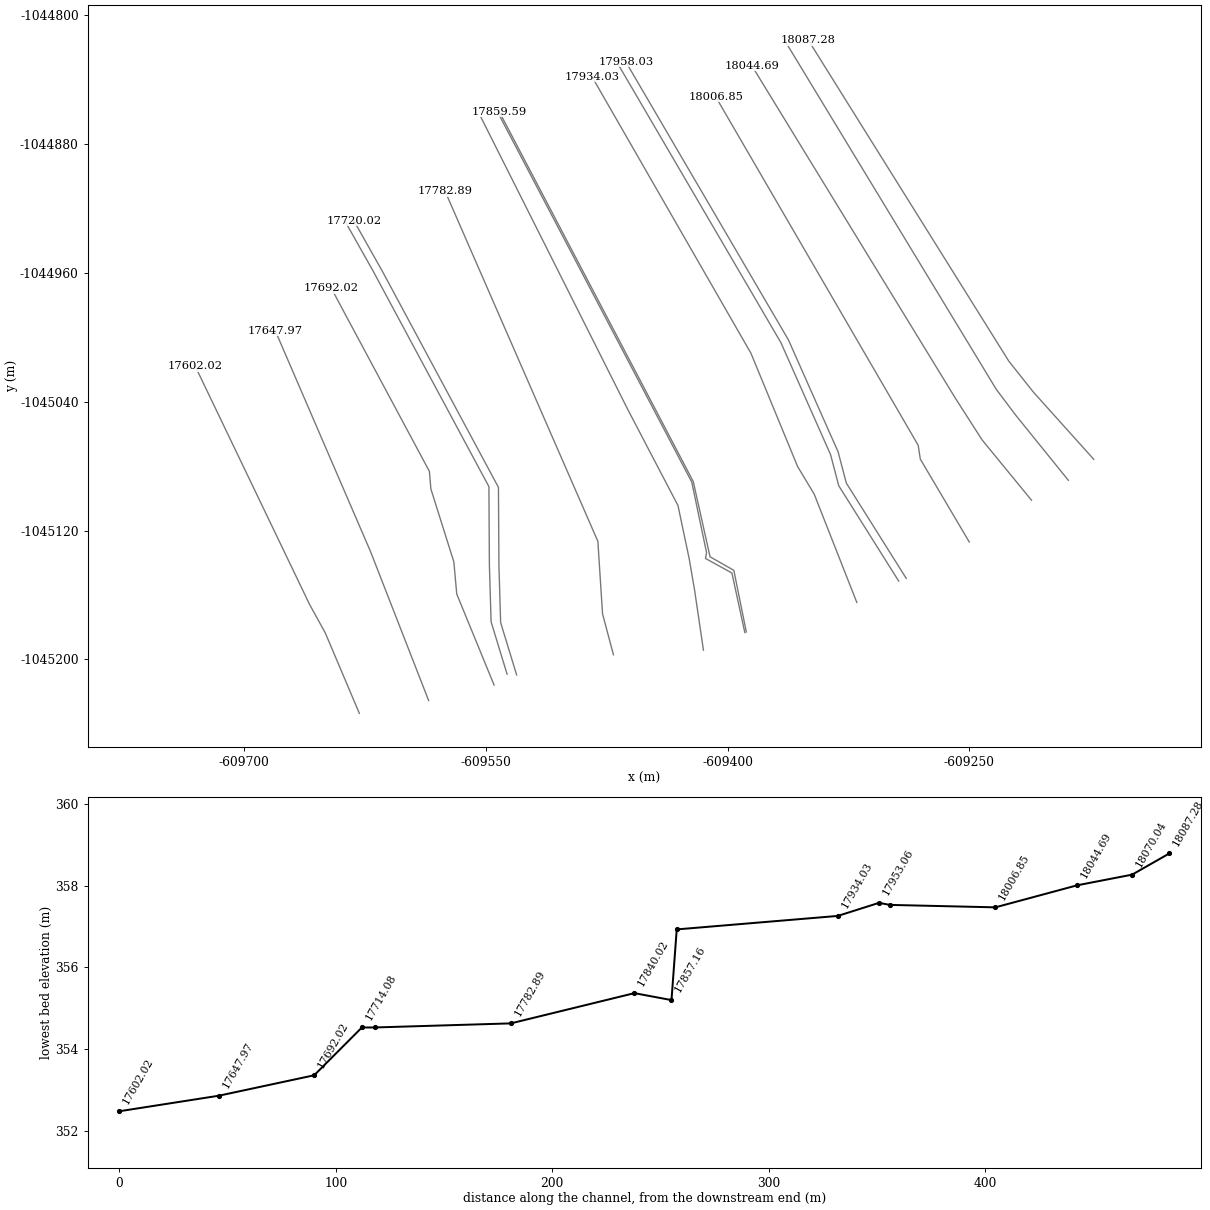
HEC-RAS study PPO_Kvasiny_efektiv.prj: PPO_Kvasiny_efektivita

--- PPO_Kvasiny_efektiv.g15 (geometry) --- (continued)

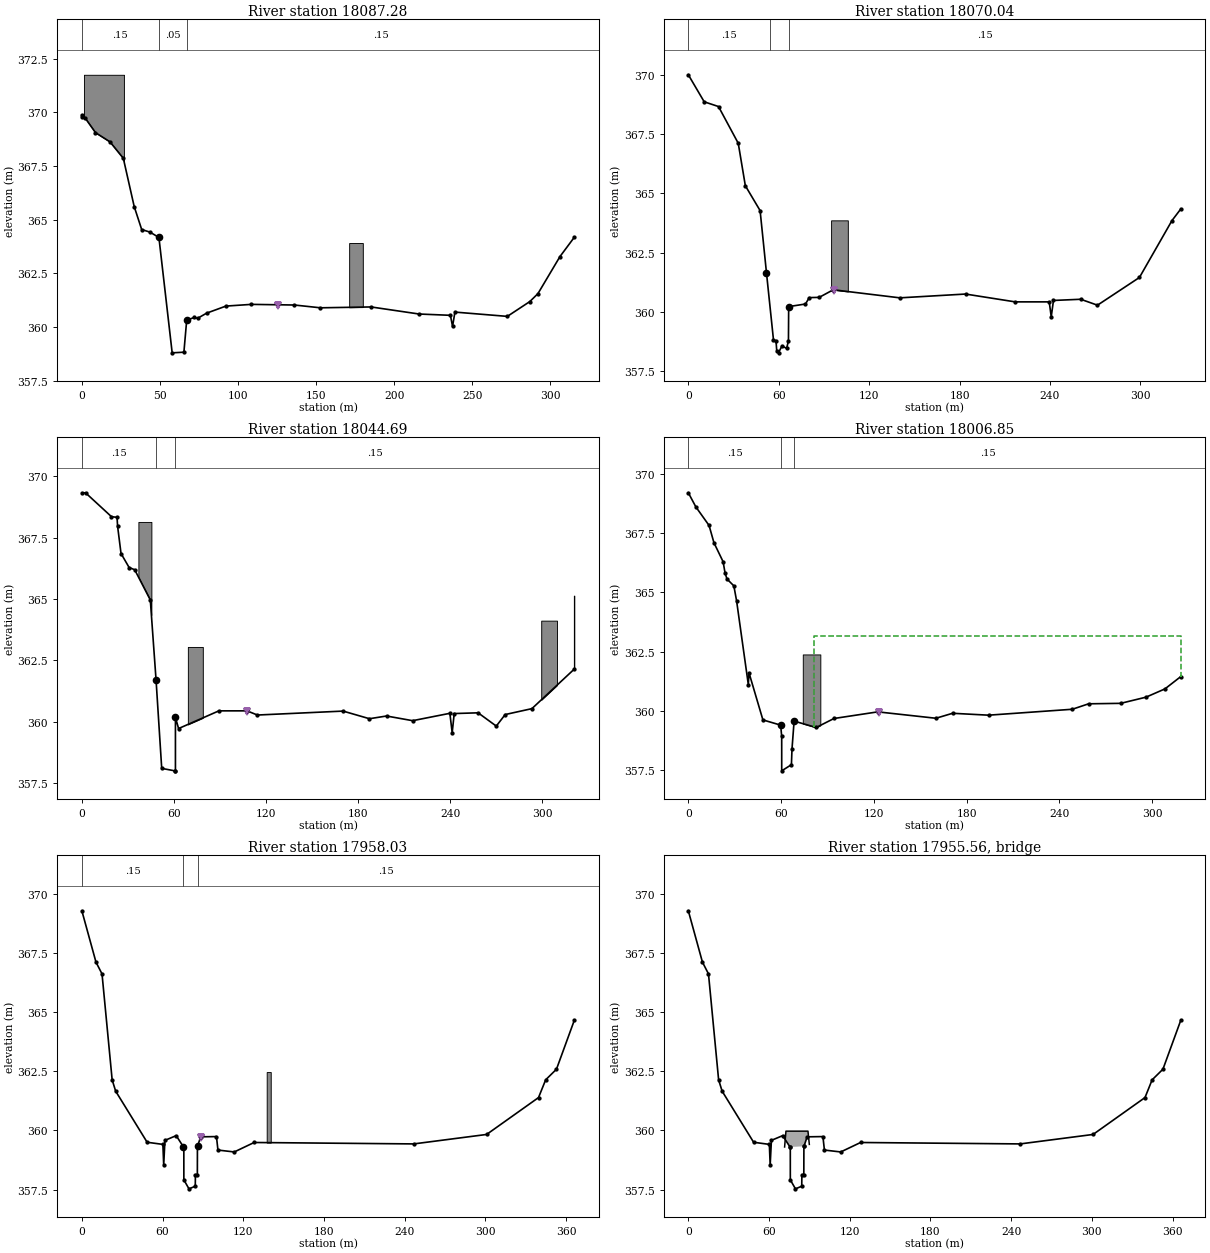
Type RM Length L Ch R = 1 ,18087.28,17.9,17.24,16.41
XS GIS Cut Line= 4
    -609172.6953   -1045075.7374-609210.22019999   -1045033.9658
    -609225.4338   -1045014.7835-609349.78819999   -1044815.6841
#Sta/Elev= 30
       0  369.87     .34  369.79     1.9  369.76    8.72  369.06   17.99  368.63
   26.56  367.86   33.53  365.61   38.32  364.54   43.62  364.42   49.35  364.17
   57.84  358.79   65.35  358.82   67.14  360.31   71.92  360.44   74.13   360.4
   79.88  360.64   92.26  360.97  108.58  361.05  136.13  361.02  152.81  360.89
   185.2  360.93  215.99   360.6  236.03  360.54   237.4  360.02  238.91  360.69
  272.48  360.49  286.86  361.18  292.07  361.55  306.19  363.28  315.38  364.18
#Mann= 3 , 0 , 0
       0     .15       0   49.35     .05       0   67.14     .15       0
Levee=0,,,-1,125.52,360.98,,
#Block Obstruct= 2 ,-1
    1.34   26.94371.7567  171.18  179.93363.9105
Bank Sta=49.35,67.14
XS Rating Curve= 0 ,0
Exp/Cntr=0.3,0.1

Type RM Length L Ch R = 1 ,18070.04,26.03,25.34,24.56
XS GIS Cut Line= 4
    -609188.4695   -1045088.7556-609221.08839999   -1045048.4074
    -609233.1209    -1045032.432    -609365.3255   -1044814.4483
#Sta/Elev= 30
       0     370   10.54  368.86   20.03  368.66   33.14  367.11   37.84  365.32
   47.64  364.27   51.88  361.64   56.53  358.81   58.19  358.78    58.7  358.34
   59.86  358.27   62.11  358.56   65.23  358.46   66.45  358.77    66.6  360.22
   77.76  360.33   80.25   360.6   86.85  360.61   96.19  360.93  140.38  360.59
  183.97  360.75  216.94  360.42  239.52  360.42  240.85  359.79  242.33  360.48
  260.41  360.53  271.53  360.28  299.39  361.45  320.98  363.85  326.83  364.34
#Mann= 3 ,-1 , 0
       0     .15       0    53.9     .05       0   66.61     .15       0
Levee=0,,,-1,96.59,360.86,,
#Block Obstruct= 1 ,-1
   94.75  105.86363.8593
Bank Sta=51.88,66.6
XS Rating Curve= 0 ,0
Exp/Cntr=0.3,0.1

Type RM Length L Ch R = 1 ,18044.69,39.68,37.85,34.98
XS GIS Cut Line= 4
    -609211.3246   -1045101.1375    -609241.9703   -1045063.7315
    -609258.5068   -1045037.9345    -609384.8456   -1044831.5591
#Sta/Elev= 30
       0  369.31    2.39  369.32   19.27  368.35   22.94  368.32   23.29  367.96
   25.53  366.85   30.81  366.28   34.45  366.19   44.62  364.96   48.36  361.71
   52.05  358.11   60.57  358.01   60.99  358.01      61  360.18   63.04  359.73
   89.32  360.45  107.65  360.45   114.4  360.28  170.26  360.44  187.43  360.13
  198.58  360.24  215.58  360.05  239.86  360.35  241.36  359.56  242.68  360.34
  258.25  360.37  270.11  359.83  275.91   360.3  293.32  360.54  320.97  362.15
#Mann= 3 , 0 , 0
       0     .15       0   48.36     .05       0      61     .15       0
Levee=0,,,-1,107.71,360.41,,
#Block Obstruct= 4 ,-1
   36.85   45.32 368.134   69.09   78.84363.0494  299.39  309.67364.1195
  320.66  320.97365.1357
Bank Sta=48.36,61
XS Rating Curve= 0 ,0
Exp/Cntr=0.3,0.1

Type RM Length L Ch R = 1 ,18006.85,47.57,48.82,45.88
XS GIS Cut Line= 4
-609249.95389999   -1045127.0667-609280.33489999   -1045075.6377
    -609281.6579   -1045067.0388    -609407.3352   -1044850.7415
#Sta/Elev= 30
       0  369.21    4.91  368.61   13.43  367.83   16.58   367.1    22.5   366.3
   23.75  365.83      25  365.57   29.46  365.28   31.22  364.65   38.82  361.11
   39.25  361.61   48.26  359.62   59.73   359.4   60.41  358.92   60.42  357.47
    66.7  357.73   67.07  358.39   68.43  359.57   82.73   359.3   94.22  359.68
  122.56  359.96  160.18  359.69  170.96   359.9  194.24  359.82  248.41  360.07
  258.94   360.3  279.72  360.32  296.07  360.58  308.35  360.93  318.59  361.45
#Mann= 3 , 0 , 0
       0     .15       0   59.73     .05       0   68.43     .15       0
Levee=0,,,-1,123.07,359.93,,
#XS Ineff= 2 , 0
                           81.24          363.15
Permanent Ineff=
       F       F
#Block Obstruct= 1 ,-1
   74.05    85.4362.3846
Bank Sta=59.73,68.43
XS Rating Curve= 0 ,0
Exp/Cntr=0.3,0.1

Type RM Length L Ch R = 1 ,17958.03,4.98,4.96,5.01
XS GIS Cut Line= 5
-609289.07889999   -1045149.6626    -609326.2672   -1045090.5068
    -609331.3531   -1045071.1643-609362.16739999   -1045001.6811
     -609463.228   -1044828.8855
#Sta/Elev= 30
       0  369.29   10.49  367.12   14.99  366.62   22.52  362.14   25.14  361.66
   48.53   359.5   60.23  359.41   60.84  358.54   61.76  359.58   70.13  359.78
   75.55 359.302    75.8   359.3   75.82  357.91   79.63  357.53    84.3  357.64
   84.42  358.13   85.85  358.13   85.91  359.33   86.02359.3391   88.33  359.73
  100.05  359.74  101.16  359.17  113.29  359.09  128.04  359.49  246.69  359.43
  300.86  359.83  339.45  361.39  344.75  362.14  352.79  362.59  366.06  364.66
#Mann= 3 ,-1 , 0
       0     .15       0   75.55     .04       0   86.02     .15       0
Levee=0,,,-1,88.68,359.7,,
#XS Ineff= 2 , 0
           63.35  359.53
Permanent Ineff=
       F       F
#Block Obstruct= 1 ,-1
   137.4   140.4362.4691
Bank Sta=75.55,86.02
XS Rating Curve= 0 ,0
Exp/Cntr=0.5,0.3

Type RM Length L Ch R = 3 ,17955.56,,,
BEGIN DESCRIPTION:
18151.9  PF 234 NOVÝ SILNIÈNÍ ŽLB MOST 1999 V
END DESCRIPTION:
Bridge Culvert--1,0,-1,-1, 0
Deck Dist Width WeirC Skew NumUp NumDn MinLoCord MaxHiCord MaxSubmerge Is_Ogee
0.3,4.6,1.4,0, 6, 6, , , 0.98, 0, 0,0,,
   71.57   72.57   76.05   86.02   88.94   89.94
   359.3  359.97  359.97  359.97  359.97  359.41
   359.3   359.3   359.3  359.33  359.33  359.41
   71.57   72.57   76.05   86.02   88.94   89.94
   359.3  359.97  359.97  359.97  359.97  359.41
   359.3   359.3   359.3  359.33  359.33  359.41
BR Coef=-1 , 0 , 0 ,, 0 ,,,0.8,-1,,0,
WSPro=,,,, 1 ,,,, 0 ,,,, 0 ,,,,-1 ,-1 ,-1 , 0 , 0 , 0 , 0 , 0
BC Design=,, 0 ,, 0 ,,,,,,
BC Use User HTab Curves=0
BC User HTab FreeFlow(D)= 0

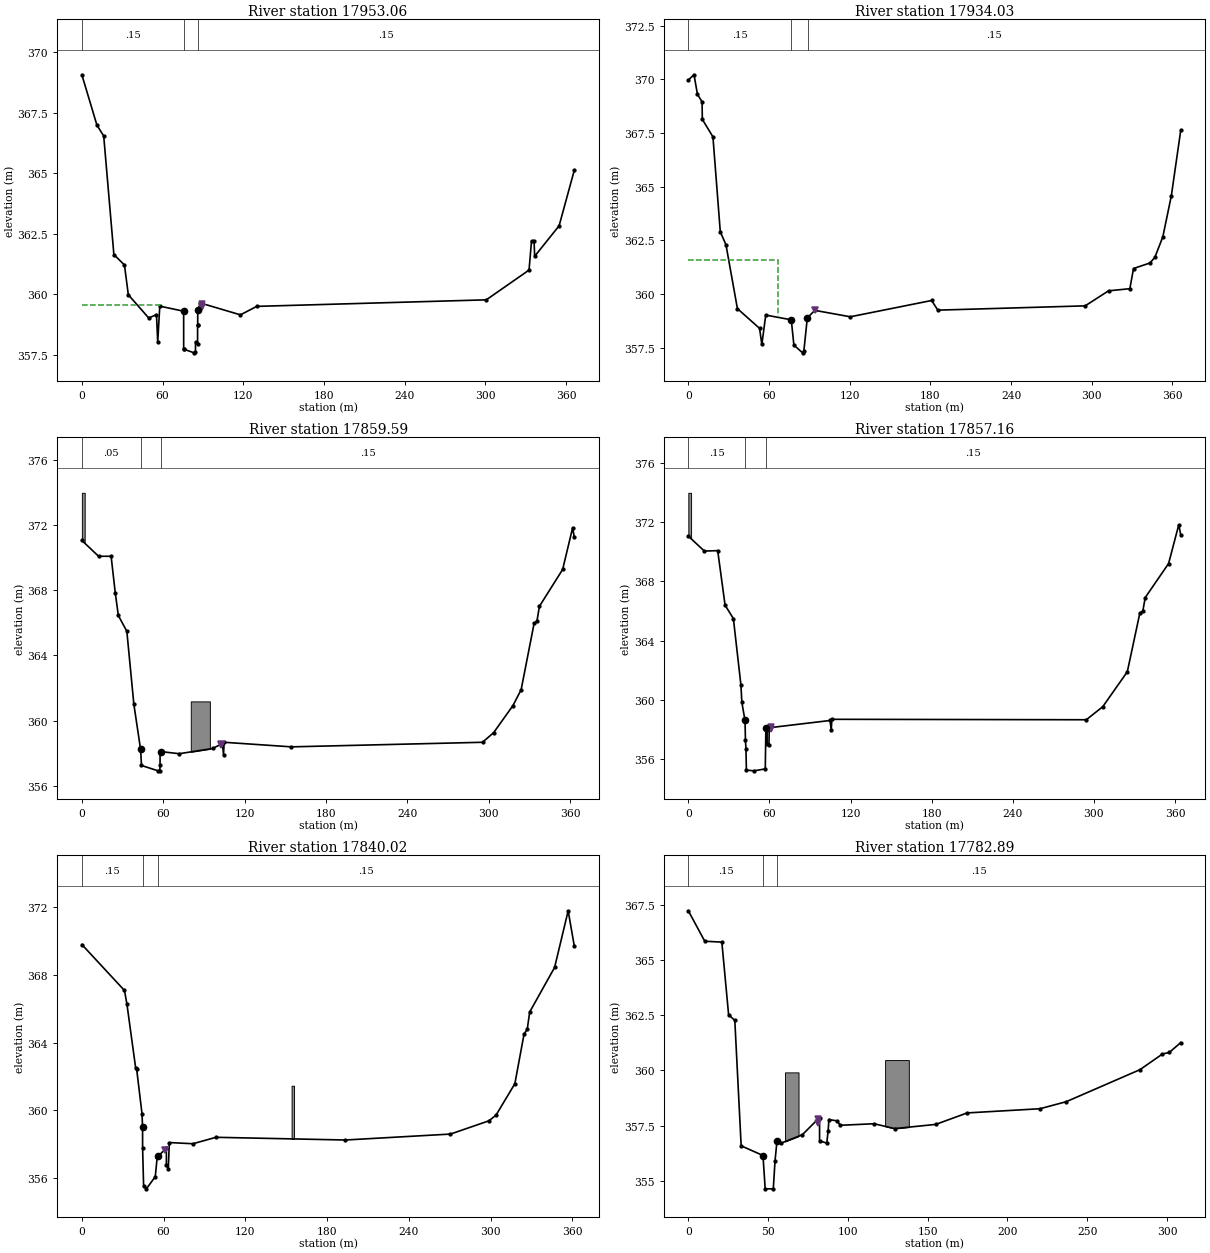
Type RM Length L Ch R = 1 ,17953.06,18.09,19.04,21.99
XS GIS Cut Line= 5
    -609293.7773   -1045151.3166    -609330.9657   -1045092.1607
    -609336.0515   -1045072.8183    -609366.8658   -1045003.3351
-609467.92639999   -1044830.5395
#Sta/Elev= 30
       0  369.07    11.2  366.99   16.25  366.54   23.81  361.64   31.67  361.21
   34.54  359.98   49.71  359.02   55.47  359.16   56.39  358.03   57.93  359.51
   75.67   359.3   75.68  357.75   75.77  357.73   83.46  357.58   84.45  357.61
   84.51  358.04   86.02  357.94   86.03  358.73   86.12  358.74   86.13  359.33
   88.09  359.64  117.88  359.15     130   359.5  300.62  359.77  332.39     361
  334.26  362.21  336.13  362.19  336.58  361.57  354.75  362.83  366.06  365.13
#Mann= 3 , 0 , 0
       0     .15       0   75.67     .04       0   86.13     .15       0
Levee=0,,,-1,89.61,359.48,,
#XS Ineff= 2 , 0
           58.64  359.55
Permanent Ineff=
       F       F
Bank Sta=75.67,86.13
XS Rating Curve= 0 ,0
Exp/Cntr=0.5,0.3

Type RM Length L Ch R = 1 ,17934.03,65.98,74.44,72.11
XS GIS Cut Line= 5
    -609319.7439   -1045164.6074-609346.21489999    -1045097.348
    -609356.5102   -1045080.2014-609385.44929999   -1045009.9555
    -609484.1037    -1044838.313
#Sta/Elev= 30
       0  369.98    4.24  370.22     6.8  369.31   10.23  368.96   10.42  368.14
    18.3  367.33   23.78   362.9   27.99   362.3   36.51  359.32   52.99   358.4
   54.67  357.65   57.58  359.02   76.56   358.8   78.51  357.62   84.98  357.26
   85.93  357.35   88.49  358.89   94.07  359.24  120.45  358.94  180.97   359.7
   185.5  359.25  295.12  359.45   312.5  360.15  328.34  360.25  331.09  361.19
  343.38  361.45  347.01  361.72  352.88  362.67   359.2  364.58  366.23  367.65
#Mann= 3 ,-1 , 0
       0     .15       0   76.56     .04       0    88.7     .15       0
Levee=0,,,-1,94.23,359.25,,
#XS Ineff= 2 , 0
           66.97  361.58
Permanent Ineff=
       F       F
Bank Sta=76.56,88.49
XS Rating Curve= 0 ,0
Exp/Cntr=0.3,0.1

Type RM Length L Ch R = 1 ,17859.59,2.45,2.42,1.42
XS GIS Cut Line= 5
-609388.34189999    -1045182.943     -609396.089   -1045144.6568
    -609410.8528    -1045136.243-609421.27679999   -1045089.5522
-609541.73739999   -1044859.9101
#Sta/Elev= 30
       0  371.05   12.33  370.08   21.59  370.08   24.63  367.84   26.91  366.45
   33.18  365.48   38.37     361   43.32  358.24   43.98  357.26   56.23  356.93
   57.52  356.95   57.67  357.31    57.7  358.11   58.31  358.11   71.77  357.98
   96.51   358.3  103.64  358.61  104.48  357.93  104.97  358.68  154.54   358.4
  295.51  358.68  303.69  359.27  317.87  360.92  323.98   361.9  333.53  365.96
  335.64   366.1  337.44  367.01  354.59  369.27  361.94  371.82  363.21  371.23
#Mann= 3 , 0 , 0
       0     .05       0   43.32     .05       0   58.31     .15       0
Levee=0,,,-1,102.77,358.5,,
#Block Obstruct= 2 ,-1
       0     2.1373.9706   80.33   94.41361.1868
Bank Sta=43.32,58.31
XS Rating Curve= 0 ,0
Exp/Cntr=0.3,0.1

Type RM Length L Ch R = 1 ,17857.16,23.71,17.14,11.38
XS GIS Cut Line= 6
    -609389.2674   -1045183.2983-609397.27959999   -1045146.3236
-609413.71029999   -1045137.2749    -609412.9959   -1045133.7824
-609422.20239999   -1045089.9074    -609542.6629   -1044860.2654
#Sta/Elev= 30
       0  371.05   11.88  370.04   21.73  370.07   27.19  366.39   33.34  365.48
   38.94  360.97   39.59  359.83   41.94   358.6   42.26  357.26   42.66  356.66
   42.95  355.25   48.54   355.2   56.92  355.33   57.37  358.08   58.25  357.99
   58.31  357.04   59.65  356.96   59.87  358.11  104.85   358.6   105.7  357.95
  106.21  358.68  294.39  358.65  306.56  359.53  324.74  361.89     334  365.85
   336.2  365.98  337.98   366.9  355.28   369.2  362.81  371.82   364.3  371.12
#Mann= 3 , 0 , 0
       0     .15       0   41.94     .05       0   57.37     .15       0
Levee=0,,,-1,61.43,358.04,,
#Block Obstruct= 1 ,-1
       0    2.05373.9771
Bank Sta=41.94,57.37
XS Rating Curve= 0 ,0
Exp/Cntr=0.3,0.1

Type RM Length L Ch R = 1 ,17840.02,57.92,57.13,54.77
XS GIS Cut Line= 6
-609414.96049999    -1045194.222    -609420.4036   -1045157.2118
-609423.78489999   -1045137.4997    -609430.7512   -1045104.4406
    -609461.8814    -1045044.887    -609553.0165   -1044863.5194
#Sta/Elev= 30
       0  369.78   31.27  367.07   33.07  366.27   39.48   362.5   40.23  362.42
   44.13  359.81   44.54  359.04   44.59  357.75   45.31  355.55   47.35  355.37
   53.89  356.09   55.31  357.26   55.77  357.28   62.02  357.77   62.03  356.76
   63.43  356.55   64.18   358.1   81.51  358.03   98.41  358.41   193.3  358.25
   270.5   358.6  298.63  359.38  303.86  359.71  317.73  361.57  324.51  364.51
   326.8  364.77  328.62   365.8  346.91  368.43  356.85  371.77  361.37  369.68
#Mann= 3 , 0 , 0
       0     .15       0   44.54     .05       0   55.77     .15       0
Levee=0,,,-1,60.97,357.69,,
#Block Obstruct= 1 ,-1
   153.9  155.72361.4517
Bank Sta=44.54,55.77
XS Rating Curve= 0 ,0
Exp/Cntr=0.3,0.1

Type RM Length L Ch R = 1 ,17782.89,62.55,62.87,61.97
XS GIS Cut Line= 4
    -609470.8038    -1045197.095-609477.57719999    -1045171.695
    -609480.4835   -1045126.6469    -609575.3674   -1044909.2278
#Sta/Elev= 30
       0  367.23   10.31  365.85   21.01  365.81   25.25  362.52   29.14  362.26
   33.12  356.58   46.79  356.14   48.18  354.63   53.26  354.63   54.36  355.91
   55.59  356.81   58.12   356.7   71.43  357.08   82.25  357.86   82.26  356.81
   86.78   356.7   87.64  357.27   88.13  357.77   93.12  357.71   95.37  357.51
  116.46  357.58  129.29  357.36  155.07  357.55  174.76  358.07  220.41  358.26
  236.89  358.58  283.05  360.03  297.17  360.74  301.47  360.81  308.65  361.26
#Mann= 3 , 0 , 0
       0     .15       0   46.79     .05       0   55.59     .15       0
Levee=0,,,-1,81.03,357.6,,
#Block Obstruct= 2 ,-1
  123.33   138.2360.4653   60.62   69.08 359.908
Bank Sta=46.79,55.59
XS Rating Curve= 0 ,0
Exp/Cntr=0.3,0.1

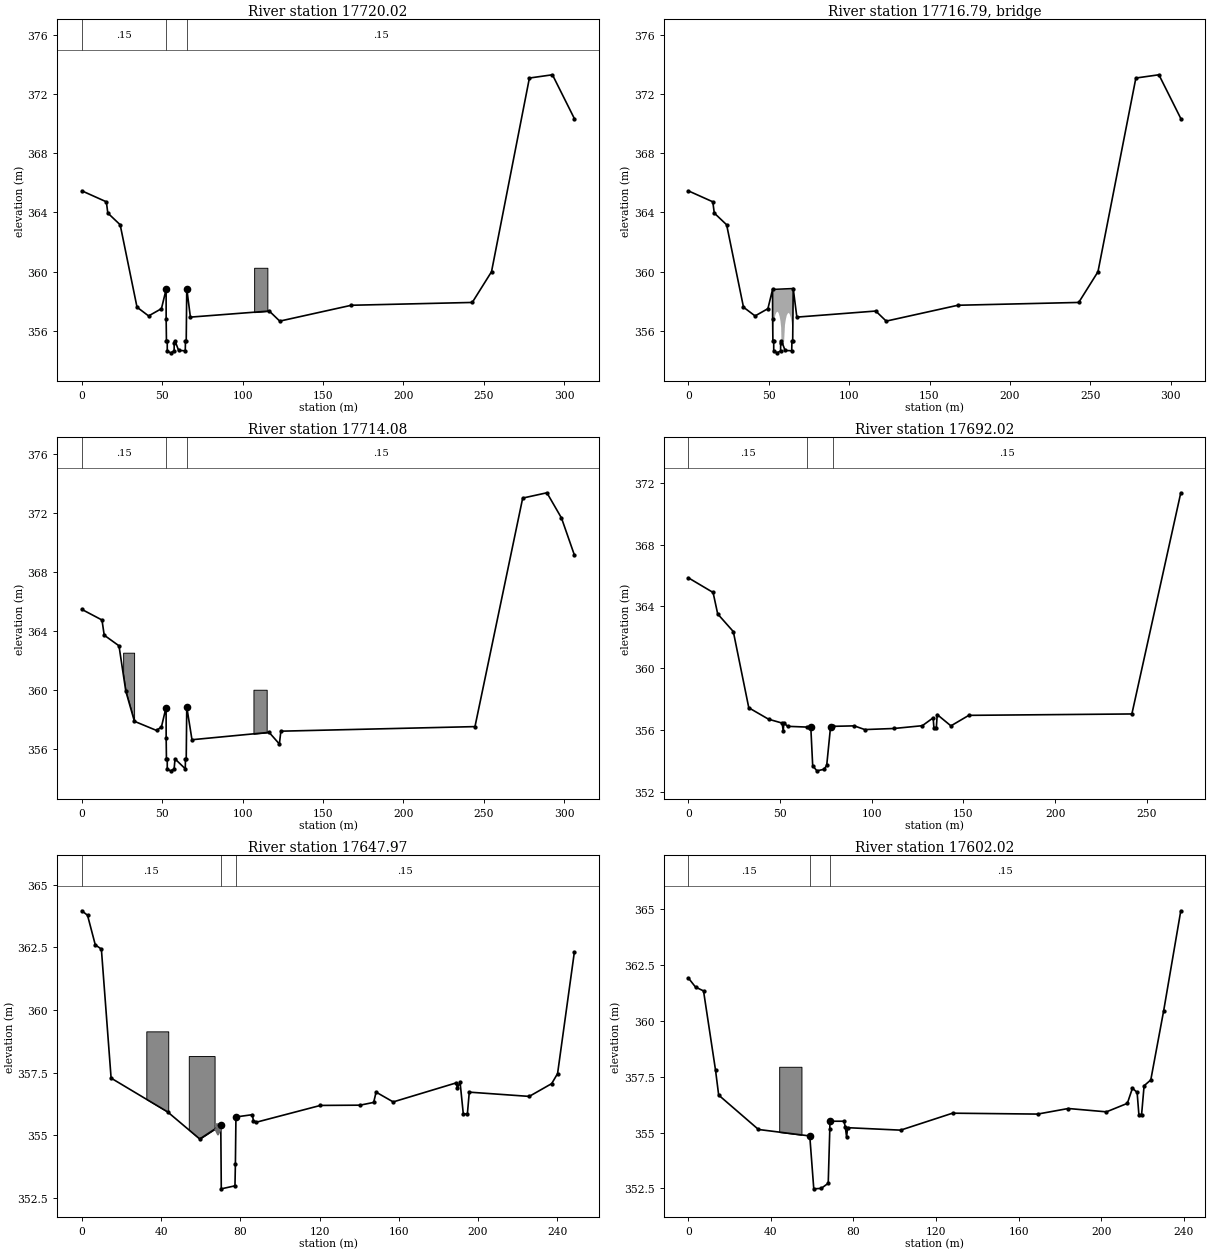
Type RM Length L Ch R = 1 ,17720.02,5.95,5.94,5.93
XS GIS Cut Line= 6
-609530.90949999   -1045209.5616-609540.83509999   -1045177.0778
     -609541.896   -1045141.5778    -609542.1886   -1045093.1615
    -609613.9235   -1044959.6171    -609631.9701   -1044927.5846
#Sta/Elev= 30
       0  365.46   15.22  364.72   16.15  363.96   23.83  363.17   34.31  357.61
   41.52  357.02    49.5  357.51    52.4  358.81   52.43  356.79   52.61  355.32
   53.11  355.32   53.12  354.64   55.31  354.53   57.39  354.66   57.44  355.22
   57.94  355.34   60.19  354.69   64.31  354.67   64.44  355.31   64.91  355.32
   65.24  358.87    67.5  356.94  116.56  357.35  123.08  356.67  167.63  357.74
  242.81  357.93  254.77     360  278.34  373.07  292.67  373.29  306.28  370.34
#Mann= 3 , 0 , 0
       0     .15       0    52.4     .04       0   65.24     .15       0
#Block Obstruct= 1 ,-1
  107.15  115.38360.2692
Bank Sta=52.4,65.24
XS Rating Curve= 0 ,0
Exp/Cntr=0.5,0.3

Type RM Length L Ch R = 3 ,17716.79,,,
BEGIN DESCRIPTION:
17913.9  PF 230 SILNIÈNÍ KAMENNÝ KLENBOVÝ
END DESCRIPTION:
Bridge Culvert--1,0,-1,-1, 0
Deck Dist Width WeirC Skew NumUp NumDn MinLoCord MaxHiCord MaxSubmerge Is_Ogee
0.5,5.3,1.4,0, 26, 26, , , 0.98, 0, 0,0,,
    52.4   52.61  52.837   53.14  53.614  54.222  54.899   55.31  56.097  56.757
  57.305   57.73   57.94   59.57  60.108  60.582  61.175  61.749   62.43   63.09
  63.704  64.262  64.548   64.91   65.05   65.24
  358.81  358.81 358.811 358.813 358.815 358.818 358.821 358.823 358.827  358.83
 358.833 358.835 358.836 358.844 358.847 358.849 358.852 358.855 358.858 358.861
 358.864 358.867 358.868  358.87  358.87  358.87
  355.32  355.32 356.038 356.414  356.83 357.122  357.27  357.31 357.232  356.99
 356.678 356.244  355.34  355.28 356.394 356.742 357.034 357.166  357.23  357.13
 356.924   356.6 356.322  355.32  356.83  356.83
    52.4   52.61  52.837   53.14  53.614  54.222  54.899   55.31  56.097  56.757
  57.305   57.73   57.94   59.57  60.108  60.582  61.175  61.749   62.43   63.09
  63.704  64.262  64.548   64.91   65.05   65.24
  358.81  358.81 358.811 358.813 358.815 358.818 358.821 358.823 358.827  358.83
 358.833 358.835 358.836 358.844 358.847 358.849 358.852 358.855 358.858 358.861
 358.864 358.867 358.868  358.87  358.87  358.87
  355.32  355.32 356.038 356.414  356.83 357.122  357.27  357.31 357.232  356.99
 356.678 356.244  355.34  355.28 356.394 356.742 357.034 357.166  357.23  357.13
 356.924   356.6 356.322  355.32  356.83  356.83
BR Coef=-1 , 0 , 0 ,, 0 ,,,0.8,-1,,0,
WSPro=,,,, 1 ,,,, 0 ,,,, 0 ,,,,-1 ,-1 ,-1 , 0 , 0 , 0 , 0 , 0
BC Design=,, 0 ,, 0 ,,,,,,
BC Use User HTab Curves=0
BC User HTab FreeFlow(D)= 0

Type RM Length L Ch R = 1 ,17714.08,18.94,22.06,22.37
XS GIS Cut Line= 6
    -609536.8314   -1045209.0995-609546.75699999   -1045176.6156
    -609547.8178   -1045141.1156-609548.11039999   -1045092.6994
    -609619.8454   -1044959.1549     -609637.892   -1044927.1225
#Sta/Elev= 30
       0  365.48   12.52  364.76   13.91  363.73    23.1  363.01   27.34  359.93
   32.69  357.89   46.43  357.27    49.5  357.51   52.32  358.81    52.4  358.81
   52.43  356.79   52.61  355.32   53.11  355.32   53.12  354.64   55.31  354.53
   57.39  354.66   57.94  355.34   64.31  354.67   64.44  355.31   64.91  355.32
   65.24  358.87   68.49  356.64  116.46  357.14  122.85  356.35  123.77  357.22
  244.49  357.53  274.17  373.03  289.23  373.39  298.29  371.68  306.28  369.18
#Mann= 3 , 0 , 0
       0     .15       0   52.32    .045       0   65.24     .15       0
#Block Obstruct= 2 ,-1
   25.68    32.5362.5436  106.72  114.95360.0309
Bank Sta=52.32,65.24
XS Rating Curve= 0 ,0
Exp/Cntr=0.5,0.3

Type RM Length L Ch R = 1 ,17692.02,41.2,44.05,46.63
XS GIS Cut Line= 6
-609544.89559999   -1045215.8779-609568.07849999   -1045159.3655
-609569.86809999   -1045139.4457    -609584.1468   -1045094.0638
-609585.04899999   -1045083.2359-609645.95609999   -1044969.5427
#Sta/Elev= 30
       0  365.85    13.5   364.9   16.02  363.51   24.53  362.37   32.97  357.44
   43.75   356.7   51.15  356.45   51.73  355.95   52.11  356.46   54.11  356.24
   64.97  356.19   66.77  356.21   67.81  353.69   70.12  353.36   74.01  353.46
   75.45  353.71   77.54   356.2   79.15  356.24   90.46  356.27   96.21  356.03
   112.1   356.1  127.58  356.28  133.49  356.79  133.91  356.12   135.2  356.12
   135.7     357  143.17  356.27  152.93  356.95  241.83  357.04   268.5  371.35
#Mann= 3 ,-1 , 0
       0     .15       0   64.97    .045       0   79.15     .15       0
Bank Sta=66.77,77.54
XS Rating Curve= 0 ,0
Exp/Cntr=0.3,0.1

Type RM Length L Ch R = 1 ,17647.97,44.69,45.95,47.64
XS GIS Cut Line= 4
-609585.52739999   -1045225.4584-609605.14359999   -1045175.1529
-609621.57099999    -1045133.065    -609680.7776   -1044995.7996
#Sta/Elev= 30
       0  363.96    2.87  363.78    6.78   362.6    9.86  362.43   14.77  357.28
   43.32  355.93   59.51  354.85   70.15   355.4    70.4  352.86   77.31  352.98
   77.53  353.86    77.8  355.73   86.09  355.82   86.61  355.58   88.12  355.52
  120.47  356.19  140.44   356.2  147.34  356.31  148.56  356.72   157.2  356.33
  189.04  357.09  189.57  356.89  190.98  357.11   192.6  355.85  194.66  355.85
  195.62  356.72  225.89  356.55  237.22  357.06   240.2  357.46  248.66   362.3
#Mann= 3 , 0 , 0
       0     .15       0   70.15    .043       0    77.8     .15       0
Levee=-1,68.56,355.13,0,,,,
#Block Obstruct= 2 ,-1
   32.55   43.62359.1464   53.99   67.02358.1605
Bank Sta=70.15,77.8
XS Rating Curve= 0 ,0
Exp/Cntr=0.3,0.1

Type RM Length L Ch R = 1 ,17602.02,44.99,45.33,43.77
XS GIS Cut Line= 4
    -609628.5299    -1045233.445-609649.70439999   -1045183.4506
    -609659.3708   -1045165.9417    -609730.4928    -1045017.789
#Sta/Elev= 30
       0  361.93     3.5  361.52    7.37  361.35   13.18   357.8   14.71  356.68
   33.99  355.14   58.85  354.85   60.79  352.48    64.4   352.5   67.79  352.73
   68.56  355.16   68.63  355.51   75.39  355.51   76.07  355.26   76.69   354.8
   77.19  355.22  102.87  355.11  128.03  355.87  169.26  355.83  184.11  356.08
   202.6  355.93  212.73  356.31   215.2  356.99  217.47   356.8  218.32  355.81
  219.64  355.81  220.85   357.1  224.09  357.36  230.35  360.47  238.63  364.94
#Mann= 3 ,-1 , 0
       0     .15       0   58.85     .04       0   68.66     .15       0
#Block Obstruct= 1 ,-1
   44.03   54.82357.9499
Bank Sta=58.85,68.63
XS Rating Curve= 0 ,0
Exp/Cntr=0.3,0.1