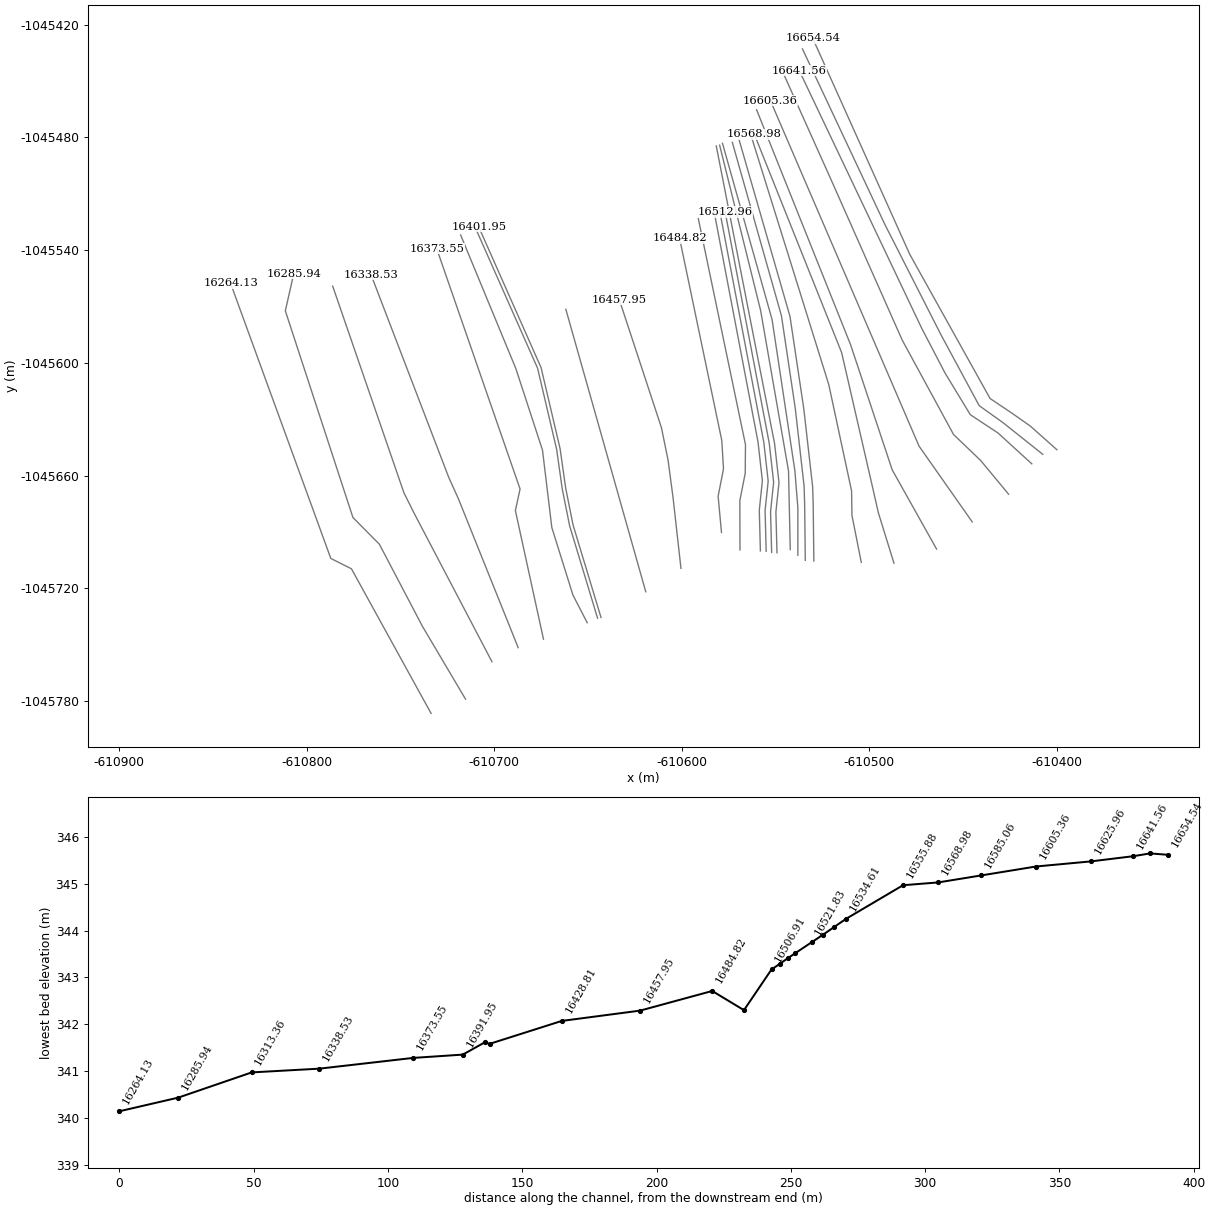
HEC-RAS study PPO_Kvasiny_efektiv.prj: PPO_Kvasiny_efektivita

--- PPO_Kvasiny_efektiv.g15 (geometry) --- (continued)

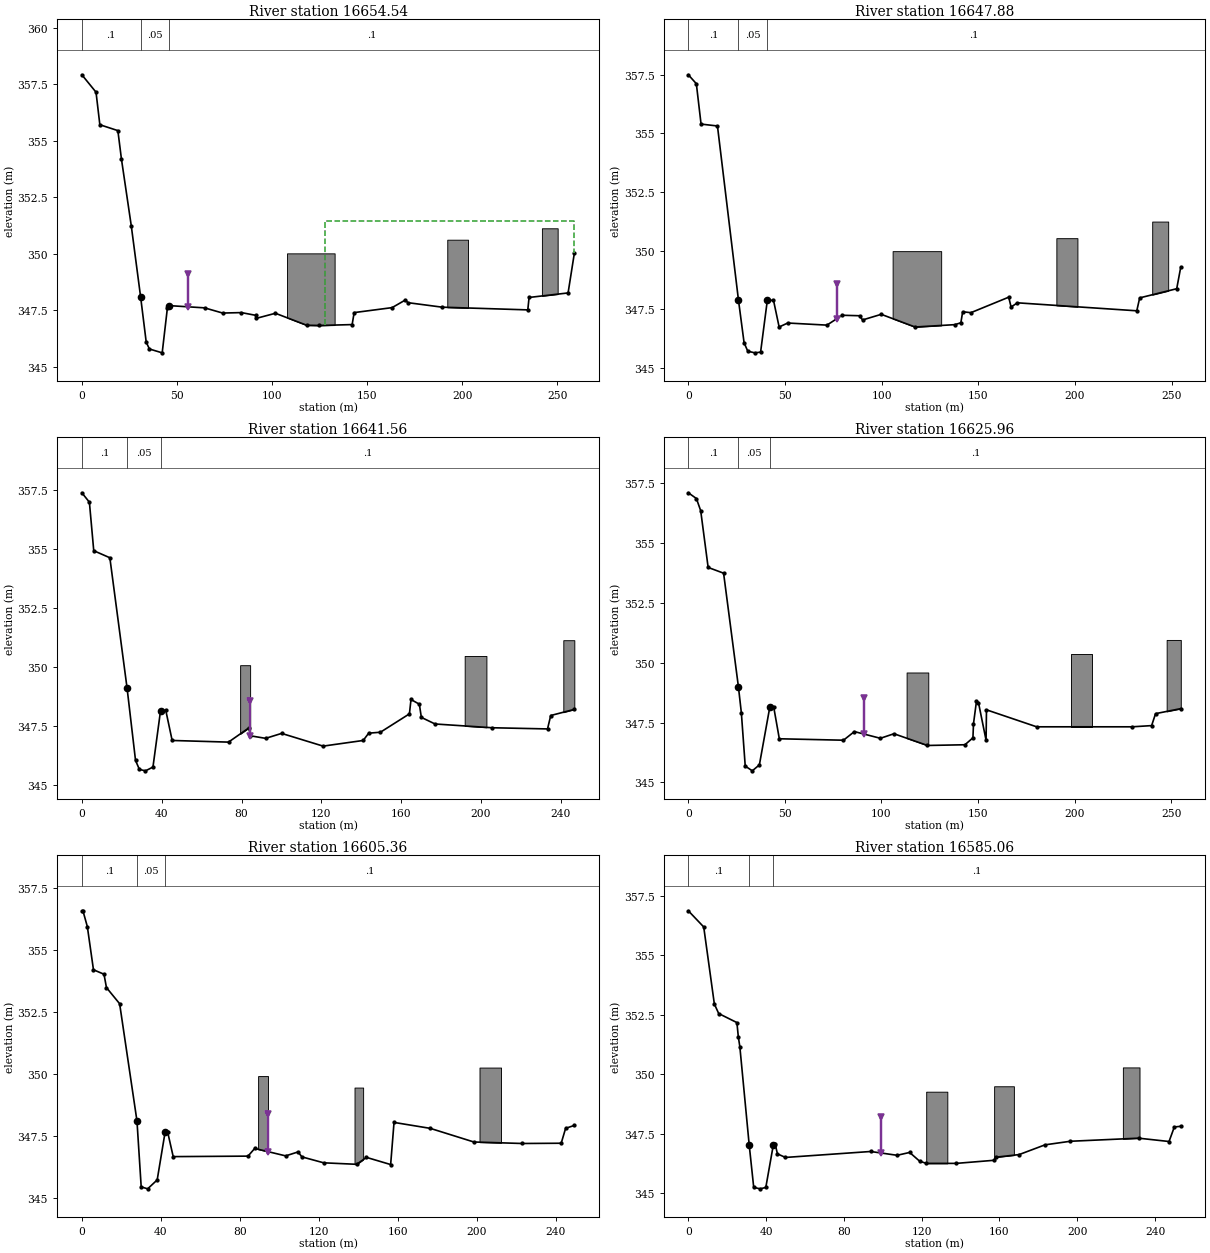
Type RM Length L Ch R = 1 ,16654.54,6.93,6.66,6.8
XS GIS Cut Line= 6
     -610399.919   -1045646.2163-610414.10069999   -1045633.6221
    -610423.8823   -1045626.7642    -610435.5652   -1045618.9463
    -610478.4107   -1045542.1985    -610530.1288   -1045427.2973
#Sta/Elev= 30
       0  357.92    7.45  357.15    9.46  355.71   18.93  355.45   20.83  354.18
   25.96  351.25   30.91  348.08   33.84  346.09   35.52  345.79   42.23  345.62
   44.97  347.61   45.65  347.71    64.5  347.61   74.01  347.38   83.87   347.4
   91.33  347.28   91.45  347.14  101.75  347.37  118.19  346.84  124.78  346.83
  142.08  346.87  143.13   347.4  163.07  347.62  170.12  347.96  171.35  347.84
  189.38  347.64  234.41  347.52  235.09  348.07  255.59  348.27  258.87  350.02
#Mann= 3 , 0 , 0
       0      .1       0   30.91     .05       0   45.65      .1       0
Levee=0,,,-1,55.88,349.1129,,	2161
#XS Ineff= 2 , 0
                          127.66          351.43
Permanent Ineff=
       F       F
#Block Obstruct= 3 ,-1
  241.83  250.11351.1296  192.08  202.98 350.625  107.84  132.87350.0207
Bank Sta=30.91,45.65
XS Rating Curve= 0 ,0
Exp/Cntr=0.3,0.1

Type RM Length L Ch R = 1 ,16647.88,5.99,6.32,7.53
XS GIS Cut Line= 6
-610407.45239999   -1045648.6625    -610428.5344   -1045631.8985
-610441.36149999   -1045622.7545-610461.68149999   -1045585.1624
    -610491.7806   -1045526.1073-610535.63219999   -1045432.9065
#Sta/Elev= 30
       0  357.49    4.15  357.11    6.59  355.39   15.07  355.31   25.93   347.9
   28.84  346.08   30.75  345.72   34.39  345.65   37.38  345.68   40.85  347.88
   44.05  347.89   46.97  346.75   51.41  346.92   71.69  346.83   79.54  347.25
   88.55  347.23   90.11  347.05   99.78  347.29  117.27  346.75  137.81  346.85
  140.96  346.93  141.89   347.4  146.14  347.36  165.71  348.02  166.93   347.6
  170.19  347.78  231.94  347.44  233.44  347.99  252.59  348.38   254.7  349.31
#Mann= 3 , 0 , 0
       0      .1       0   25.93     .05       0   40.85      .1       0
Levee=0,,,-1,76.74,348.5952,,	2159
#XS Ineff= 2 , 0
       0                   42.13       0  347.55
Permanent Ineff=
       F       T
#Block Obstruct= 3 ,-1
  105.66  130.77  349.98  190.35  201.24350.5325  239.91  248.18351.2398
Bank Sta=25.93,40.85
XS Rating Curve= 0 ,0
Exp/Cntr=0.3,0.1

Type RM Length L Ch R = 1 ,16641.56,17.07,15.6,12.26
XS GIS Cut Line= 6
-610413.30689999   -1045653.7066-610431.29479999   -1045637.3368
-610446.09189999    -1045627.568    -610459.5562   -1045605.4465
    -610472.0445   -1045581.5282    -610537.3255   -1045444.4423
#Sta/Elev= 30
       0   357.4    3.78     357    5.96  354.94   14.03  354.64   22.68  349.09
    26.9  346.03   28.84  345.65   31.89  345.59   35.63  345.75   39.44  348.15
   42.05  348.16   45.25  346.88   73.49  346.81   83.79  347.42   84.32  347.08
   92.09  346.97   100.1  347.18  120.88  346.64  140.97  346.88  143.73  347.19
  149.61  347.23  164.14  348.01  164.93  348.62  169.11  348.42  170.12  347.86
  176.98  347.58  205.67  347.42  233.34  347.37  234.95  347.94  246.77   348.2
#Mann= 3 , 0 , 0
       0      .1       0   22.68     .05       0   39.44      .1       0
Levee=0,,,-1,84.49,348.5743,,	2159
#XS Ineff= 2 , 0
       0                    41.8       0   347.5
Permanent Ineff=
       F       T
#Block Obstruct= 3 ,-1
   79.31   84.32350.0773  191.83  202.72350.4694  241.25  246.77351.1385
Bank Sta=22.68,39.44
XS Rating Curve= 0 ,0
Exp/Cntr=0.3,0.1

Type RM Length L Ch R = 1 ,16625.96,21.61,20.6,17.48
XS GIS Cut Line= 6
-610425.68789999   -1045669.8678     -610440.574   -1045651.9392
-610455.03269999   -1045638.1208     -610482.421   -1045587.8698
    -610520.3187      -1045502.6-610545.36879999   -1045446.8765
#Sta/Elev= 30
       0   357.1    4.18  356.86    6.41  356.35   10.26  353.98   18.26  353.74
   25.94  348.99   27.45  347.91   29.46  345.68   33.12  345.48   36.79  345.73
   42.22  348.16   44.24  348.13   47.11  346.82   80.33  346.76   85.96  347.12
   99.43  346.84  106.46  347.03   123.8  346.54   143.2  346.57  147.34  346.86
  147.63  347.45  149.17  348.39  150.21  348.33  154.14  346.76  154.35  348.03
  180.32  347.32  229.76  347.32  239.84  347.37  241.88  347.87  254.94  348.08
#Mann= 3 , 0 , 0
       0      .1       0   25.94     .05       0   42.22      .1       0
Levee=0,,,-1,91.1,348.5402,,	2159
#XS Ineff= 2 , 0
       0                      44       0  347.35
Permanent Ineff=
       F       T
#Block Obstruct= 3 ,-1
     113  124.22349.5901  198.32  209.22350.3801  247.62  254.94350.9503
Bank Sta=25.94,42.22
XS Rating Curve= 0 ,0
Exp/Cntr=0.3,0.1

Type RM Length L Ch R = 1 ,16605.36,21.02,20.3,16.27
XS GIS Cut Line= 3
-610445.09629999   -1045684.5852-610473.44709999   -1045644.2738
-610552.67139999    -1045460.529
#Sta/Elev= 30
       0  356.58     .55  356.59    2.78  355.95    5.88  354.21   11.21  354.03
   12.46  353.49   19.13  352.84   27.91  348.11   30.05  345.45   33.32  345.37
   38.15  345.73   42.18  347.67   43.48  347.65   46.26  346.67   84.14  346.69
   87.53     347  103.21   346.7  109.51  346.86  111.41  346.66  122.47  346.42
  139.16  346.36   144.1  346.64  156.37  346.35  158.08  348.05  176.45  347.81
  198.52  347.26  222.94   347.2  242.73  347.21  244.96  347.81  249.38  347.93
#Mann= 3 , 0 , 0
       0      .1       0   27.91     .05       0   42.18      .1       0
Levee=0,,,-1,94.36,348.3709,,	2159
#XS Ineff= 2 , 0
       0                    42.5       0  347.15
Permanent Ineff=
       F       T
#Block Obstruct= 3 ,-1
   89.25   94.26349.9202  138.07  142.43349.4565  201.36  212.27350.2634
Bank Sta=27.91,42.18
XS Rating Curve= 0 ,0
Exp/Cntr=0.3,0.1

Type RM Length L Ch R = 1 ,16585.06,17.86,16.08,10.48
XS GIS Cut Line= 4
    -610464.0819   -1045699.0756    -610487.7346   -1045656.9739
    -610509.9596   -1045590.2987    -610560.0797   -1045465.2915
#Sta/Elev= 30
       0  356.87    7.92  356.19   13.39  352.95   15.62  352.55   24.98  352.17
   25.73  351.56   26.49  351.16    31.3  347.03   33.63  345.24   36.97  345.18
   39.85  345.24   43.72  347.03   44.65  347.06   45.84  346.65   49.93   346.5
   93.75  346.75  107.37  346.59  113.82  346.71  118.99  346.34  122.48  346.25
  137.76  346.25  157.18  346.38  158.11  346.51  170.11  346.62  183.44  347.03
  196.43  347.18  231.58  347.31  247.21  347.17  249.92  347.78  253.25  347.81
#Mann= 3 , 0 , 0
       0      .1       0    31.3     .05       0   43.72      .1       0
Levee=0,,,-1,99.07,348.1866,,	2159
#XS Ineff= 2 , 0
       0                      44       0  346.85
Permanent Ineff=
       F       T
#Block Obstruct= 3 ,-1
  122.33  133.19349.2643  157.26  167.42349.4925  223.47  232.02350.2849
Bank Sta=31.3,43.72
XS Rating Curve= 0 ,0
Exp/Cntr=0.3,0.1

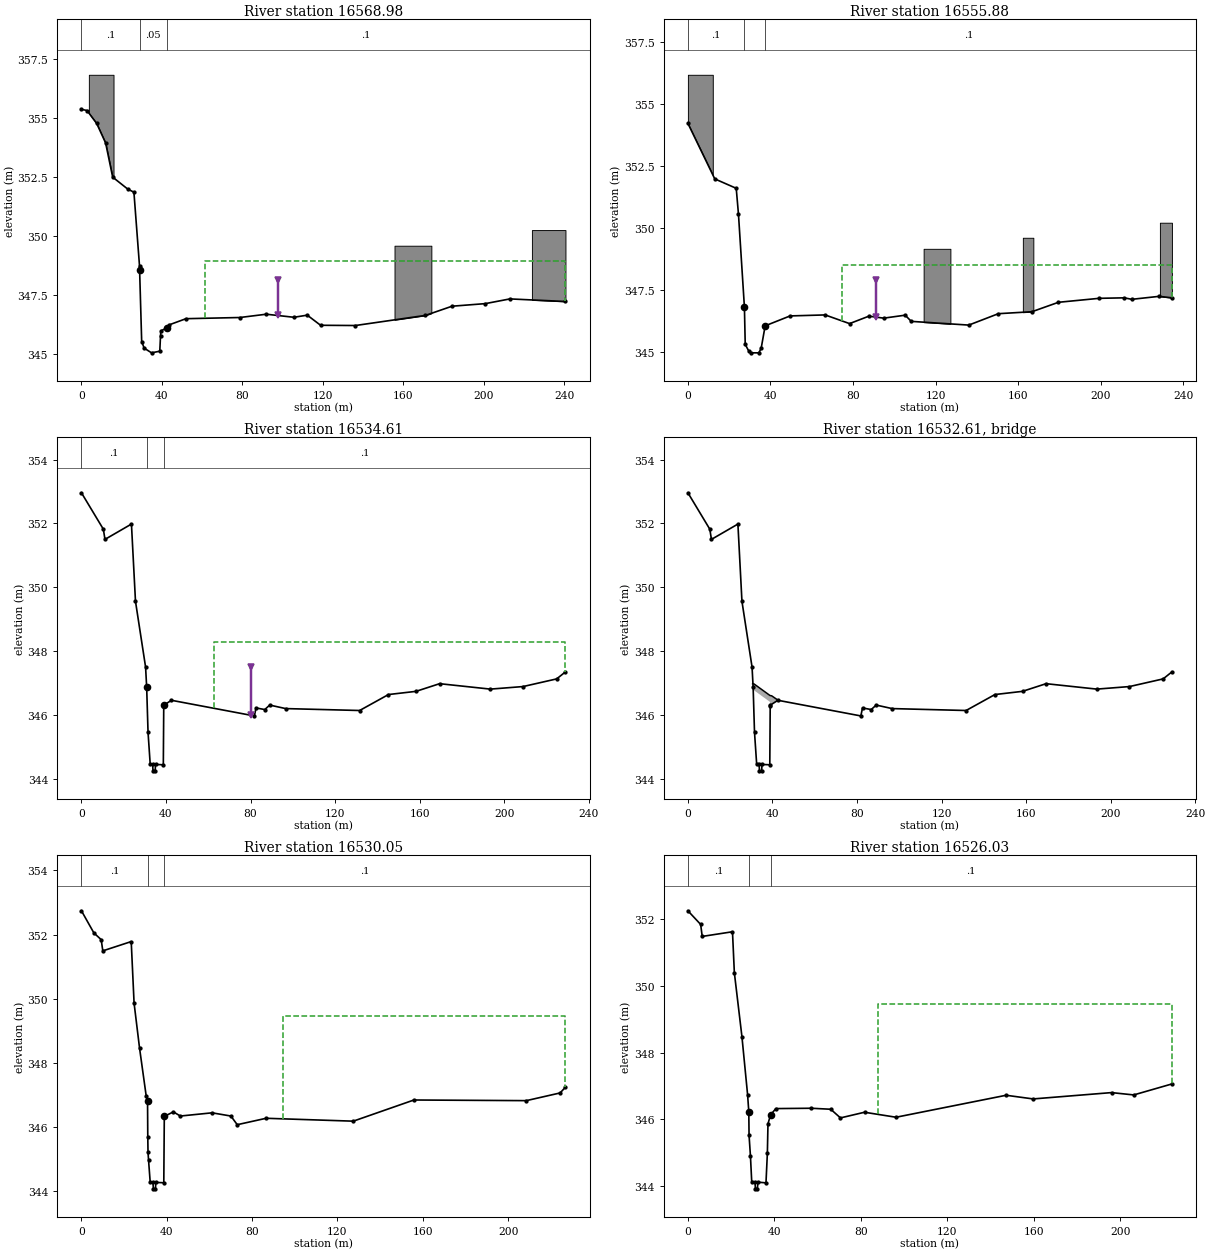
Type RM Length L Ch R = 1 ,16568.98,14.3,13.1,11.02
XS GIS Cut Line= 5
    -610486.8255   -1045706.5634-610495.14299999   -1045679.7281
    -610497.7888   -1045668.0863    -610514.7221    -1045594.532
    -610561.2439   -1045478.4149
#Sta/Elev= 29
       0  355.37    2.76  355.32    7.58  354.77   12.03  353.94   15.54  352.49
   22.92  351.99   26.09  351.85   28.89   348.7   28.92  348.54   29.95  345.51
   31.19  345.23   34.85  345.03   38.95   345.1   39.31  345.75   39.49  345.96
   42.33  346.09   43.66  346.22   51.97  346.48   78.74  346.53   91.89  346.67
  105.62  346.54  112.26  346.63  118.88   346.2  136.17  346.19     171  346.62
  184.22  347.01  200.78  347.12  212.99  347.32   240.6  347.21
#Mann= 3 , 0 , 0
       0      .1       0   28.92     .05       0   42.33      .1       0
Levee=0,,,-1,97.59,348.1275,,	2159
#XS Ineff= 2 , 0
                           61.35          348.95
Permanent Ineff=
       F       F
#Block Obstruct= 3 ,-1
    3.69   15.95356.8368  155.62  173.94 349.579  223.92   240.6350.2427
Bank Sta=28.92,42.33
XS Rating Curve= 0 ,0
Exp/Cntr=0.3,0.1

Type RM Length L Ch R = 1 ,16555.88,20.77,21.27,17.9
XS GIS Cut Line= 5
    -610504.2404   -1045706.1507    -610509.2146    -1045681.174
    -610509.4305   -1045668.0863-610521.60139999   -1045611.4654
    -610562.8314   -1045479.6849
#Sta/Elev= 27
       0  354.23   13.02  351.99   23.42  351.61   24.51  350.56   27.39  346.81
   27.78  345.31   29.57  345.03   30.58  344.97   34.36  344.97    35.5  345.15
   37.44  346.06   49.54  346.46    66.5   346.5   78.34  346.15   87.71  346.45
    94.9  346.37   105.3  346.49  108.23  346.24  136.11  346.09  150.44  346.55
  166.72  346.63  179.56  347.01  199.26  347.17  211.42  347.19  215.11  347.13
  228.36  347.25  234.55  347.19
#Mann= 3 , 0 , 0
       0      .1       0   27.39     .05       0   37.44      .1       0
Levee=0,,,-1,91.29,347.9076,,	2159
#XS Ineff= 2 , 0
                           74.91          348.51
Permanent Ineff=
       F       F
#Block Obstruct= 4 ,-1
       0   12.06356.1919  114.23   127.2349.1687  162.31  167.39349.6144
  228.72  234.55350.2217
Bank Sta=27.39,37.44
XS Rating Curve= 0 ,0
Exp/Cntr=0.3,0.1

Type RM Length L Ch R = 1 ,16534.61,4.61,4.56,4.51
XS GIS Cut Line= 6
-610529.54529999   -1045705.4184    -610529.8783    -1045676.323
-610530.17399999   -1045665.9981-610534.91189999   -1045624.3717
-610542.27789999   -1045575.2226-610569.46539999   -1045481.1129
#Sta/Elev= 30
       0  352.96   10.36  351.82   11.14   351.5   23.66  351.98   25.57  349.56
   30.35   347.5   30.86  346.87   31.51  345.46   32.53  344.46   33.67  344.45
   33.87  344.25   34.87  344.25   35.07  344.45   38.74  344.44   38.94  346.29
   39.07  346.31   42.57  346.46   81.81  345.97    82.6  346.22   86.73  346.17
   89.08  346.31   96.62   346.2  131.61  346.14  145.25  346.64  158.29  346.74
  169.44  346.98  193.45  346.81   208.9  346.89  224.82  347.13  228.98  347.35
#Mann= 3 , 0 , 0
       0      .1       0   30.86     .04       0   39.07      .1       0
Levee=0,,,-1,80.25,347.4962,,	2159
#XS Ineff= 2 , 0
                            62.5          348.28
Permanent Ineff=
       F       F
Bank Sta=30.86,39.07
XS Rating Curve= 0 ,0
Exp/Cntr=0.5,0.3

Type RM Length L Ch R = 3 ,16532.61,,,
Bridge Culvert--1,0,-1,-1, 0
Deck Dist Width WeirC Skew NumUp NumDn MinLoCord MaxHiCord MaxSubmerge Is_Ogee
1,1.6,1.4,0, 7, 7, , , 0.98, 0, 0,0,,
   30.63   31.33   31.33   38.83   38.83   39.63   42.49
  346.98  346.97  346.97  346.61  346.61   346.6  346.47
  346.78          346.77  346.41
   30.48   31.18   31.18   38.68   38.68   39.48   43.12
  346.98  346.97  346.97  346.61  346.61   346.6  346.47
  346.78          346.77  346.41
BR Coef=-1 , 0 , 0 ,, 0 ,,,0.8,-1,,0,
WSPro=,,,, 1 ,,,, 0 ,,,, 0 ,,,,-1 ,-1 ,-1 , 0 , 0 , 0 , 0 , 0
BC Design=,, 0 ,, 0 ,,,,,,
BC Use User HTab Curves=0
BC User HTab FreeFlow(D)= 0

Type RM Length L Ch R = 1 ,16530.05,3.73,4.02,4.32
XS GIS Cut Line= 6
    -610534.1055   -1045705.0639-610534.43849999   -1045675.9685
    -610534.7342   -1045665.6436    -610539.4721   -1045624.0172
    -610546.8381   -1045574.8681    -610573.0214   -1045482.6369
#Sta/Elev= 30
       0  352.74    5.83  352.05    9.26  351.84   10.02  351.49   23.34  351.78
   24.68  349.86   27.24  348.46   30.35  346.97   30.99  346.81    31.1   345.7
   31.21  345.22   31.46  344.97   32.23  344.28   33.48  344.28   33.76  344.07
   34.69  344.07   34.89  344.27   38.61  344.26   38.85  346.33   43.12  346.47
   46.35  346.34   61.25  346.44   70.06  346.34   73.04  346.07   86.57  346.27
  127.43  346.18  155.85  346.84  208.55  346.82  224.39  347.06   226.9  347.24
#Mann= 3 , 0 , 0
       0      .1       0   30.99     .04       0   38.85      .1       0
#XS Ineff= 2 , 0
                           94.54          349.47
Permanent Ineff=
       F       F
Bank Sta=30.99,38.85
XS Rating Curve= 0 ,0
Exp/Cntr=0.5,0.3

Type RM Length L Ch R = 1 ,16526.03,4.58,4.2,3.62
XS GIS Cut Line= 5
    -610538.0693   -1045702.3362-610538.07229999    -1045677.112
    -610539.6568   -1045657.3569-610551.82759999   -1045576.9234
    -610578.2707   -1045483.1449
#Sta/Elev= 30
       0  352.26     5.9  351.85    6.62  351.49   20.62  351.63   21.48   350.4
   24.99  348.48    27.6  346.74   28.16  346.23   28.28  345.52   28.91  344.91
   29.51  344.13   31.02  344.12   31.22  343.92   32.08  343.91   32.44  344.11
   36.11  344.09   36.75  344.98   37.03  345.86    38.2  346.13   40.68  346.32
   57.07  346.33   66.05   346.3   70.55  346.04   81.67  346.21   96.26  346.06
  147.15  346.72  159.66  346.61   195.9   346.8  206.17  346.73  223.83  347.06
#Mann= 3 , 0 , 0
       0      .1       0   28.16     .04       0    38.2      .1       0
#XS Ineff= 2 , 0
                           87.76          349.45
Permanent Ineff=
       F       F
Bank Sta=28.16,38.2
XS Rating Curve= 0 ,0
Exp/Cntr=0.3,0.1

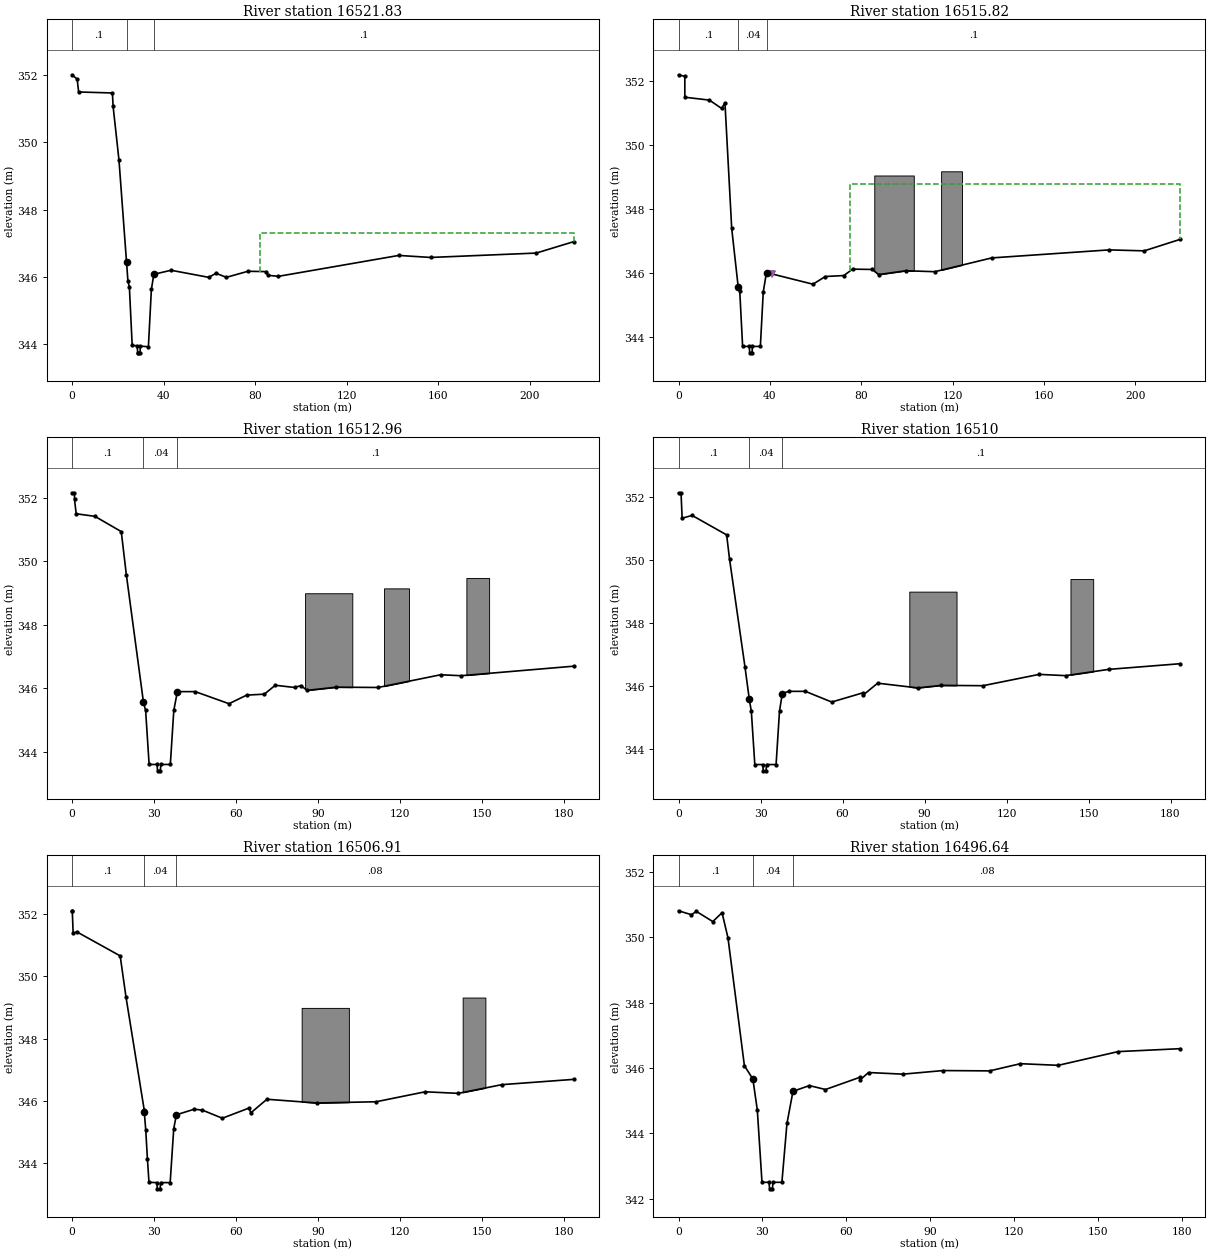
Type RM Length L Ch R = 1 ,16521.83,6.74,6.01,5.22
XS GIS Cut Line= 4
    -610542.1235   -1045699.3356    -610543.0548   -1045657.4255
    -610557.9562   -1045571.9967    -610579.7877   -1045484.1398
#Sta/Elev= 30
       0     352    2.23  351.87    2.87  351.49   17.63  351.46   17.91  351.07
    20.5  349.46   23.79  346.44    24.4  345.88   25.03   345.7   26.26  343.97
   28.45  343.96   28.64  343.76   28.85  343.75   29.66  343.75   29.86  343.95
   33.34  343.93   34.64  345.63   35.71  346.08   43.23   346.2    59.7  345.99
   62.86  346.11   67.39  345.99   76.82  346.17   84.53  346.16   85.58  346.05
   90.13  346.02   142.7  346.64  156.61  346.58  202.73  346.71  219.17  347.05
#Mann= 3 , 0 , 0
       0      .1       0   23.79     .04       0   35.71      .1       0
#XS Ineff= 2 , 0
                           82.13          347.31
Permanent Ineff=
       F       F
Bank Sta=23.79,35.71
XS Rating Curve= 0 ,0
Exp/Cntr=0.3,0.1

Type RM Length L Ch R = 1 ,16515.82,2.86,2.86,2.83
XS GIS Cut Line= 5
    -610549.2021   -1045701.0436    -610549.7798   -1045679.3474
    -610548.1328   -1045663.7179    -610550.4721   -1045643.0045
    -610581.5868   -1045484.5631
#Sta/Elev= 30
       0  352.19    2.75  352.14    2.76  351.49   13.52   351.4   18.86  351.14
   20.33  351.32   23.28   347.4   26.15  345.56   26.81  345.44   28.06  343.72
   30.97  343.72   31.17  343.52   32.17  343.52   32.37  343.72   35.83  343.72
    37.1  345.42   38.47  346.01   38.68  346.02   58.86  345.66   64.28   345.9
   72.41  345.93   76.19  346.13   84.83  346.12   87.61  345.96   99.59  346.08
  112.21  346.05  137.16  346.48  188.56  346.73  203.93   346.7  219.73  347.06
#Mann= 3 , 0 , 0
       0      .1       0   26.15     .04       0   38.68      .1       0
Levee=0,,,-1,40.99,345.99,,
#XS Ineff= 2 , 0
                            75.2          348.78
Permanent Ineff=
       F       F
#Block Obstruct= 2 ,-1
   85.71  103.01  349.05  114.98  124.12349.1804
Bank Sta=26.15,38.68
XS Rating Curve= 0 ,0
Exp/Cntr=0.3,0.1

Type RM Length L Ch R = 1 ,16512.96,2.96,2.96,2.85
XS GIS Cut Line= 5
    -610552.0539   -1045700.8215    -610552.6316   -1045679.1253
    -610550.9846   -1045663.4958-610553.32389999   -1045642.7824
    -610576.8487   -1045519.6843
#Sta/Elev= 30
       0  352.15     .88  352.14     .89  351.94    1.51  351.49    8.34  351.41
      18  350.93   19.85  349.58   26.13  345.56   26.91  345.31   28.19  343.61
   31.08  343.61   31.28  343.41   32.28  343.41   32.48  343.61   35.95  343.61
   37.22  345.31   38.53   345.9   45.06   345.9   57.42  345.52   63.88  345.79
   70.34  345.82   74.35   346.1   81.44  346.03    83.7  346.09   85.98  345.94
   96.73  346.04  111.96  346.03  134.86  346.43   142.3   346.4  183.59   346.7
#Mann= 3 , 0 , 0
       0      .1       0   26.13     .04       0   38.53      .1       0
#Block Obstruct= 3 ,-1
   85.25  102.53348.9921  114.14  123.28349.1454  144.27  152.58349.4734
Bank Sta=26.13,38.53
XS Rating Curve= 0 ,0
Exp/Cntr=0.3,0.1

Type RM Length L Ch R = 1 ,16510   ,3.1,3.09,3.07
XS GIS Cut Line= 5
    -610554.9674   -1045700.2362    -610555.5451     -1045678.54
    -610553.8981   -1045662.9105-610556.23739999   -1045642.1971
    -610579.7622    -1045519.099
#Sta/Elev= 30
       0  352.13     .91  352.14    1.32  351.33    4.96  351.42    17.6   350.8
   18.66  350.03   24.29  346.61   25.87  345.58   26.64  345.18   27.91  343.49
   30.81  343.49   31.01  343.29   32.01  343.29   32.21  343.49   35.69  343.49
   36.94  345.19   37.96  345.75   40.33  345.82   46.41  345.82   56.04  345.48
   67.35  345.77   67.67  345.71   72.86  346.08    87.5  345.93   96.15  346.01
   111.4     346  131.93  346.36  141.61  346.32  157.46  346.52  183.59   346.7
#Mann= 3 , 0 , 0
       0      .1       0   25.87     .04       0   37.96      .1       0
#Block Obstruct= 2 ,-1
   84.43  101.71348.9938   143.4  151.71349.3952
Bank Sta=25.87,37.96
XS Rating Curve= 0 ,0
Exp/Cntr=0.3,0.1

Type RM Length L Ch R = 1 ,16506.91,10.74,10.26,7.39
XS GIS Cut Line= 5
    -610558.0583   -1045700.0491     -610558.636   -1045678.3529
     -610556.989   -1045662.7234-610559.32829999     -1045642.01
    -610582.8531   -1045518.9119
#Sta/Elev= 30
       0  352.11     .08  352.11     .39   351.4    1.79  351.43    17.6  350.66
   19.74  349.33   26.37  345.72   26.42  345.64   26.95  345.07   27.57  344.13
   28.14  343.38      31  343.37    31.2  343.17    32.2  343.17    32.4  343.37
   35.89  343.37   37.19   345.1   38.16  345.55   44.67  345.73    47.7   345.7
   54.99  345.44   64.81  345.77   65.35  345.61    71.3  346.05    89.6  345.93
  111.25  345.97  129.19  346.29   141.3  346.24  157.27  346.52  183.59  346.69
#Mann= 3 , 0 , 0
       0      .1       0   26.42     .04       0   38.16     .08       0
#Block Obstruct= 2 ,-1
      84  101.28348.9877  142.91  151.22349.3203
Bank Sta=26.42,38.16
XS Rating Curve= 0 ,0
Exp/Cntr=0.3,0.1

Type RM Length L Ch R = 1 ,16496.64,11.84,11.82,12.2
XS GIS Cut Line= 5
-610568.93389999   -1045699.5274-610569.01029999   -1045673.3139
    -610566.1424   -1045658.7355    -610566.0002   -1045643.5141
    -610591.1844   -1045523.1212
#Sta/Elev= 30
       0  350.81    4.59  350.69    6.39  350.79   12.24  350.48   15.55  350.75
   17.67  349.98   23.53  346.07   26.56  345.66   28.15  344.71   29.82   342.5
   32.33   342.5   32.53   342.3   33.53   342.3   33.73   342.5   36.93   342.5
   38.74   344.3    40.9  345.29   41.07  345.29   46.74  345.46   52.51  345.34
   64.67  345.71   64.94  345.64   67.88  345.86   80.18  345.81   94.54  345.92
  111.15  345.91  122.14  346.13  135.67  346.08  157.06   346.5  179.29  346.59
#Mann= 3 , 0 , 0
       0      .1       0   26.56     .04       0   41.07     .08       0
Bank Sta=26.56,41.07
XS Rating Curve= 0 ,0
Exp/Cntr=0.3,0.1

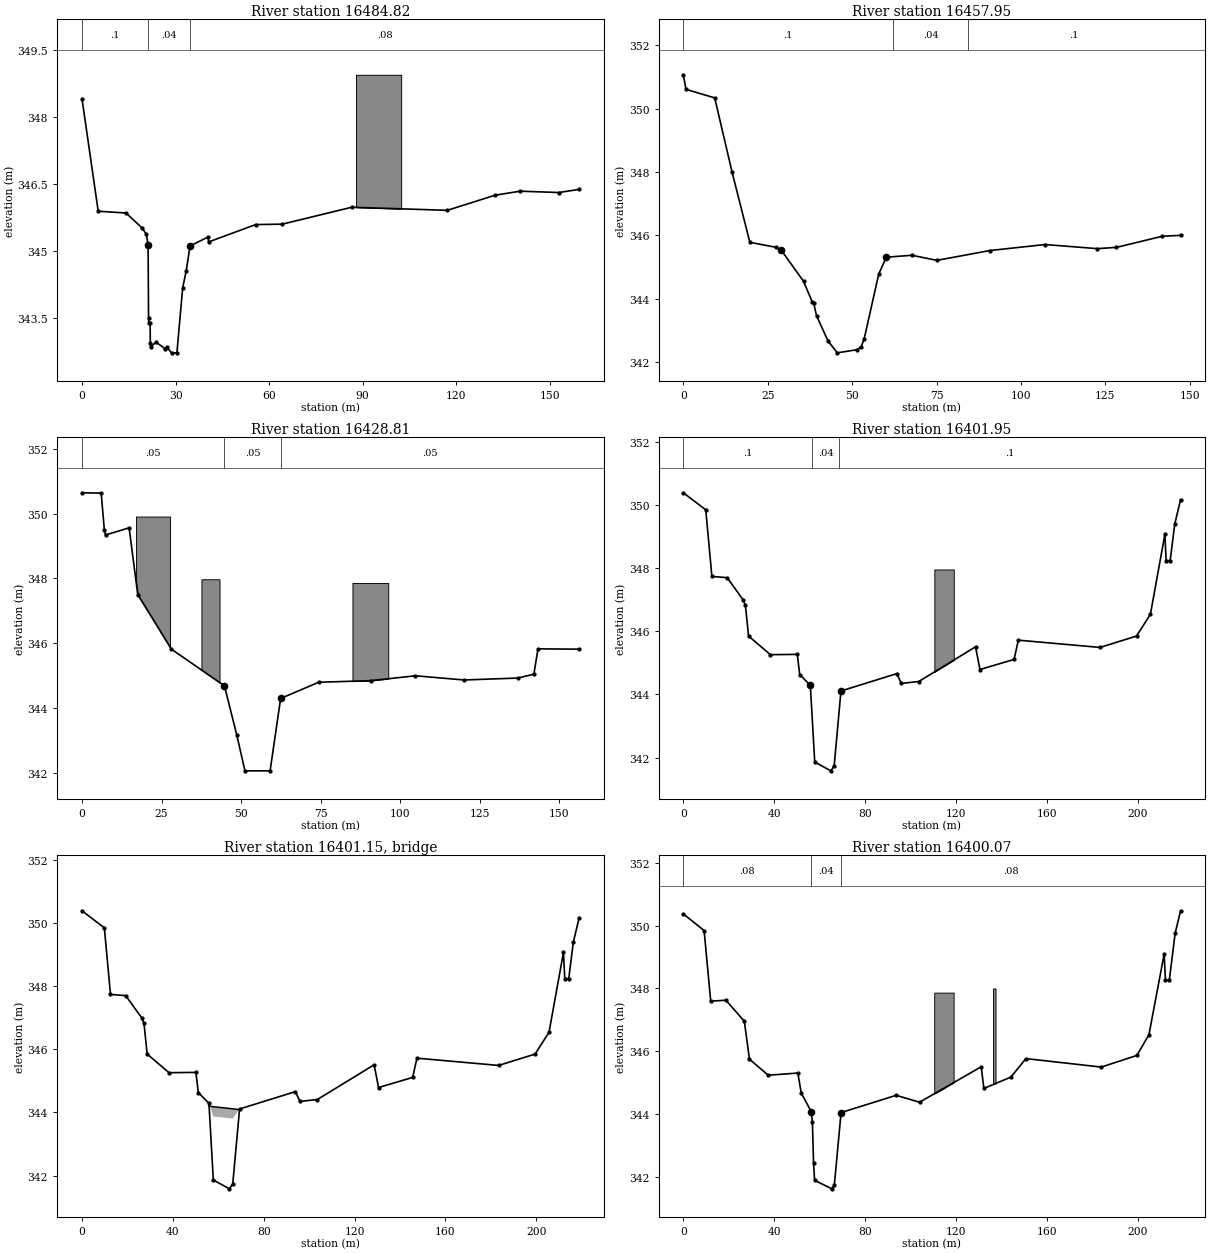
Type RM Length L Ch R = 1 ,16484.82,24.61,26.87,29.73
XS GIS Cut Line= 5
    -610578.8018   -1045690.2112    -610580.5927   -1045670.9478
    -610577.7248   -1045656.3694    -610578.6325   -1045641.3372
    -610601.1836   -1045533.5318
#Sta/Elev= 29
       0  348.42    5.21  345.89   14.12  345.85   19.35  345.51   20.66  345.37
    21.2  345.14   21.35  343.49   21.44  343.37   21.86  343.37   21.91  342.93
   21.98  342.84   23.71  342.95   26.72   342.8   27.21  342.84   28.71  342.71
   30.44  342.71   32.29  344.17   33.43  344.55   34.64  345.11   40.42  345.31
   40.58   345.2    55.7  345.59   64.24   345.6   86.53  345.98  117.11  345.91
  132.48  346.25  140.48  346.34  152.86  346.31   159.4  346.38
#Mann= 3 , 0 , 0
       0      .1       0    21.2     .04       0   34.64     .08       0
#Block Obstruct= 1 ,-1
   87.85  102.34 348.954
Bank Sta=21.2,34.64
XS Rating Curve= 0 ,0
Exp/Cntr=0.3,0.1

Type RM Length L Ch R = 1 ,16457.95,27.86,29.15,31.23
XS GIS Cut Line= 5
    -610600.4112   -1045709.3366    -610604.6319   -1045671.6896
    -610607.2707   -1045651.8644-610610.81619999   -1045634.4717
     -610633.272   -1045566.4278
#Sta/Elev= 26
       0  351.07     .76  350.61    9.29  350.34   14.42     348    19.7  345.78
   27.53  345.62      29  345.53   35.59  344.55   38.18   343.9   38.58  343.87
   39.46  343.46   42.87  342.66   45.62  342.29   51.48  342.39   52.72  342.49
   53.58  342.74   57.88  344.78   60.14  345.31   67.71  345.37   75.12  345.21
   90.78  345.52  107.15  345.71  122.62  345.58  128.27  345.62  141.83  345.97
  147.29     346
#Mann= 3 ,-1 , 0
       0      .1       0   62.13     .04       0   84.25      .1       0
Bank Sta=29,60.14
XS Rating Curve= 0 ,0
Exp/Cntr=0.3,0.1

Type RM Length L Ch R = 1 ,16428.81,27.35,26.86,24.82
XS GIS Cut Line= 2
    -610619.1772   -1045721.7966-610661.80689999   -1045571.4847
#Sta/Elev= 20
       0  350.64    6.05  350.63    7.04  349.48    7.42  349.34   14.82  349.56
   17.54   347.5    28.1  345.82   44.77  344.69   48.61  343.19   51.22  342.07
   59.12  342.07   62.43   344.3   74.37   344.8   90.77  344.85  104.81     345
   120.1  344.87  137.01  344.93  142.02  345.05   143.3  345.83  156.24  345.82
#Mann= 3 , 0 , 0
       0     .05       0   44.77     .05       0   62.43     .05       0
#Block Obstruct= 3 ,-1
   16.98   27.69349.9077   37.54   43.23347.9749      85   96.25347.8609
Bank Sta=44.77,62.43
XS Rating Curve= 0 ,0
Exp/Cntr=0.3,0.1

Type RM Length L Ch R = 1 ,16401.95,1.88,1.88,1.88
XS GIS Cut Line= 6
    -610643.0462   -1045735.4757    -610657.9483   -1045686.2902
-610661.88529999   -1045666.6815-610664.87119999    -1045645.638
-610675.02239999   -1045602.4955-610708.26749999   -1045527.6306
#Sta/Elev= 30
       0  350.39    9.85  349.85   12.56  347.74   19.29   347.7   26.28     347
   27.32  346.82    28.7  345.85   38.33  345.26   50.16  345.27   51.22  344.63
    55.9  344.29   57.83  341.86   64.94  341.58   66.39  341.74   69.38  344.11
   93.96  344.66   95.97  344.35  103.63  344.41  128.62  345.51  130.57  344.79
  145.58  345.11  147.47  345.72  183.43  345.49  199.49  345.85  205.61  346.54
  211.97  349.07  212.55  348.24   214.3  348.24  216.33   349.4  218.88  350.17
#Mann= 3 ,-1 , 0
       0      .1       0   56.59     .04       0   68.65      .1       0
#Block Obstruct= 1 ,-1
  110.49  119.04347.9603
Bank Sta=55.9,69.38
XS Rating Curve= 0 ,0
Exp/Cntr=0.5,0.3

Type RM Length L Ch R = 3 ,16401.15,,,
BEGIN DESCRIPTION:
16595.9  PF 211 ŽELEZNÁ LÁVKA PRO PÌŠÍ V
END DESCRIPTION:
Bridge Culvert--1,0,-1,-1, 0
Deck Dist Width WeirC Skew NumUp NumDn MinLoCord MaxHiCord MaxSubmerge Is_Ogee
0.5,1.3,1.4,0, 2, 2, , , 0.98, 0, 0,0,,
    55.8   69.52
   344.2  344.09
  343.89  343.78
    55.8   69.52
   344.2  344.09
  343.89  343.78
BR Coef=-1 , 0 , 0 ,, 0 ,,,0.8,-1,,0,
WSPro=,,,, 1 ,,,, 0 ,,,, 0 ,,,,-1 ,-1 ,-1 , 0 , 0 , 0 , 0 , 0
BC Design=,, 0 ,, 0 ,,,,,,
BC Use User HTab Curves=0
BC User HTab FreeFlow(D)= 0

Type RM Length L Ch R = 1 ,16400.07,8.96,8.12,7.29
XS GIS Cut Line= 6
-610644.88569999   -1045735.8526-610659.78779999   -1045686.6671
    -610663.7248   -1045667.0584    -610666.7107   -1045646.0149
    -610676.8619   -1045602.8724     -610710.107   -1045528.0075
#Sta/Elev= 30
       0  350.37    9.13  349.84   12.04  347.59   18.73  347.62   26.84  346.95
    29.1  345.74   37.36  345.23    50.4   345.3    51.9  344.66    56.3  344.07
   56.81  343.73   57.32  342.42   57.79  341.88   65.38  341.61   66.46  341.73
   69.43  344.04   93.66  344.59  103.99  344.37  131.13   345.5  132.29  344.81
  144.17  345.17   150.8  345.76  183.97  345.49  199.64  345.86  204.96  346.52
  211.66  349.09  212.24  348.26  213.94  348.26  216.49  349.75  218.88  350.47
#Mann= 3 , 0 , 0
       0     .08       0    56.3     .04       0   69.43     .08       0
#Block Obstruct= 2 ,-1
  110.43  118.98347.8619  136.33  137.43347.9948
Bank Sta=56.3,69.43
XS Rating Curve= 0 ,0
Exp/Cntr=0.5,0.3

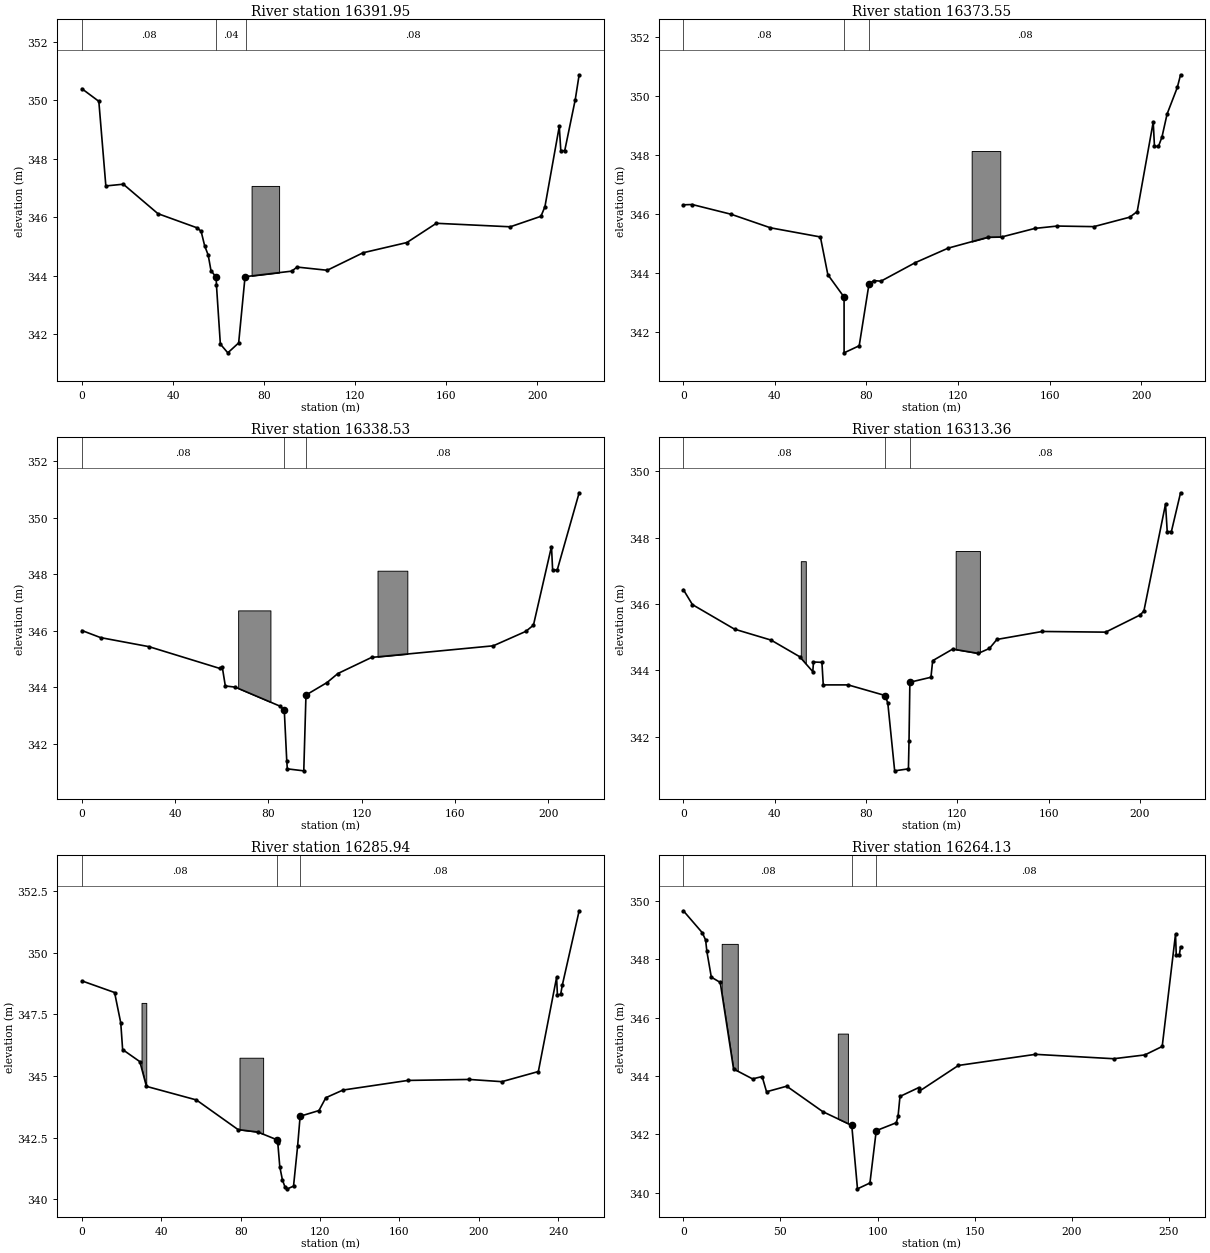
Type RM Length L Ch R = 1 ,16391.95,18.23,18.4,18.11
XS GIS Cut Line= 6
    -610650.4058   -1045738.2674    -610658.0192   -1045723.5482
     -610669.287   -1045687.5937     -610674.261   -1045646.3993
    -610688.4727    -1045603.003-610717.91099999   -1045531.9448
#Sta/Elev= 30
       0   350.4    7.41  349.97   10.49  347.07   18.16  347.13   33.37  346.12
   50.73  345.63   52.36  345.51   53.89  345.02   55.45   344.7   56.67  344.17
   58.95  343.94   59.07  343.68   60.79  341.65   64.07  341.35   68.83  341.69
   71.64  343.96   92.16  344.15   94.48  344.29  107.73  344.18  123.49  344.78
  142.72  345.13  155.66  345.79  188.15  345.67  201.62  346.03  203.37  346.36
  209.67  349.11  210.34  348.28  212.07  348.28  216.69  350.03   218.4  350.88
#Mann= 3 ,-1 , 0
       0     .08       0   58.88     .04       0   71.91     .08       0
#Block Obstruct= 1 ,-1
   74.51    86.6347.0706
Bank Sta=58.95,71.64
XS Rating Curve= 0 ,0
Exp/Cntr=0.3,0.1

Type RM Length L Ch R = 1 ,16373.55,26.96,35.01,35.49
XS GIS Cut Line= 4
    -610673.7292   -1045747.0293    -610688.7177   -1045678.5817
-610686.21959999   -1045667.0905    -610730.6856   -1045539.1883
#Sta/Elev= 29
       0   346.3    3.86  346.31   20.86  345.98   38.07  345.52   59.87  345.21
   63.13  343.93   70.04  343.19   70.22  343.18   70.23  341.28   76.83  341.52
    81.1  343.61   83.14  343.73   86.32  343.71  101.37  344.34  115.67  344.83
  133.07   345.2   139.1  345.21  153.59   345.5  163.39  345.58  179.35  345.56
  195.01  345.88  198.29  346.07   205.3  349.11  205.84  348.28  207.58  348.28
  209.12   348.6  211.36  349.38  215.82  350.28  217.24  350.71
#Mann= 3 , 0 , 0
       0     .08       0   70.04     .04       0    81.1     .08       0
#Block Obstruct= 1 ,-1
  125.97  138.46348.1243
Bank Sta=70.04,81.1
XS Rating Curve= 0 ,0
Exp/Cntr=0.3,0.1

Type RM Length L Ch R = 1 ,16338.53,23.53,25.17,25.21
XS GIS Cut Line= 4
    -610687.2188   -1045751.5259    -610719.1944   -1045672.0866
    -610724.1906   -1045661.0951    -610765.6589   -1045553.1776
#Sta/Elev= 23
       0  346.01    7.99  345.76   28.76  345.44   59.15  344.67    60.2  344.72
   61.51  344.05   65.74  344.01   84.87  343.34    86.8   343.2   87.87   341.4
   88.11  341.12   95.17  341.05   96.11  343.73  105.13  344.17   109.8  344.49
  124.28  345.06  176.47  345.47  190.43  345.98  193.71   346.2  201.45  348.98
  201.94  348.15  203.91  348.15  213.32  350.88
#Mann= 3 , 0 , 0
       0     .08       0    86.8     .04       0   96.11     .08       0
#Block Obstruct= 2 ,-1
  126.81   139.6348.1252   67.01   80.86346.7222
Bank Sta=86.8,96.11
XS Rating Curve= 0 ,0
Exp/Cntr=0.3,0.1

Type RM Length L Ch R = 1 ,16313.36,24.7,27.42,30.51
XS GIS Cut Line= 4
    -610701.2082   -1045759.0202    -610742.6765   -1045680.0805
    -610748.1723    -1045669.089-610786.14319999   -1045559.1731
#Sta/Elev= 30
       0  346.43    3.96  345.98    22.4  345.24   38.42  344.91   50.93  344.41
   56.68  343.96   56.99  344.25   60.68  344.24   61.27  343.56   72.16  343.56
   88.37  343.24   89.54  343.01   92.54  340.97   98.57  341.03   98.83  341.88
    99.2  343.64  108.43  343.79  109.19  344.29  117.98  344.64  129.16  344.51
  134.06  344.66  137.33  344.93   157.2  345.17  184.94  345.15  200.12  345.67
   201.7  345.79  211.17  349.01  211.91  348.18  213.73  348.18  217.75  349.35
#Mann= 3 , 0 , 0
       0     .08       0   88.37     .04       0    99.2     .08       0
#Block Obstruct= 2 ,-1
  119.26  129.87347.5963   51.43   53.62347.2883
Bank Sta=88.37,99.2
XS Rating Curve= 0 ,0
Exp/Cntr=0.3,0.1

Type RM Length L Ch R = 1 ,16285.94,21.15,21.82,19.48
XS GIS Cut Line= 6
    -610715.3028   -1045778.9285-610738.31199999   -1045740.1285
    -610761.2514   -1045696.4839-610775.34899999   -1045682.2974
    -610811.4005   -1045572.2957    -610806.8889   -1045552.4446
#Sta/Elev= 30
       0  348.85   16.44  348.38   19.55  347.15   20.49  346.07   29.18  345.58
   32.47  344.58   57.65  344.03   78.64  342.83   88.67  342.73   98.46  342.41
   98.69  342.28   99.69  341.32  101.04  340.78  102.39  340.49  103.54  340.43
  106.61  340.54  108.69  342.18  109.93  343.37  119.42   343.6  122.88  344.12
  131.51  344.43  164.24  344.82  195.14  344.86  211.58  344.77  229.97  345.18
  239.16  348.99  239.58  348.28  241.23  348.31  242.02  348.67  250.53  351.69
#Mann= 3 , 0 , 0
       0     .08       0   98.46     .04       0  109.93     .08       0
#Block Obstruct= 2 ,-1
   30.02    32.4347.9592   79.38   91.29345.7397
Bank Sta=98.46,109.93
XS Rating Curve= 0 ,0
Exp/Cntr=0.3,0.1

Type RM Length L Ch R = 1 ,16264.13,20.35,23.06,15.94
XS GIS Cut Line= 4
    -610733.6834   -1045786.4992-610776.15089999    -1045709.558
-610787.14249999   -1045704.0622    -610840.6015   -1045557.6742
#Sta/Elev= 30
       0  349.65    9.74   348.9   11.46  348.65    12.1  348.26   14.39  347.38
   18.98   347.2   25.84  344.24   35.64   343.9   40.56  343.98   42.83  343.46
   53.22  343.65   71.79  342.78   86.71  342.31   89.66  340.14   96.07  340.34
   99.32  342.13  109.62   342.4  110.55  342.62  111.54   343.3  121.12   343.6
  121.53  343.48  141.62  344.36  181.32  344.74  221.59  344.59  237.64  344.72
  246.57  345.01  253.43  348.85   253.8  348.14  255.39  348.14  256.02  348.42
#Mann= 3 , 0 , 0
       0     .08       0   86.71     .04       0   99.32     .08       0
#Block Obstruct= 2 ,-1
   19.74   28.01 348.518   79.53   84.73345.4495
Bank Sta=86.71,99.32
XS Rating Curve= 0 ,0
Exp/Cntr=0.3,0.1