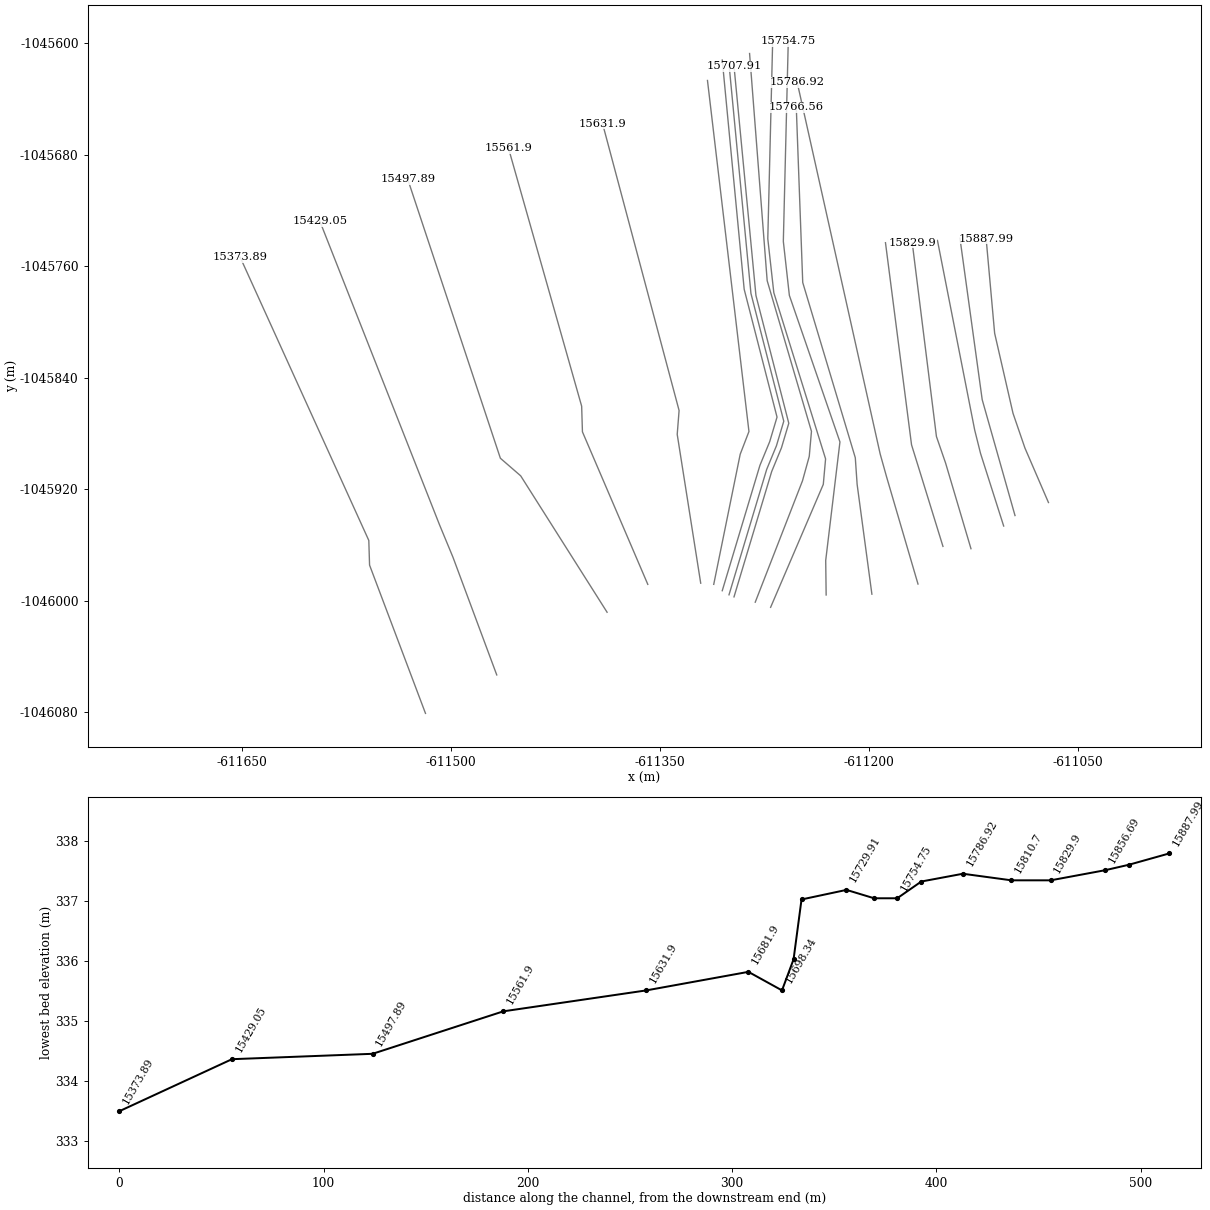
HEC-RAS study PPO_Kvasiny_efektiv.prj: PPO_Kvasiny_efektivita

--- PPO_Kvasiny_efektiv.g15 (geometry) --- (continued)

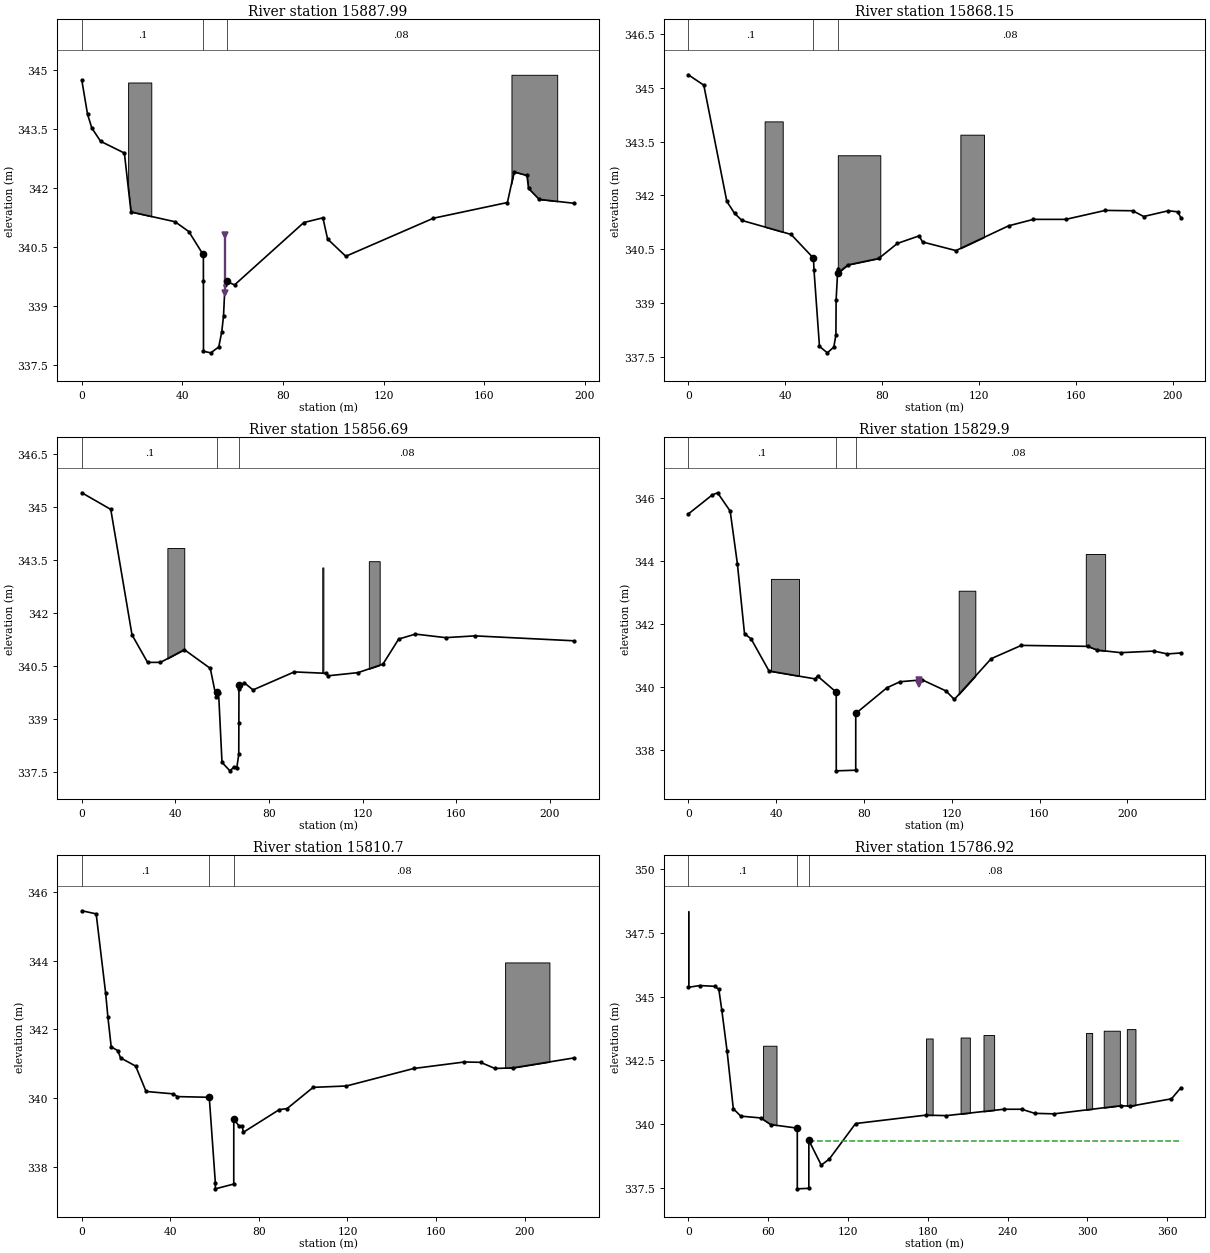
Type RM Length L Ch R = 1 ,15887.99,19.91,19.84,18.61
XS GIS Cut Line= 5
-611071.43079999   -1045929.3784-611088.29679999   -1045890.3326
    -611096.8689   -1045865.3553-611110.03889999   -1045807.9662
    -611116.1349   -1045740.2327
#Sta/Elev= 30
       0  344.74    2.26  343.88    3.95  343.53    7.45  343.19   16.91  342.89
   19.54  341.39   37.06  341.14   42.53  340.89   48.17  340.31   48.32   340.3
   48.34  339.64   48.37  337.84   51.28   337.8   54.44  337.95   55.65  338.34
   56.33  338.74   56.93  339.54   57.62  339.62   60.71  339.53   88.27  341.12
   95.85  341.24   97.72   340.7  104.95  340.26   139.8  341.23  169.22  341.63
  171.87  342.41     177  342.32  177.61  341.99  181.85  341.71  195.83  341.61
#Mann= 3 , 0 , 0
       0      .1       0   48.17     .04       0   57.62     .08       0
Levee=0,,,-1,56.76,340.8148,,	2160
#Block Obstruct= 2 ,-1
   18.39   27.61344.6881  170.83  189.02344.8846
Bank Sta=48.17,57.62
XS Rating Curve= 0 ,0
Exp/Cntr=0.3,0.1

Type RM Length L Ch R = 1 ,15868.15,11.59,11.46,10.73
XS GIS Cut Line= 3
    -611095.4338     -1045938.72    -611118.9712   -1045855.5772
    -611134.9309   -1045739.7811
#Sta/Elev= 30
       0  345.36    6.39  345.07    15.9  341.83   19.07   341.5   22.12   341.3
   42.42  340.91   51.66  340.25   51.88  339.92   54.14  337.79   57.39  337.61
   60.06  337.77   60.93  338.11   61.01  339.08   61.71  339.96   61.91  339.84
   65.86  340.06   78.61  340.24   86.31  340.66   95.28  340.87   96.69   340.7
  110.47  340.46  132.21  341.15  142.47  341.33  155.79  341.33  172.16  341.58
  183.48  341.57  187.98  341.41  198.16  341.57  202.07  341.54   203.3  341.38
#Mann= 3 , 0 , 0
       0      .1       0   51.66     .04       0   61.91     .08       0
#Block Obstruct= 3 ,-1
    31.5   38.97344.0612   61.71   79.25343.1169  112.31  122.04343.6905
Bank Sta=51.66,61.91
XS Rating Curve= 0 ,0
Exp/Cntr=0.3,0.1

Type RM Length L Ch R = 1 ,15856.69,26.05,26.8,27.68
XS GIS Cut Line= 4
    -611103.5637   -1045946.2449-611120.18499999   -1045894.0618
    -611124.3476   -1045877.4141     -611151.067   -1045741.3785
#Sta/Elev= 30
       0  345.39   12.36  344.92   21.44  341.37    28.1  340.59   33.62  340.59
   43.81  340.95   54.91  340.42   57.38  339.62   57.88  339.75   58.46  339.73
   59.92  337.76   63.31  337.52   64.92  337.62   66.21  337.59   67.09  337.99
   67.13  338.88   67.17  339.96   67.38  339.83   69.33  340.02   73.18  339.81
   90.82  340.32  104.41  340.28   105.3  340.21  118.11   340.3  128.73  340.54
  135.47  341.25  142.63  341.39  155.53  341.29  168.07  341.34  210.56   341.2
#Mann= 3 , 0 , 0
       0      .1       0   57.88    .035       0   67.17     .08       0
#Block Obstruct= 3 ,-1
   36.57   43.79343.8254  102.78  103.27 343.276   122.7  127.34343.4536
Bank Sta=57.88,67.17
XS Rating Curve= 0 ,0
Exp/Cntr=0.3,0.1

Type RM Length L Ch R = 1 ,15829.9 ,19.46,19.19,18.61
XS GIS Cut Line= 4
-611127.02369999   -1045962.5109-611145.18809999   -1045901.2055
    -611151.8026   -1045882.0232    -611169.1645    -1045742.966
#Sta/Elev= 28
       0  345.48   10.89  346.08   13.33  346.15   19.07  345.57   22.36   343.9
    25.6  341.69   28.57  341.53   36.77  340.51   57.75  340.26   58.86  340.35
   67.39  339.84    67.4  337.35   76.27  337.37   76.28  339.16   76.36  339.17
   90.51  339.98   96.45  340.17  106.54  340.23  117.37  339.88  121.19  339.61
  137.99   340.9  151.71  341.32  181.95  341.29  186.38  341.17  197.12  341.09
  212.17  341.14   218.2  341.05  224.37  341.08
#Mann= 3 , 0 , 0
       0      .1       0   67.39    .035       0   76.36     .08       0
Levee=0,,,-1,105.23,340.1,,
#Block Obstruct= 3 ,-1
   37.64   50.42343.4244  123.19  130.76343.0505  181.09   189.9344.2119
Bank Sta=67.39,76.36
XS Rating Curve= 0 ,0
Exp/Cntr=0.3,0.1

Type RM Length L Ch R = 1 ,15810.7 ,23.98,23.78,23.78
XS GIS Cut Line= 4
-611147.12029999   -1045960.8525-611163.70899999   -1045907.1587
-611169.66209999   -1045887.9764    -611188.3553   -1045742.9866
#Sta/Elev= 29
       0  345.46    6.47  345.37   10.74  343.06   11.78  342.35   13.26  341.49
   16.26  341.38   17.47  341.17   24.31  340.93   29.01  340.19    41.3  340.12
   43.17  340.04   57.56  340.02   60.31  337.52   60.32  337.35   68.62  337.49
   68.63  339.39   71.01  339.18   72.44  339.17   72.96     339   89.18  339.66
    92.7  339.69  104.49  340.31  119.55  340.35  149.92  340.86   172.8  341.05
   180.1  341.04  186.59  340.86  194.88  340.88  222.47  341.17
#Mann= 3 , 0 , 0
       0      .1       0   57.56     .04       0   68.63     .08       0
#XS Ineff= 2 , 0
       0                   68.63       0  339.39
Permanent Ineff=
       F       T
#Block Obstruct= 1 ,-1
   191.2  211.22343.9536
Bank Sta=57.56,68.63
XS Rating Curve= 0 ,0
Exp/Cntr=0.3,0.1

Type RM Length L Ch R = 1 ,15786.92,22.11,20.36,18.99
XS GIS Cut Line= 4
     -611165.032   -1045987.8568    -611187.5216   -1045911.1275
-611192.15179999    -1045894.591    -611251.6831   -1045628.0227
#Sta/Elev= 27
       0  345.36    8.56  345.43   19.87   345.4   22.95  345.28   25.17  344.47
   29.12  342.87   33.82   340.6   39.46  340.31   54.42  340.24   61.97  339.98
   81.93  339.84   81.94  337.46   90.61  337.48   90.62  339.36   99.95  338.39
  106.03  338.63  125.74  340.02  178.62  340.35  194.02  340.33  237.09  340.58
  250.73  340.58  260.41  340.42  274.87   340.4  325.38  340.72  332.41   340.7
  363.26  340.99  370.26  341.42
#Mann= 3 , 0 , 0
       0      .1       0   81.93    .035       0   90.62     .08       0
#XS Ineff= 2 , 0
       0                   90.85       0  339.34
Permanent Ineff=
       F       T
#Block Obstruct= 8 ,-1
       0     .15348.3615   56.21    66.3343.0709  178.74  183.69343.3546
  204.71  211.66343.3929  221.93  229.93343.4889     299  303.61343.5717
  312.31  324.45343.6595  329.69  336.18343.7225
Bank Sta=81.93,90.62
XS Rating Curve= 0 ,0
Exp/Cntr=0.3,0.1

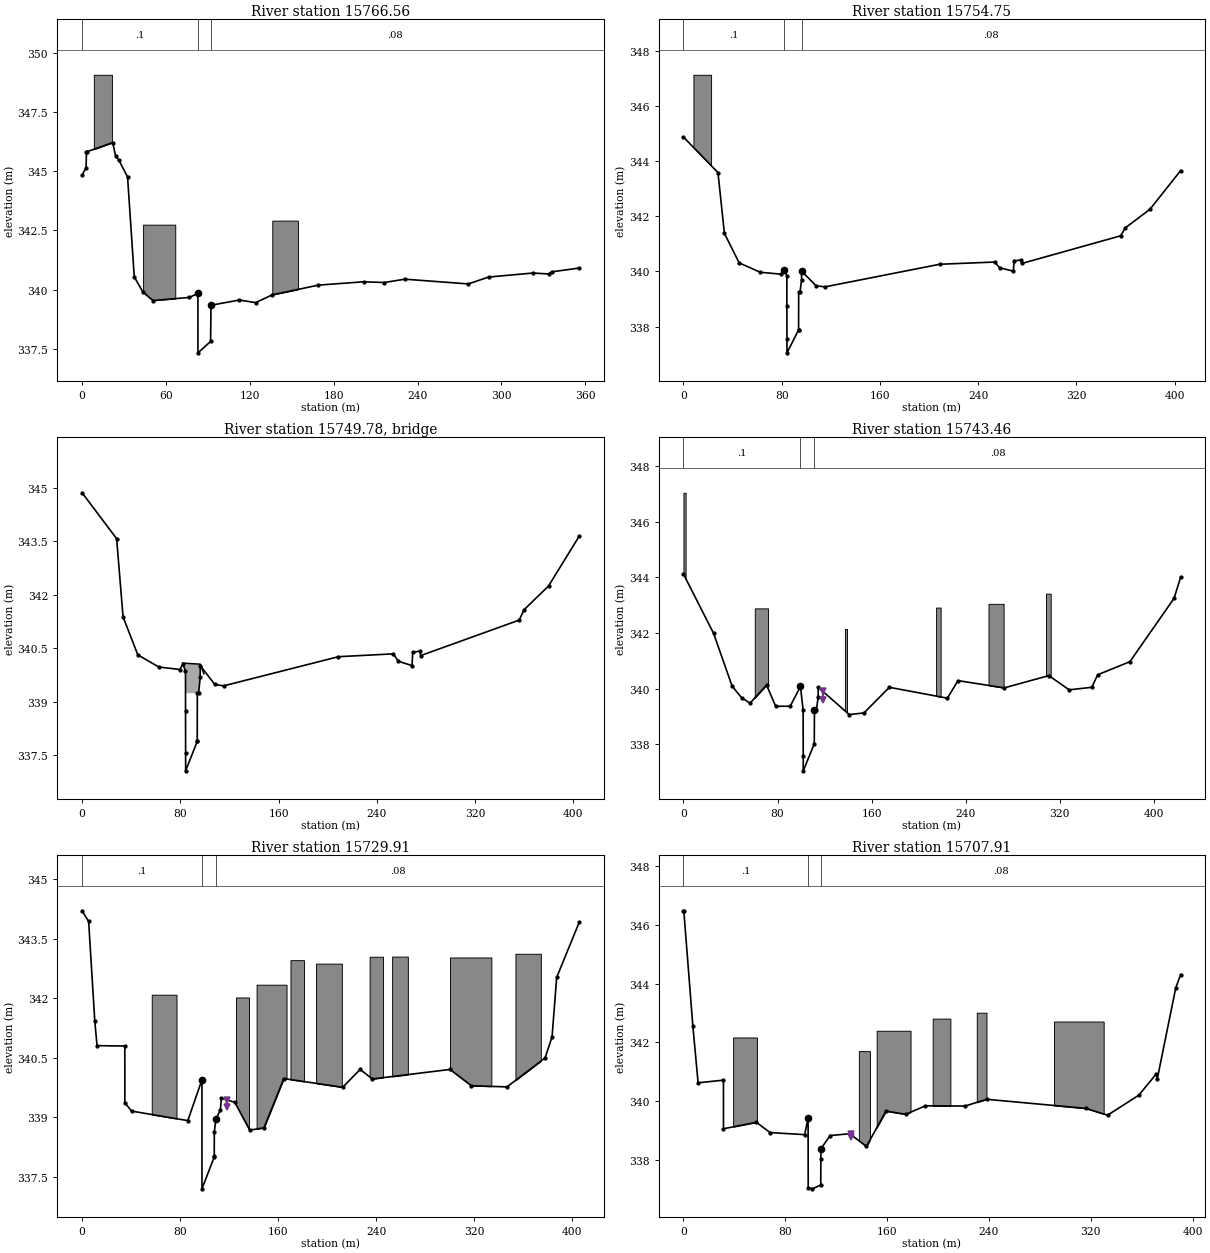
Type RM Length L Ch R = 1 ,15766.56,12.99,11.81,8.6
XS GIS Cut Line= 5
-611198.10489999   -1045995.1328-611208.68829999   -1045916.4191
    -611210.0111   -1045897.2368    -611247.7144   -1045771.5595
-611252.34459999   -1045645.8821
#Sta/Elev= 30
       0  344.83    2.84  345.15    3.15   345.8    3.42  345.82   21.89  346.21
   24.06  345.63    26.3  345.47   32.53  344.76   37.32  340.54   43.57  339.89
   50.72  339.54   76.73  339.67   82.87  339.84   82.88  337.33   91.93  337.81
   92.22  339.34   92.26  339.34  112.46  339.56  124.16  339.45     136  339.78
  169.11  340.19  201.46  340.33  216.15   340.3  230.96  340.44  276.32  340.24
  290.78  340.53  322.52   340.7  334.03  340.66  335.86  340.75  355.62  340.91
#Mann= 3 , 0 , 0
       0      .1       0   82.87    .035       0   92.26     .08       0
#Block Obstruct= 3 ,-1
    8.41   21.34349.0717   43.63   66.65 342.743  136.06  154.41342.9142
Bank Sta=82.87,92.26
XS Rating Curve= 0 ,0
Exp/Cntr=0.3,0.1

Type RM Length L Ch R = 1 ,15754.75,11.28,11.29,11.04
XS GIS Cut Line= 6
     -611230.918   -1045995.6999    -611231.2355   -1045970.9348
    -611221.0212    -1045885.914    -611257.3088   -1045780.7867
    -611261.6351    -1045742.032    -611258.0872   -1045598.3207
#Sta/Elev= 30
       0  344.87   28.12  343.58   33.36  341.38   45.38  340.31    62.5  339.97
    79.6   339.9   82.07  340.05   84.19  339.85   84.22  338.74   84.29  337.54
    84.3  337.05   93.74  337.88   93.75  337.89   93.83  339.24   94.91  339.25
   96.15  339.68   96.21  340.01  108.01  339.48  115.21  339.44  208.71  340.26
  253.27  340.34  257.54  340.13  268.64  340.01  269.15  340.38  275.01  340.42
   275.6  340.29  355.89  341.29  359.79  341.58  379.77  342.25  404.72  343.65
#Mann= 3 , 0 , 0
       0      .1       0   82.07    .035       0   96.21     .08       0
#Block Obstruct= 1 ,-1
    8.14   22.52347.1254
Bank Sta=82.07,96.21
XS Rating Curve= 0 ,0
Exp/Cntr=0.5,0.3

Type RM Length L Ch R = 3 ,15749.78,,,
Bridge Culvert--1,0,-1,-1, 0
Deck Dist Width WeirC Skew NumUp NumDn MinLoCord MaxHiCord MaxSubmerge Is_Ogee
0.5,10.4,1.4,0, 3, 2, , , 0.98, 0, 0,0,,
   81.88   96.21   99.18
  340.08  340.05  339.78
  339.24  339.23  339.78
   99.48   114.6
  340.08  340.05
  339.24  339.23
BR Coef=-1 , 0 , 0 ,, 0 ,,,0.8,-1,,0,
WSPro=,,,, 1 ,,,, 0 ,,,, 0 ,,,,-1 ,-1 ,-1 , 0 , 0 , 0 , 0 , 0
BC Design=,, 0 ,, 0 ,,,,,,
BC Use User HTab Curves=0
BC User HTab FreeFlow(D)= 0

Type RM Length L Ch R = 1 ,15743.46,14.98,13.54,10.62
XS GIS Cut Line= 6
    -611270.7595   -1046004.5644    -611232.9684    -1045916.367
-611231.32099999   -1045898.0854-611268.45829999   -1045778.8404
    -611272.7846   -1045740.0857    -611269.2368   -1045596.3744
#Sta/Elev= 30
       0  344.12   25.61  341.99   41.43  340.09   49.41  339.68    56.6  339.48
   70.68  340.13   78.41  339.37   90.78  339.37   99.48  340.08  101.76  339.24
  101.86  337.58  101.87  337.05  111.26  338.02   111.4  339.23  113.07  339.24
  114.55   339.7   114.6  340.05  140.98  339.07  153.54  339.13  175.09  340.05
  224.48  339.66  233.43  340.29  272.77  340.03  310.69  340.47  327.95  339.96
  347.21  340.05  352.21   340.5  379.62  340.97  417.22  343.25  422.69     344
#Mann= 3 , 0 , 0
       0      .1       0   99.48    .035       0   111.4     .08       0
Levee=0,,,-1,118.36,339.59,,
#Block Obstruct= 6 ,-1
       0    1.87347.0369   60.66   71.88342.8853   137.3  139.05342.1466
  214.83  218.71342.9147  259.38  272.25 343.048  308.26  312.29343.4149
Bank Sta=99.48,111.4
XS Rating Curve= 0 ,0
Exp/Cntr=0.5,0.3

Type RM Length L Ch R = 1 ,15729.91,23.06,22.01,19.38
XS GIS Cut Line= 6
    -611281.7885   -1046000.8759-611247.89779999   -1045913.8258
    -611243.0385   -1045896.2879    -611241.4543   -1045878.3214
    -611273.2296   -1045770.2109    -611285.8491   -1045607.2642
#Sta/Elev= 30
       0   344.2    5.36  343.93   10.38  341.41   12.22   340.8   34.88  340.79
    34.9  339.36   40.38  339.15    86.3  338.91   97.84  339.94   97.85  337.19
  107.83  337.99  107.89  338.03  107.94  338.63  109.25  338.95  112.92  339.18
  113.68  339.48  124.63  339.37  136.84  338.67  148.48  338.73  164.67  339.97
  212.71  339.75  226.96   340.2  236.88  339.96   300.3   340.2  317.72  339.79
  346.77  339.76  377.88  340.49   383.6  341.02  387.37  342.52  405.77  343.91
#Mann= 3 , 0 , 0
       0      .1       0   97.84    .035       0  109.25     .08       0
Levee=0,,,-1,118.65,339.25,,
#Block Obstruct= 9 ,-1
  125.59  136.26342.0143  142.44  166.88342.3365     191  212.02 342.868
   56.85   77.08342.0844  300.27  334.05343.0232  253.06  265.89343.0455
  353.72  374.44343.1166  170.09  181.11342.9549   234.7  245.66343.0414
Bank Sta=97.84,109.25
XS Rating Curve= 0 ,0
Exp/Cntr=0.3,0.1

Type RM Length L Ch R = 1 ,15707.91,3.89,3.89,3.9
XS GIS Cut Line= 6
    -611297.0154   -1045997.0692-611269.98739999   -1045907.1252
    -611262.9829    -1045890.143    -611257.7215   -1045872.5269
    -611281.2811   -1045780.8493    -611297.0154   -1045616.4002
#Sta/Elev= 30
       0  346.46     .29  346.47     7.4  342.56   11.53  340.63   31.45  340.72
   31.46  339.07   57.35  339.29   68.02  338.94   95.25  338.87   97.93  339.43
   98.03  337.07   101.3  337.03  107.88  337.16  107.95  338.03  108.02  338.39
  115.25  338.84  130.67   338.9  143.77  338.47  159.13  339.67  174.73  339.56
  190.03  339.85  221.21  339.84  238.26  340.07  316.29  339.76  333.17  339.53
  357.76  340.21  371.62  340.94  372.23  340.76  386.69  343.84  390.53   344.3
#Mann= 3 , 0 , 0
       0      .1       0   97.93    .035       0  108.02     .08       0
Levee=0,,,-1,131.41,338.79,,
#Block Obstruct= 6 ,-1
   39.03   57.74342.1694  291.09  330.12342.7108  195.81   209.7342.8094
  151.82  178.41342.3976  137.81  146.51341.7051  230.44  238.06343.0097
Bank Sta=97.93,108.02
XS Rating Curve= 0 ,0
Exp/Cntr=0.3,0.1

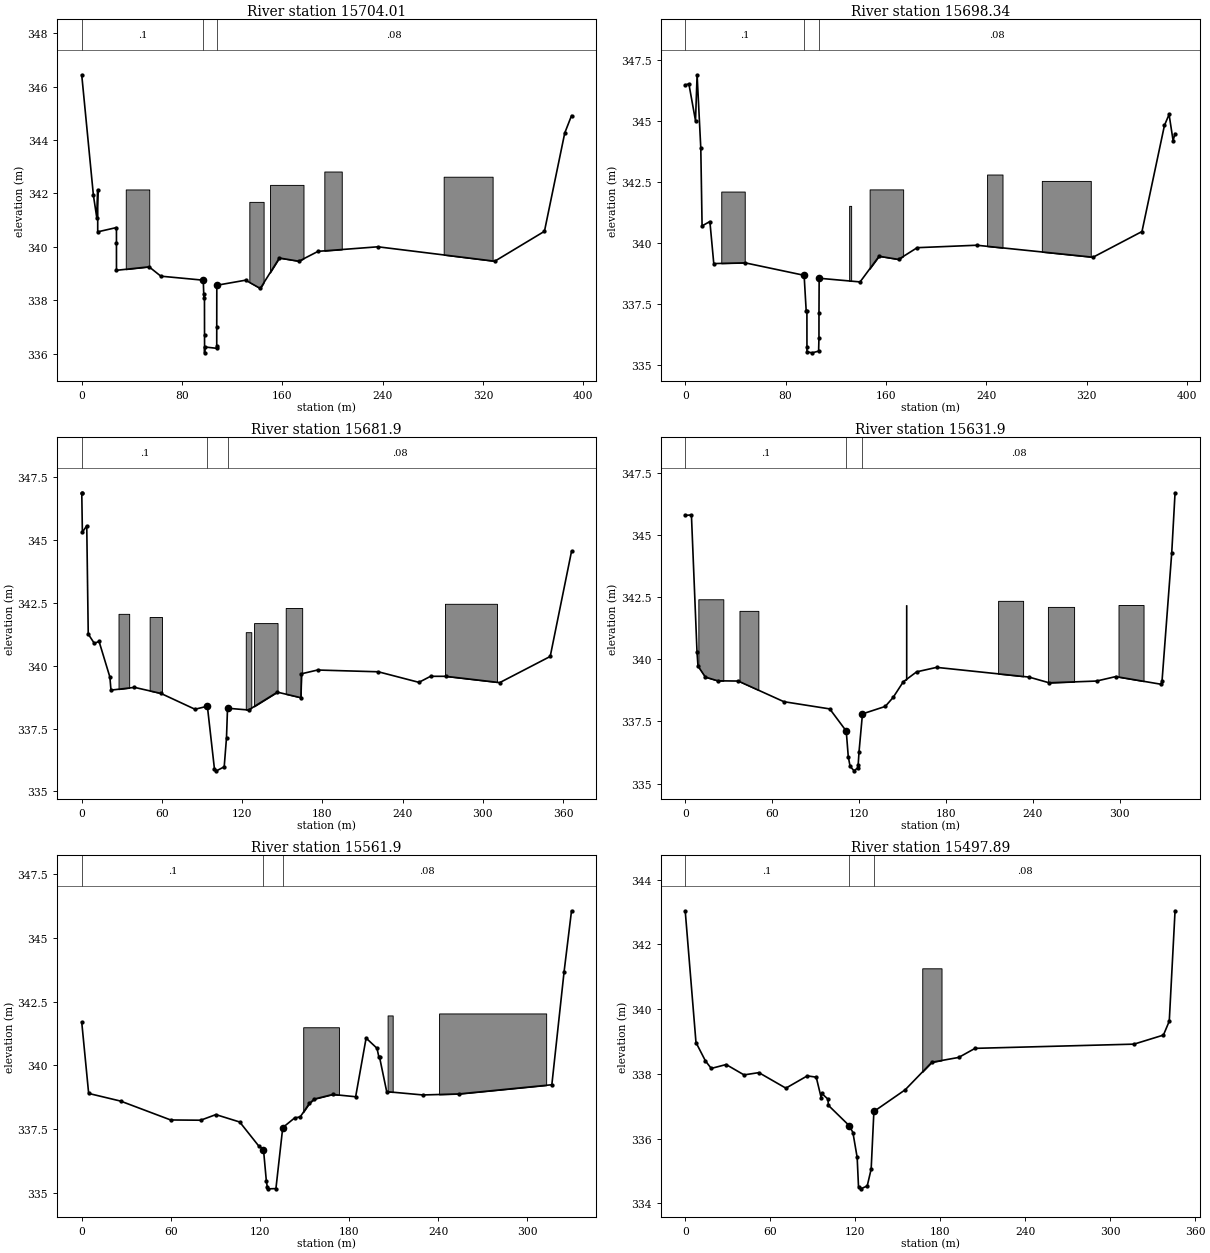
Type RM Length L Ch R = 1 ,15704.01,5.49,5.67,5.52
XS GIS Cut Line= 6
    -611300.6086    -1045995.581    -611273.5806   -1045905.6369
-611266.57609999   -1045888.6548    -611261.3147   -1045871.0387
    -611284.8744   -1045779.3611    -611300.6086    -1045614.912
#Sta/Elev= 30
       0  346.44    9.31  341.93   12.04  341.08   12.75  342.14   12.76  340.56
   27.69  340.72    27.7  340.14   27.71  339.12   53.73  339.25   63.09   338.9
   96.92  338.75   97.39  338.08   97.86  338.22   97.92   336.7   97.97  336.03
   97.99  336.25  107.58   336.2  107.65  336.28  107.66  336.99  107.71  338.56
  130.67  338.75  142.36  338.44  157.56  339.58  173.15  339.46  188.47  339.83
  236.17     340  329.33  339.46  368.94  340.58  385.12  344.26  390.53  344.91
#Mann= 3 , 0 , 0
       0      .1       0   96.92    .035       0  107.71     .08       0
#Block Obstruct= 5 ,-1
   35.12   53.83342.1467  133.64  145.02341.6818  150.16  176.82342.3174
  193.44  207.33342.8185  288.59  327.61342.6234
Bank Sta=96.92,107.71
XS Rating Curve= 0 ,0
Exp/Cntr=0.3,0.1

Type RM Length L Ch R = 1 ,15698.34,15.5,16.44,16.98
XS GIS Cut Line= 6
-611305.45039999   -1045992.6441-611278.42249999      -1045902.7
    -611271.4179   -1045885.7179    -611266.1565   -1045868.1018
    -611289.7162   -1045776.4242-611305.45039999   -1045611.9751
#Sta/Elev= 30
       0  346.46    2.89  346.51    8.18     345    9.45  346.88   12.39  343.88
   13.42   340.7   19.64  340.88   22.74  339.16   47.73  339.19   94.78  338.68
   96.42  337.23      97  337.23   97.03  335.75   97.05  335.55  101.17  335.51
  106.33  335.58  106.61  336.13  106.62  337.12  106.77  338.56   139.4  338.41
  154.52  339.46  170.07  339.33  184.92  339.81  232.43  339.91  325.16  339.42
  364.15  340.47  382.07  344.81  385.76  345.26  388.95  344.19  390.53  344.47
#Mann= 3 , 0 , 0
       0      .1       0   94.78    .035       0  106.77     .08       0
#Block Obstruct= 5 ,-1
   28.71   47.42342.1049  130.67  132.27  341.52     147  173.73342.1931
  240.64  252.95342.8019  284.31  323.33  342.54
Bank Sta=94.78,106.77
XS Rating Curve= 0 ,0
Exp/Cntr=0.3,0.1

Type RM Length L Ch R = 1 ,15681.9 ,45.84,50,51.56
XS GIS Cut Line= 4
-611311.56309999   -1045988.0799    -611292.5808   -1045894.7576
-611286.29859999   -1045878.4296-611316.05409999   -1045626.6029
#Sta/Elev= 30
       0  346.88     .04  346.88     .49  345.31    3.76  345.57    4.88  341.26
    9.43  340.89   12.96  340.97   21.06  339.55   21.88  339.03   39.45  339.14
    59.2   338.9   84.71  338.27   93.97  338.39   99.23  335.91  100.76  335.82
  106.56  335.98  108.28  337.14  109.04  338.31  124.79  338.24  146.31  338.95
   163.9  338.73  164.34  339.68  176.38  339.83   221.8  339.76  252.17  339.34
  260.89  339.58  272.13  339.58  312.67  339.33  350.37  340.37  366.31  344.55
#Mann= 3 , 0 , 0
       0      .1       0   93.97    .035       0  109.04     .08       0
#Block Obstruct= 6 ,-1
   27.52   35.49342.0646  271.67  310.54342.4639  152.57  164.87342.2979
    50.8   60.03341.9404  122.69  126.81341.3354  128.89  146.45341.6966
Bank Sta=93.97,109.04
XS Rating Curve= 0 ,0
Exp/Cntr=0.3,0.1

Type RM Length L Ch R = 1 ,15631.9 ,68.16,70,69.66
XS GIS Cut Line= 4
    -611320.9068    -1045987.247-611337.76359999   -1045880.4979
     -611336.416   -1045863.3839-611391.28819999   -1045657.6723
#Sta/Elev= 30
       0  345.78    4.26   345.8    8.12  340.29    8.79  339.72   13.84  339.28
   22.41  339.13   36.61  339.12    68.1  338.29   99.75     338  111.14  337.11
  112.54  336.08   113.8  335.69  116.58  335.51  118.99  335.63  119.37  335.74
  119.97  336.28  122.34   337.8  138.09   338.1  143.49  338.46  150.51  339.09
  159.72  339.49  173.52  339.67   237.3  339.28  251.22  339.05  283.94  339.12
  297.23   339.3   328.6  338.99  329.16  339.13  335.85  344.28  338.14  346.69
#Mann= 3 , 0 , 0
       0      .1       0  111.14     .05       0  122.34     .08       0
#Block Obstruct= 6 ,-1
  152.28  152.78342.1754  215.97  233.24342.3452   299.1  316.38342.1783
    9.04   26.27342.4084  250.37  268.44342.1011   37.43   50.46341.9418
Bank Sta=111.14,122.34
XS Rating Curve= 0 ,0
Exp/Cntr=0.3,0.1

Type RM Length L Ch R = 1 ,15561.9 ,53.46,64.01,67.42
XS GIS Cut Line= 4
    -611358.8707   -1045988.0799    -611405.7524    -1045878.675
    -611406.3202   -1045860.2644    -611458.7895   -1045675.2631
#Sta/Elev= 30
       0   341.7    4.67   338.9   26.16   338.6   59.88  337.86   80.08  337.85
   90.31  338.07  106.36  337.78  119.03  336.85  122.37   336.7  124.27  335.48
  124.95  335.22  125.54  335.16  130.74  335.17  135.33  337.56  143.34  337.94
  147.09  337.98  153.27  338.51  156.65  338.68  168.99  338.86  184.41  338.77
  191.45  341.07  198.78  340.67  200.07  340.32   200.5  340.32  205.32  338.97
  229.63  338.84  253.98  338.88  316.49  339.24  324.73  343.67  329.74  346.06
#Mann= 3 , 0 , 0
       0      .1       0  122.37     .05       0  135.33     .08       0
#Block Obstruct= 3 ,-1
  205.92  209.34341.9575  240.57  312.66342.0353  149.11  173.16341.4943
Bank Sta=122.37,135.33
XS Rating Curve= 0 ,0
Exp/Cntr=0.3,0.1

Type RM Length L Ch R = 1 ,15497.89,71.41,68.84,61.12
XS GIS Cut Line= 4
    -611388.0808   -1046008.0824-611450.05429999   -1045910.2353
    -611464.6264   -1045897.6141-611531.03799999   -1045697.5967
#Sta/Elev= 30
       0  343.02    7.58  338.97   14.28   338.4   18.37  338.17   28.88  338.29
    41.5  337.97   51.98  338.04   71.06  337.56   86.16  337.94   92.48   337.9
   96.01  337.26    96.3   337.4  100.78  337.22  101.05  337.03  115.82   336.4
  118.38  336.19  121.39  335.42  122.33  334.52  123.98  334.45  128.49  334.54
  131.27  335.06   133.2  336.84   155.3  337.51   174.1  338.36  193.11  338.51
  204.62  338.79  316.85  338.92  337.63   339.2  341.76  339.63  345.85  343.04
#Mann= 3 , 0 , 0
       0      .1       0  115.82     .05       0   133.2     .08       0
#Block Obstruct= 1 ,-1
  167.34  180.95341.2631
Bank Sta=115.82,133.2
XS Rating Curve= 0 ,0
Exp/Cntr=0.3,0.1

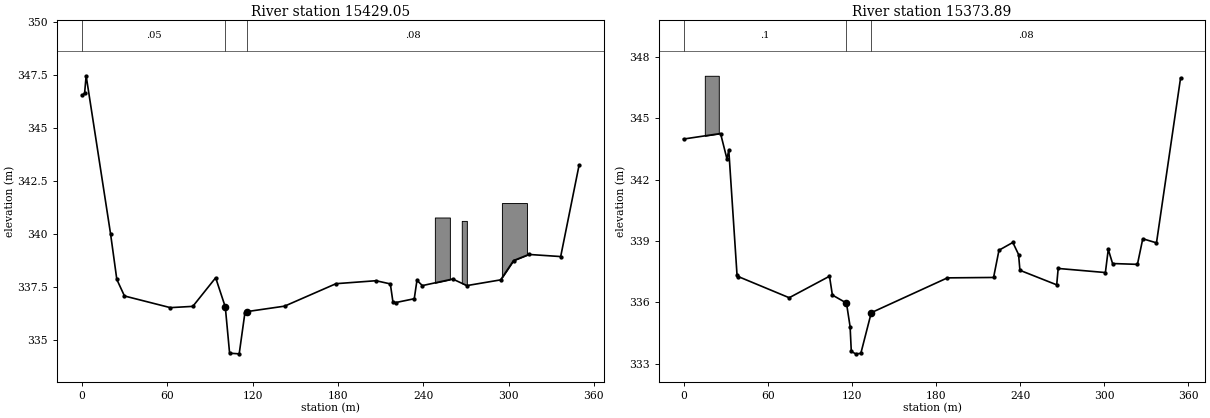
Type RM Length L Ch R = 1 ,15429.05,57.83,55.16,52.38
XS GIS Cut Line= 4
    -611467.2355   -1046053.0626    -611498.6151   -1045968.6868
-611508.26709999   -1045945.4035     -611594.204   -1045727.3864
#Sta/Elev= 30
       0  346.55    1.78  346.66    2.86  347.48   20.04  340.02   24.44  337.87
   29.81  337.09   62.06  336.54   77.89   336.6   93.96  337.95  100.74  336.57
  103.76  334.39  110.51  334.36  114.54   336.3  115.69  336.35  142.43  336.61
   178.6  337.67  206.71  337.81  216.82  337.66  218.69  336.79  220.66  336.78
  233.65  336.96  235.55  337.83  239.34  337.58   260.7  337.89  270.65  337.58
  294.39  337.85  303.46  338.76  314.24  339.05  336.64  338.95  349.57  343.26
#Mann= 3 , 0 , 0
       0     .05       0  100.74     .05       0  115.69     .08       0
#Block Obstruct= 3 ,-1
  248.14   258.7 340.793  267.07  270.64340.6323   295.3  312.91341.4743
Bank Sta=100.74,115.69
XS Rating Curve= 0 ,0
Exp/Cntr=0.3,0.1

Type RM Length L Ch R = 1 ,15373.89,10.94,373.89,55.99
XS GIS Cut Line= 4
    -611518.3532   -1046080.6446    -611558.4674   -1045974.2846
    -611559.0168   -1045956.5783    -611651.2961   -1045753.4009
#Sta/Elev= 30
       0  343.98   26.39  344.25   30.94  343.01   32.25  343.44   38.14  337.33
   39.14  337.26   75.35  336.23  104.09  337.28  106.16  336.36   116.2  335.97
  118.79  334.82  119.65  333.61  122.73  333.49  126.44  333.51   133.9   335.5
  188.19   337.2  221.15  337.22     225  338.55  234.88  338.93  238.98  338.34
  239.94  337.57  266.18  336.86  267.23  337.66  300.91  337.46  302.96  338.59
  306.04   337.9  323.77  337.86  327.58  339.11  337.36  338.91  354.54  346.96
#Mann= 3 , 0 , 0
       0      .1       0   116.2     .05       0   133.9     .08       0
#Block Obstruct= 1 ,-1
   15.15   25.12347.0693
Bank Sta=116.2,133.9
XS Rating Curve= 0 ,0
Exp/Cntr=0.3,0.1
LCMann Table=0

Chan Stop Cuts=-1
Use User Specified Reach Order=0
Composite Channel Slope=5

--- PPO_Kvasiny_efektiv.g01 (geometry) ---

Geom Title=N-Q5
Program Version=5.03

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
River Reach=Bela            ,Bela_reach

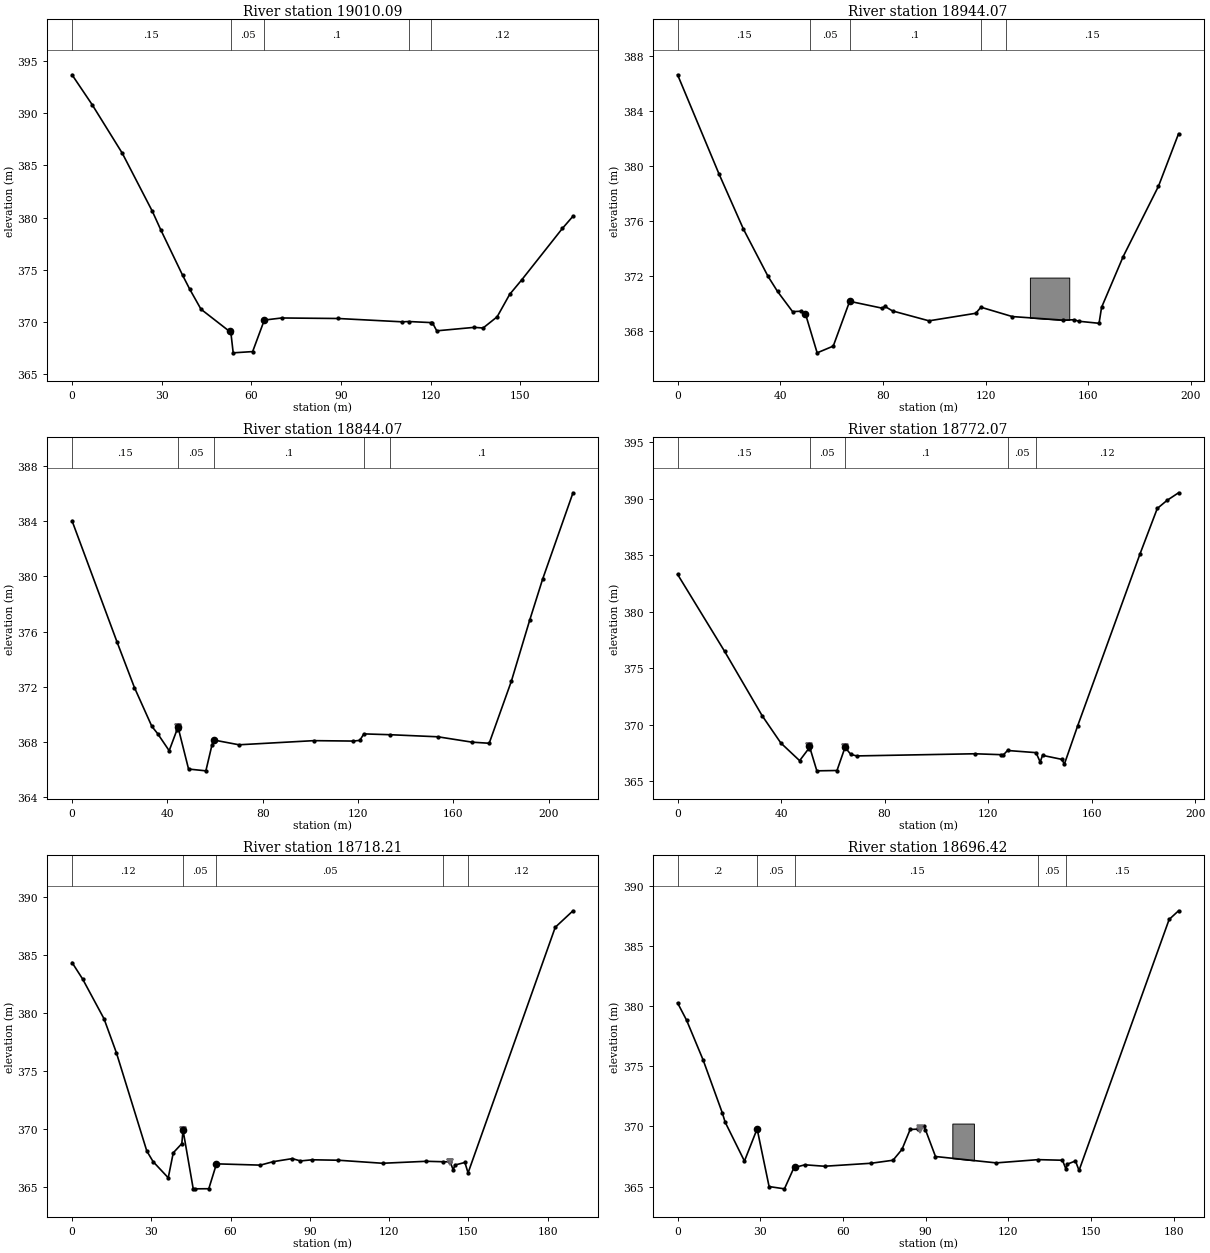
Type RM Length L Ch R = 1 ,19010.09,63.81,66.01,58.86
XS GIS Cut Line= 5
-608502.66209999   -1044593.6857    -608536.6251   -1044560.8986
     -608549.118   -1044545.2805    -608586.5786   -1044508.0775
     -608607.896   -1044465.4426
#Sta/Elev= 27
       0  393.68    6.75  390.81   16.83  386.16    26.9  380.59   29.66  378.85
   36.98  374.49   39.39  373.14   43.16  371.22   52.73  369.09   53.17  368.96
   53.94  367.04   60.45  367.16   64.36  370.18   70.18  370.38   89.09  370.33
   110.6  370.01  112.68  370.04     120  369.94  120.58  369.94  122.07  369.15
  134.59  369.48  137.58  369.42  142.28  370.49  146.47  372.64  150.45  374.01
  164.12  378.96  167.67  380.13
#Mann= 5 ,-1 , 0
       0     .15       0   53.15     .05       0    64.4      .1       0
  112.68     .05       0     120     .12       0
Bank Sta=52.73,64.36
XS Rating Curve= 0 ,0
Exp/Cntr=0.3,0.1

Type RM Length L Ch R = 1 ,18944.07,107.06,100,81.52
XS GIS Cut Line= 5
    -608546.4782   -1044642.7763-608578.86259999   -1044608.0005
     -608594.864   -1044596.0024    -608642.9144   -1044514.1948
    -608653.0656   -1044483.0645
#Sta/Elev= 26
       0  386.63   16.09  379.43   25.66  375.39   35.22  371.96   38.92  370.86
   44.79  369.39   48.23  369.42    49.8  369.23   54.36  366.39   60.63  366.88
   67.02  370.14   79.71  369.64   80.76  369.77   83.72  369.44   97.93  368.72
  116.15  369.27  118.16  369.71  130.38  369.03  150.14  368.77  154.47   368.8
  156.24  368.69  164.17  368.54  165.15   369.7  173.57   373.4  187.32  378.52
  195.14  382.34
#Mann= 5 ,-1 , 0
       0     .15       0   51.56     .05       0   67.03      .1       0
  118.16     .05       0   127.9     .15       0
#Block Obstruct= 1 ,-1
  137.23  152.56371.8682
Bank Sta=49.8,67.02
XS Rating Curve= 0 ,0
Exp/Cntr=0.3,0.1

Type RM Length L Ch R = 1 ,18844.07,72.16,72,73.34
XS GIS Cut Line= 6
-608649.34349999   -1044712.1427    -608661.1943   -1044671.2681
    -608666.6842   -1044652.0363-608687.57959999     -1044587.96
    -608711.2657   -1044551.4157    -608740.0273   -1044528.7448
#Sta/Elev= 26
       0  384.04   18.89  375.24   26.18  371.94   33.47  369.13    35.9   368.6
   40.75  367.36   44.03  368.88   44.31  369.11   44.67  368.93   48.88  366.03
   56.14   365.9   58.65  367.74   59.34  368.14   70.03  367.79  101.43  368.09
     118  368.06  120.69  368.11  122.41  368.58  133.48  368.52  153.46  368.37
  167.81  367.98  174.98   367.9  184.29  372.41  191.95  376.82  197.36  379.79
  210.13  386.07
#Mann= 5 ,-1 , 0
       0     .15       0   44.35     .05       0   59.46      .1       0
  122.41     .05       0  133.48      .1       0
Levee=-1,44.3,369.1,0,,,,
Bank Sta=44.31,59.34
XS Rating Curve= 0 ,0
Exp/Cntr=0.3,0.1

Type RM Length L Ch R = 1 ,18772.07,49.5,53.87,46.34
XS GIS Cut Line= 5
-608717.01799999   -1044739.5508    -608729.3973    -1044693.413
    -608735.3242   -1044674.3114    -608762.3599   -1044598.1112
    -608783.6774   -1044558.5216
#Sta/Elev= 26
       0  383.29   18.17  376.48   32.67  370.79   39.91  368.37   47.16  366.81
   50.67  367.88   50.91  368.11   53.81  365.91    61.6  365.94   64.71  367.99
   66.95  367.36   69.23  367.23  114.85  367.42     125  367.34  125.72  367.28
   127.5  367.71  138.51  367.52  140.12  366.69  141.02  367.28  148.38  366.93
  149.49  366.52  154.63  369.91  178.71  385.11  185.36  389.12  189.15  389.84
  193.59  390.51
#Mann= 5 ,-1 , 0
       0     .15       0   50.99     .05       0    64.7      .1       0
   127.5     .05       0  138.51     .12       0
Levee=-1,50.87,368.11,-1,64.69,367.98,,
Bank Sta=50.91,64.71
XS Rating Curve= 0 ,0
Exp/Cntr=0.3,0.1

Type RM Length L Ch R = 1 ,18718.21,29.06,21.79,6.52
XS GIS Cut Line= 5
-608753.54699999   -1044753.4637     -608781.487   -1044705.5211
    -608789.4245   -1044670.2786    -608798.9496    -1044622.336
-608821.80959999   -1044578.8384
#Sta/Elev= 30
       0  384.35    4.01  382.93   12.11  379.51   16.79  376.59   28.31  368.13
   30.69  367.22   36.42  365.83   38.32  367.98   41.56  368.77   42.02  369.93
   45.86   364.9   46.37  364.88   51.77  364.89   54.68  367.03   71.29  366.92
    76.2  367.22   83.37  367.48   86.48  367.28   90.94  367.38  100.86  367.34
  117.53  367.08  134.11  367.25  140.49  367.21  143.13   367.2  144.27  366.52
  144.99  366.93  148.71  367.15  149.91  366.25  182.91  387.38  189.63   388.8
#Mann= 5 ,-1 , 0
       0     .12       0   42.02     .05       0   54.68     .05       0
  140.49     .05       0  149.91     .12       0
Levee=-1,42.02,369.93,-1,142.96,367.15,,
Bank Sta=42.02,54.68
XS Rating Curve= 0 ,0
Exp/Cntr=0.3,0.1

Type RM Length L Ch R = 1 ,18696.42,50.22,38.35,4.09
XS GIS Cut Line= 4
-608796.05849999    -1044760.252    -608795.7939   -1044693.8414
    -608803.2023   -1044622.1392    -608824.1044   -1044584.3037
#Sta/Elev= 30
       0  380.28    3.25  378.85    9.27  375.53   16.25  371.11   17.25  370.36
   24.25  367.12   28.85   369.8   33.19     365   38.76  364.81   42.24  366.59
    42.5  366.59   46.19  366.81   53.31  366.69   70.21  366.94   78.14  367.19
   81.39  368.09   84.36  369.75   87.08  369.78   89.29     370   89.92  369.72
   93.55   367.5  115.58  366.97  130.78  367.24  139.61  367.19  140.83  366.48
  141.43  366.87  144.32  367.13  145.62  366.34   178.3  387.23  181.72  387.95
#Mann= 5 ,-1 , 0
       0      .2       0   28.85     .05       0    42.5     .15       0
  130.78     .05       0  140.83     .15       0
Levee=0,,,-1,87.99,369.73,,
#Block Obstruct= 1 ,-1
   99.66  107.48370.2419
Bank Sta=28.85,42.5
XS Rating Curve= 0 ,0
Exp/Cntr=0.3,0.1

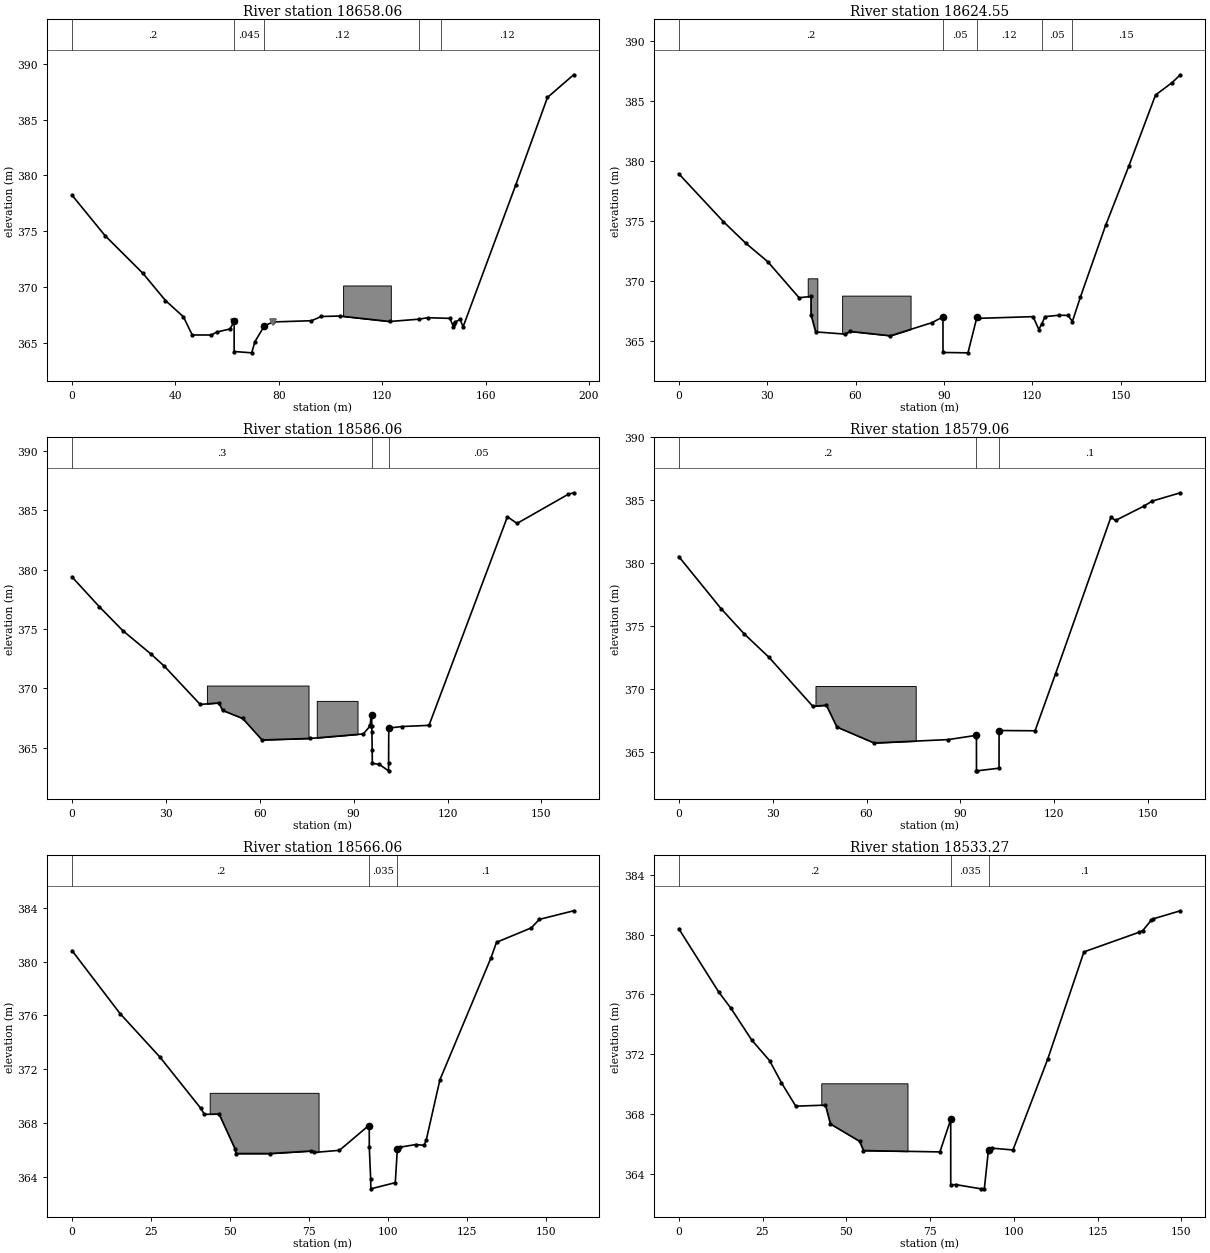
Type RM Length L Ch R = 1 ,18658.06,22,33.51,26.87
XS GIS Cut Line= 6
-608811.08549999    -1044755.116     -608825.589   -1044701.0257
    -608807.8792   -1044691.7325-608803.30299999   -1044664.7705
    -608806.6867   -1044622.1356-608834.09479999   -1044582.8844
#Sta/Elev= 30
       0  378.22   12.72  374.61   27.41  371.22   36.15  368.78    43.1  367.32
    46.5  365.69   53.84  365.69   56.09  365.96   61.11  366.23   62.71   366.9
   62.73  364.21   69.51  364.09   70.75  365.09   74.45  366.52   77.86  366.86
   92.64  366.97   96.45  367.35  103.66  367.39  122.92   366.9  134.34  367.11
  137.58  367.24  146.19  367.18  147.55  366.45  147.78  366.72  148.03  366.83
  150.17  367.09  151.31  366.42  171.67  379.13  183.96  386.99  194.08  389.02
#Mann= 5 ,-1 , 0
       0      .2       0   62.71    .045       0   74.46     .12       0
  134.34     .05       0   142.8     .12       0
Levee=-1,62.62,366.83,-1,77.85,366.86,,
#Block Obstruct= 1 ,-1
  104.88  123.34370.1295
Bank Sta=62.71,74.45
XS Rating Curve= 0 ,0
Exp/Cntr=0.3,0.1

Type RM Length L Ch R = 1 ,18624.55,27.54,38.49,47.2
XS GIS Cut Line= 6
    -608813.3292   -1044757.0751-608830.65819999   -1044713.3605
     -608838.708   -1044671.6675    -608829.9133   -1044663.7088
    -608830.5483   -1044653.6758    -608851.3869   -1044598.6741
#Sta/Elev= 30
       0  378.92   15.14  374.94   22.67  373.16    30.2  371.61   40.84  368.61
   44.87  368.72   44.88  367.19   46.46  365.77   56.35  365.59   58.15  365.81
   71.85  365.45   85.93  366.54   89.66  367.02   89.67  364.06   98.15  364.03
   101.2  367.01  101.96   366.9  120.26  367.04  122.19  365.97  123.18  366.43
  124.31  367.04  129.18  367.16  132.12  367.14  133.58  366.63  136.31  368.67
  144.85  374.62  152.76  379.57  161.81  385.47  167.38  386.49  170.22  387.15
#Mann= 5 ,-1 , 0
       0      .2       0   89.66     .05       0   101.2     .12       0
  123.18     .05       0  133.58     .15       0
#Block Obstruct= 2 ,-1
   43.76   47.02 370.226   55.44   78.67368.7872
Bank Sta=89.66,101.2
XS Rating Curve= 0 ,0
Exp/Cntr=0.3,0.1

Type RM Length L Ch R = 1 ,18586.06,7.01,7,6.98
XS GIS Cut Line= 5
-608816.16099999   -1044758.1613-608829.69599999   -1044721.9555
-608861.31879999   -1044682.8263    -608874.4763   -1044667.7636
    -608911.2437   -1044631.9484
#Sta/Elev= 30
       0  379.37    8.71  376.87   16.19  374.86   25.24  372.88   29.53  371.85
   40.95  368.64   46.89  368.77   48.11  368.14   54.53  367.46   60.71  365.65
    76.2  365.78   93.11  366.16   95.27  366.84   95.31  366.91   95.55  367.76
   95.77  367.75   95.78  366.84   95.83  366.33   95.91   364.8   95.96  363.68
   98.19  363.59  101.15  363.05  101.16   363.7  101.21  366.65  105.39  366.78
  114.07  366.88  139.13  384.44  142.21  383.88  158.54  386.33  160.29  386.46
#Mann= 3 , 0 , 0
       0      .3       0   95.77    .035       0  101.21     .05       0
#Block Obstruct= 2 ,-1
    78.2   91.23368.9392   43.09   75.57370.2309
Bank Sta=95.77,101.21
XS Rating Curve= 0 ,0
Exp/Cntr=0.3,0.1

Type RM Length L Ch R = 1 ,18579.06,11.58,13.01,14.24
XS GIS Cut Line= 5
-608821.51799999    -1044762.635    -608835.0529   -1044726.4292
    -608866.6757      -1044687.3    -608879.8332   -1044672.2374
-608916.60069999   -1044636.4221
#Sta/Elev= 22
       0  380.53   13.49   376.4   20.96  374.38   28.84  372.53   42.84  368.64
   47.15  368.73   50.53     367   62.43  365.73   86.13     366   95.11  366.34
   95.13  366.19   95.14  363.53    95.3  363.52  102.35  363.73  102.36  366.72
  113.86   366.7   120.4  371.22  138.11  383.66  139.57  383.39  148.64  384.53
  151.29  384.93  160.29  385.59
#Mann= 3 , 0 , 0
       0      .2       0   95.11    .035       0  102.36      .1       0
#Block Obstruct= 1 ,-1
   43.69   75.72 370.257
Bank Sta=95.11,102.36
XS Rating Curve= 0 ,0
Exp/Cntr=0.3,0.1

Type RM Length L Ch R = 1 ,18566.06,31.65,32.78,32.95
XS GIS Cut Line= 5
-608821.57499999   -1044763.5753    -608827.6657   -1044750.7171
-608875.58549999   -1044694.5559    -608890.8203   -1044681.5982
-608930.53099999   -1044650.2205
#Sta/Elev= 29
       0  380.81   15.17  376.14   27.74  372.92   40.72   369.1   41.86  368.65
    46.5  368.68   51.51  366.11   51.86  365.74    62.5  365.74   75.63  365.93
   76.44  365.82   84.59  365.98   93.69  367.79   94.02  367.78   94.03  366.24
   94.46  363.86   94.53  363.12  102.25  363.58  102.91  366.09  103.89  366.22
  108.79  366.41  111.38  366.35  112.06  366.76  116.37  371.22  132.52  380.27
  134.28  381.43  145.28   382.5  147.82  383.13  158.67  383.77
#Mann= 3 , 0 , 0
       0      .2       0   94.02    .035       0  102.91      .1       0
#Block Obstruct= 1 ,-1
   43.54   77.98370.2509
Bank Sta=94.02,102.91
XS Rating Curve= 0 ,0
Exp/Cntr=0.3,0.1

Type RM Length L Ch R = 1 ,18533.27,12.87,12.37,12.43
XS GIS Cut Line= 4
    -608836.7278   -1044771.9928-608886.99879999   -1044726.4844
    -608909.2238   -1044709.0218    -608949.4406   -1044673.5676
#Sta/Elev= 28
       0   380.4   11.91  376.17   15.57  375.08   21.75  372.96   27.09  371.58
   30.64   370.1   34.92  368.53   43.78   368.6   45.25  367.34   53.98  366.18
   55.12  365.56   77.94  365.47   81.16  367.64   81.17  363.27   82.75  363.28
   90.22     363    91.2  363.02   92.37  365.49   92.53   365.6   93.52  365.72
   99.74   365.6   110.1  371.67  120.92  378.85  137.46  380.17  138.48  380.28
  141.03  380.97  141.59  381.06  149.69   381.6
#Mann= 3 , 0 , 0
       0      .2       0   81.16    .035       0   92.53      .1       0
#Block Obstruct= 1 ,-1
   42.53   68.26370.0591
Bank Sta=81.16,92.53
XS Rating Curve= 0 ,0
Exp/Cntr=0.3,0.1