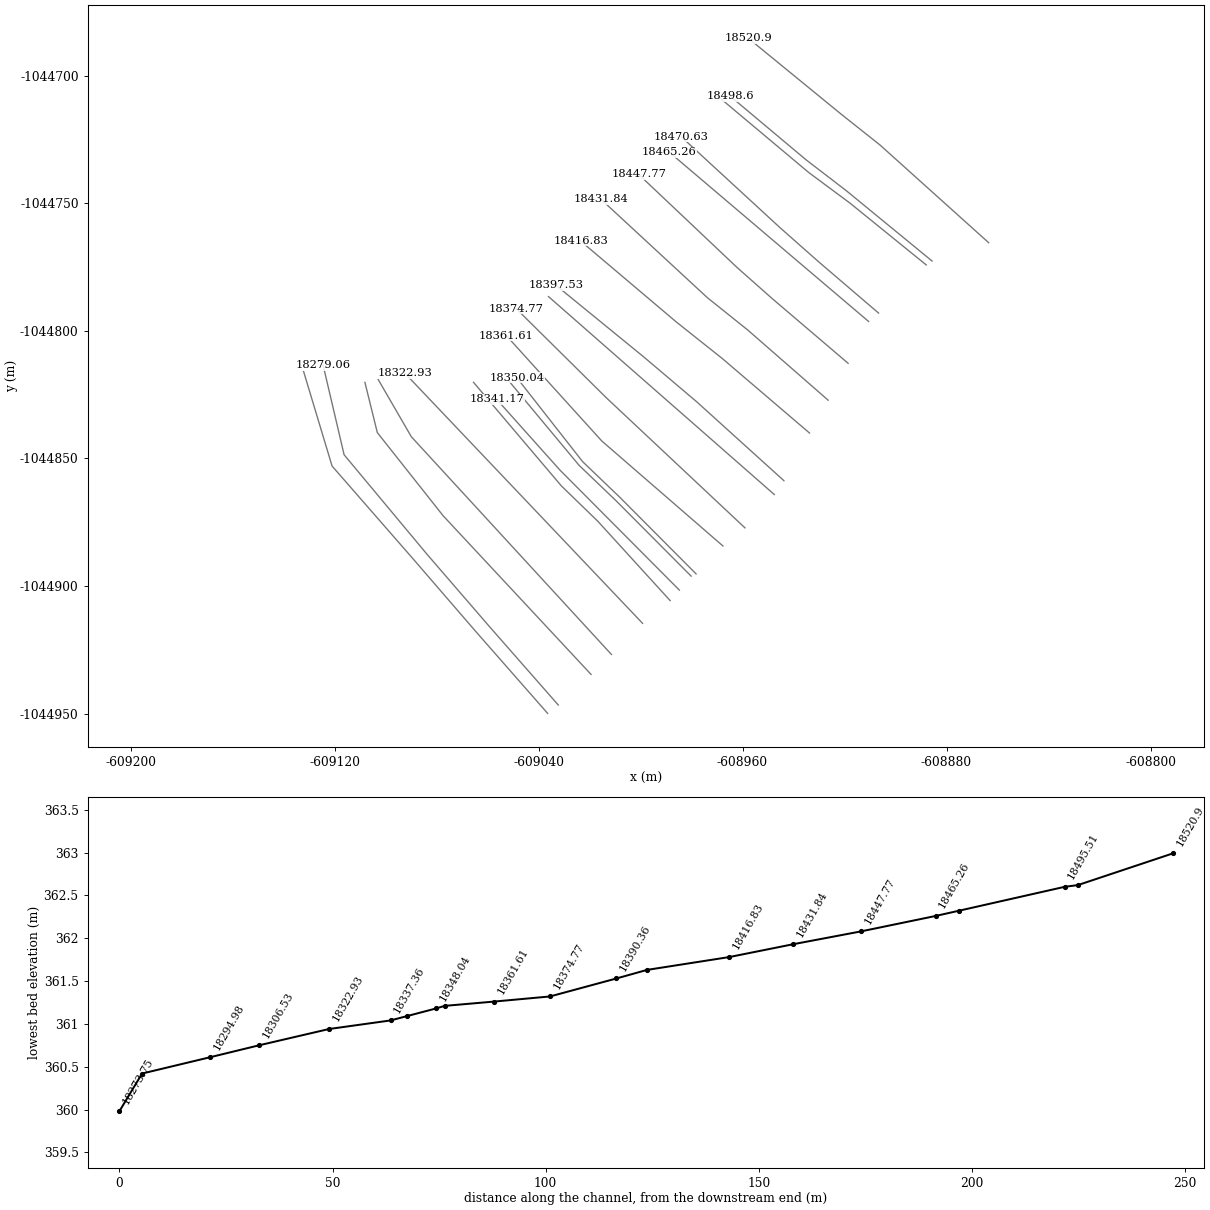
HEC-RAS study PPO_Kvasiny_efektiv.prj: PPO_Kvasiny_efektivita

--- PPO_Kvasiny_efektiv.g01 (geometry) --- (continued)

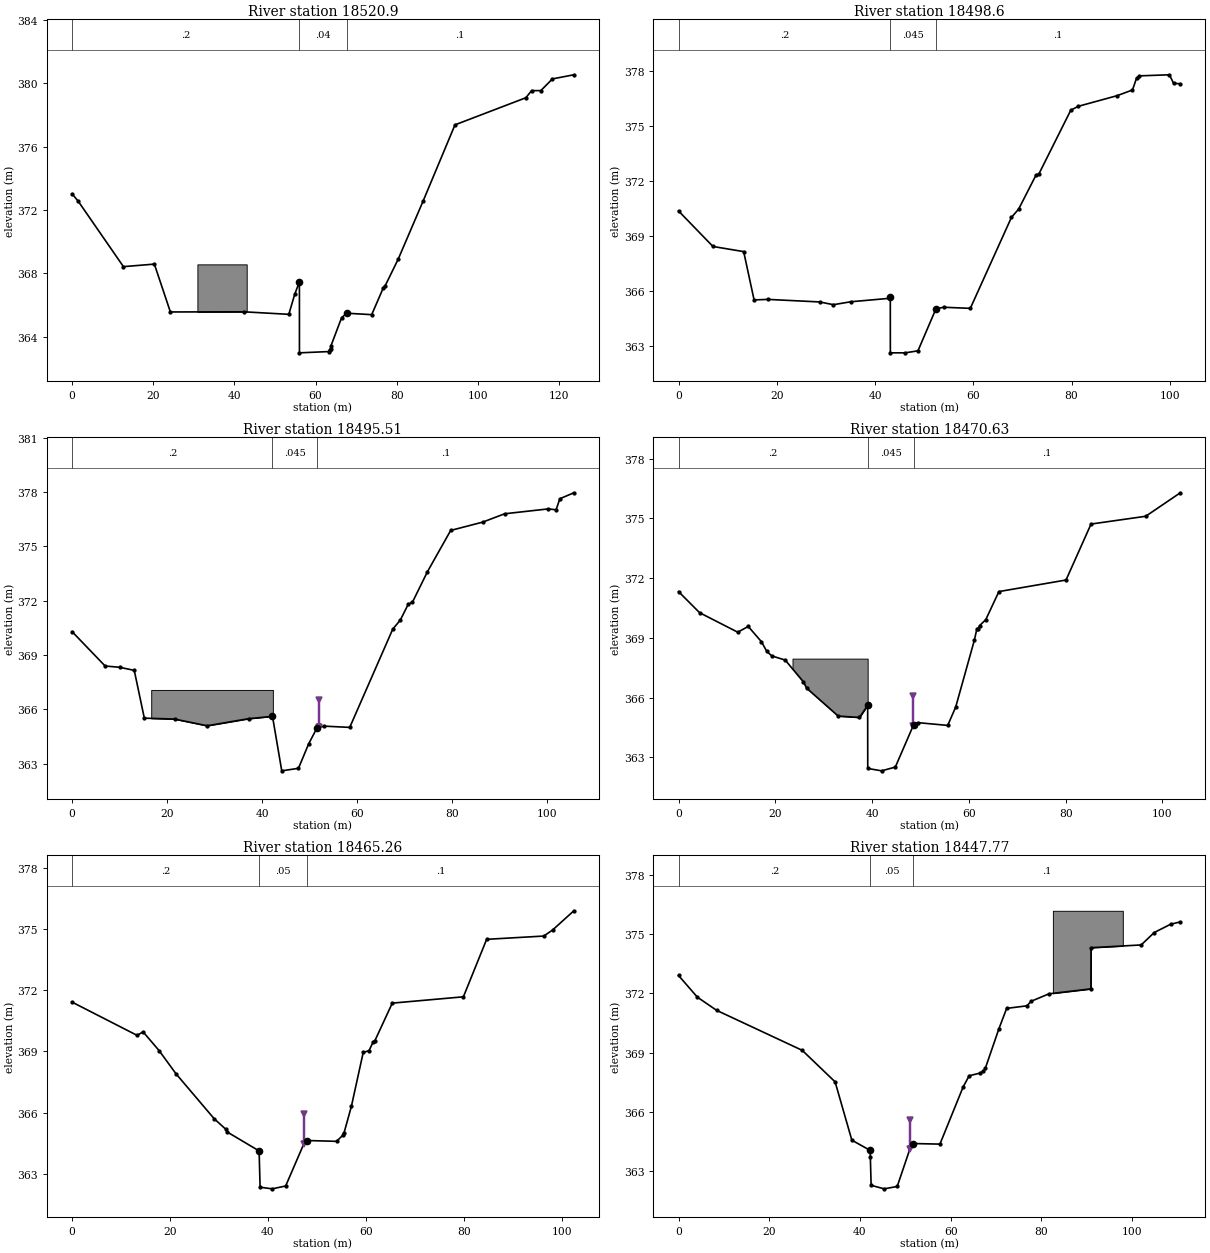
Type RM Length L Ch R = 1 ,18520.9 ,21.89,22.29,22.52
XS GIS Cut Line= 4
    -608863.4842   -1044765.4406-608906.08109999   -1044727.1808
-608921.42689999     -1044715.01    -608957.6926   -1044685.3842
#Sta/Elev= 27
       0  373.03    1.54  372.55   12.66  368.43   20.28  368.59   24.23  365.57
   42.35  365.58   53.42  365.42   54.89   366.7   56.03  367.47   56.04  362.99
   63.28  363.07   63.48   363.2   63.73  363.25   63.82  363.44   66.43  365.21
   67.69  365.49   73.85   365.4   76.67  367.07   77.16  367.22   80.37   368.9
    86.5  372.56   94.37  377.38  111.84  379.09  113.26  379.54  115.53  379.54
  118.39  380.28  123.67  380.54
#Mann= 3 , 0 , 0
       0      .2       0   56.03     .04       0   67.69      .1       0
#Block Obstruct= 1 ,-1
   30.89   43.04368.5746
Bank Sta=56.03,67.69
XS Rating Curve= 0 ,0
Exp/Cntr=0.3,0.1

Type RM Length L Ch R = 1 ,18498.6 ,2.83,3.09,3.31
XS GIS Cut Line= 4
    -608885.6669   -1044772.6373    -608919.2351   -1044745.1325
    -608935.1101   -1044732.9616    -608964.8046   -1044708.0749
#Sta/Elev= 29
       0  370.37    7.01  368.43   13.26  368.15   15.38  365.51   18.15  365.54
   28.73   365.4   31.54  365.25   35.05  365.41   43.04   365.6   43.11  365.66
   43.12  362.62   46.14  362.62   48.74  362.73   52.41  365.03   53.99  365.11
    59.4  365.05   67.77  370.02   69.23  370.47   72.79  372.34   73.35  372.39
   79.86  375.88   81.41  376.09    89.3  376.67   92.41  376.98   93.25  377.63
   93.77  377.75   99.93  377.81  100.78  377.34  102.15  377.32
#Mann= 3 , 0 , 0
       0      .2       0   43.11    .045       0   52.41      .1       0
Bank Sta=43.11,52.41
XS Rating Curve= 0 ,0
Exp/Cntr=0.3,0.1

Type RM Length L Ch R = 1 ,18495.51,25.6,24.88,23.57
XS GIS Cut Line= 4
    -608887.9529   -1044774.1613    -608917.6792   -1044750.0879
    -608934.0835    -1044737.917    -608970.0669   -1044707.7544
#Sta/Elev= 27
       0  370.29    6.96  368.39   10.03  368.32   13.09  368.15   15.21  365.51
   21.57  365.46   28.43  365.09   37.14  365.48   42.19  365.61   44.14   362.6
   47.66  362.74   49.82   364.1   51.54  364.96   53.01  365.07   58.45     365
   67.51  370.43    69.1  370.93    70.8  371.82   71.62   371.9   74.81   373.6
    79.7  375.88   86.45  376.34   91.06   376.8  100.25  377.07  101.89  377.02
  102.68  377.63  105.63  377.96
#Mann= 3 , 0 , 0
       0      .2       0   42.19    .045       0   51.54      .1       0
Levee=0,,,-1,52.01,366.5074,,	2157
#Block Obstruct= 1 ,-1
   16.66   42.27367.0693
Bank Sta=42.19,51.54
XS Rating Curve= 0 ,0
Exp/Cntr=0.3,0.1

Type RM Length L Ch R = 1 ,18470.63,5.16,5.37,5.75
XS GIS Cut Line= 4
-608906.65179999   -1044793.0242    -608930.3372   -1044772.7807
-608945.32779999   -1044759.5411    -608983.9917   -1044723.9844
#Sta/Elev= 30
       0  371.32    4.35  370.26   12.24  369.28    14.4  369.57   17.14   368.8
   18.23  368.32   19.27  368.09   22.05  367.88   25.79  366.79   26.47  366.47
   32.99  365.07   37.38     365   39.08  365.61    39.1  362.44   41.97  362.32
    44.8  362.51   48.59  364.64   49.46  364.74   55.62   364.6   57.27  365.52
   61.13  368.88   61.66  369.46   61.92  369.46   62.21  369.61   63.49  369.91
    66.2  371.32   80.07   371.9   85.24  374.71   96.53   375.1  103.69  376.28
#Mann= 3 , 0 , 0
       0      .2       0   39.08    .045       0   48.59      .1       0
Levee=0,,,-1,48.46,366.0615,,	2157
#Block Obstruct= 1 ,-1
   23.55   39.08 367.954
Bank Sta=39.08,48.59
XS Rating Curve= 0 ,0
Exp/Cntr=0.3,0.1

Type RM Length L Ch R = 1 ,18465.26,17.65,17.49,17.14
XS GIS Cut Line= 2
    -608910.5632   -1044796.3117    -608988.7089   -1044730.0063
#Sta/Elev= 28
       0  371.42   13.27  369.79   14.51  369.96   17.78  369.04   21.24   367.9
   29.02   365.7   31.41  365.18   31.74  365.04    38.2  364.12    38.4  362.34
   40.87  362.26   43.62   362.4    47.5  364.56   48.04  364.63   54.01  364.59
    55.3  364.89   55.55  365.01   57.04   366.3   59.46  368.95   60.65  369.04
   61.48  369.46   61.85  369.53    65.4  371.37   79.92  371.68   84.67   374.5
   96.34  374.66   98.15  374.96  102.48   375.9
#Mann= 3 , 0 , 0
       0      .2       0    38.2     .05       0   48.04      .1       0
Levee=0,,,-1,47.29,365.9167,,	2157
Bank Sta=38.2,48.04
XS Rating Curve= 0 ,0
Exp/Cntr=0.3,0.1

Type RM Length L Ch R = 1 ,18447.77,15.66,15.93,16.64
XS GIS Cut Line= 4
-608918.60229999   -1044812.6923-608948.38219999   -1044787.3387
    -608962.1406   -1044775.1678    -609000.7698   -1044738.6552
#Sta/Elev= 30
       0  372.91    4.15  371.81     8.4  371.14   27.27  369.11   34.52  367.51
   38.21  364.55   42.26  364.03   42.29  363.69   42.46  362.26   45.32  362.08
   48.21   362.2   51.24  364.26   51.65  364.38   57.63  364.35   62.76  367.26
   64.08  367.82   66.39  367.95    67.2  368.05   67.64   368.2   70.61  370.19
   72.34  371.24   76.82  371.37   77.73   371.6   81.68  371.98   90.92  372.23
   90.94  374.32     102  374.46  104.88  375.09  108.48  375.51  110.63  375.63
#Mann= 3 , 0 , 0
       0      .2       0   42.26     .05       0   51.65      .1       0
Levee=0,,,-1,51.03,365.5753,,	2157
#Block Obstruct= 1 ,-1
   82.53   97.95376.1941
Bank Sta=42.26,51.65
XS Rating Curve= 0 ,0
Exp/Cntr=0.3,0.1

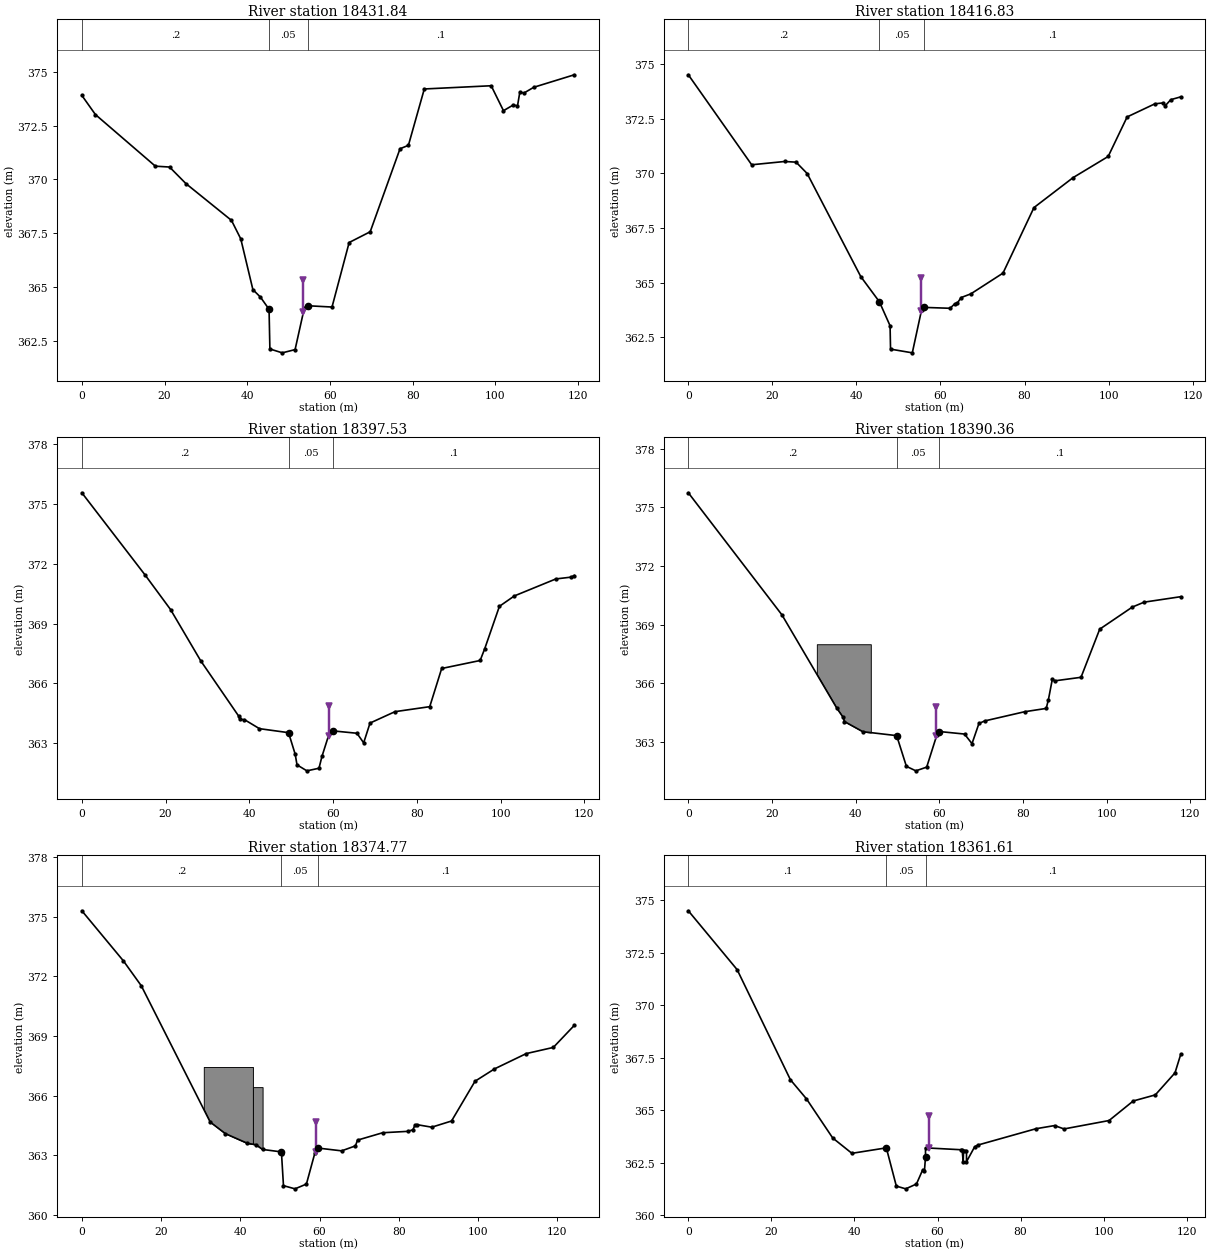
Type RM Length L Ch R = 1 ,18431.84,14.94,15.01,15.06
XS GIS Cut Line= 4
-608926.42619999   -1044827.1558    -608957.9395   -1044799.6768
-608973.81459999   -1044786.9768    -609015.6187   -1044748.3474
#Sta/Elev= 30
       0   373.9    3.28  373.01   17.77  370.61    21.2  370.57   25.16   369.8
   36.17  368.09   38.42  367.23   41.35  364.87   43.18  364.52   45.17  363.98
   45.26  363.94   45.46  362.11   48.45  361.93   51.55  362.08   53.78  364.01
   54.56  364.12   60.48  364.06   64.62  367.06   69.71  367.56   76.92  371.42
   78.95  371.58   82.79   374.2   98.96  374.35  101.93  373.19  104.34  373.46
  105.32  373.41  105.89  374.06  106.87  374.01  109.27  374.28  119.06  374.86
#Mann= 3 , 0 , 0
       0      .2       0   45.17     .05       0   54.56      .1       0
Levee=0,,,-1,53.56,365.304,,	2157
Bank Sta=45.17,54.56
XS Rating Curve= 0 ,0
Exp/Cntr=0.3,0.1

Type RM Length L Ch R = 1 ,18416.83,19.51,19.31,18.8
XS GIS Cut Line= 4
    -608933.7448   -1044840.0106    -608967.9937   -1044810.7893
-608985.98539999   -1044796.5017    -609023.5562   -1044764.7517
#Sta/Elev= 27
       0  374.51   15.08  370.39   22.91  370.54   25.64  370.51   28.28  369.99
   41.04  365.27   45.46  364.12   48.01  363.02   48.12  361.95    53.3  361.78
   55.49  363.73   56.19  363.86   62.29  363.82   63.37  364.02   64.02  364.06
   64.91  364.31   67.23  364.48   74.88  365.43   82.25  368.43   91.55   369.8
   99.91  370.77  104.42  372.58  111.02  373.18  112.87  373.22  113.53   373.1
   114.8  373.37  117.19   373.5
#Mann= 3 , 0 , 0
       0      .2       0   45.46     .05       0   56.19      .1       0
Levee=0,,,-1,55.47,365.2081,,	2157
Bank Sta=45.46,56.19
XS Rating Curve= 0 ,0
Exp/Cntr=0.3,0.1

Type RM Length L Ch R = 1 ,18397.53,7.24,7.17,6.9
XS GIS Cut Line= 4
-608943.77299999   -1044858.6939-608978.04789999   -1044827.7227
    -608998.6854   -1044810.2602    -609033.0813   -1044782.2143
#Sta/Elev= 29
       0  375.54   15.13  371.42   21.18   369.7   28.37  367.14   37.48  364.36
   37.74   364.2   38.84  364.19   42.41  363.74   49.36  363.54   50.95  362.46
   51.38  361.93   53.74  361.63   56.63  361.76   57.34  362.35   59.02  363.46
   59.91  363.63    65.7  363.51    67.3  363.03   68.82  364.02   74.78  364.59
   83.08  364.84   85.93  366.75   95.12  367.15   96.23  367.75   99.72  369.86
  103.29  370.38   113.2  371.23  116.84  371.32  117.61   371.4
#Mann= 3 , 0 , 0
       0      .2       0   49.36     .05       0   59.91      .1       0
Levee=0,,,-1,58.91,364.8894,,	2157
Bank Sta=49.36,59.91
XS Rating Curve= 0 ,0
Exp/Cntr=0.3,0.1

Type RM Length L Ch R = 1 ,18390.36,15.99,15.59,15.07
XS GIS Cut Line= 2
    -608947.5425   -1044864.1187-609036.10399999   -1044786.5639
#Sta/Elev= 26
       0  375.74   22.38   369.5    35.5  364.73   36.92  364.29   37.32  364.05
   41.73  363.53    49.8  363.33   52.13  361.76   54.39  361.53   56.98  361.72
   59.42  363.37   59.95  363.54   66.02  363.41   67.81  362.92   69.47  363.95
   70.84  364.08   80.38  364.55   85.55  364.72   86.08  365.17      87   366.2
   87.62  366.13   93.87  366.31   98.34  368.77  106.14   369.9  108.95  370.15
  117.72  370.43
#Mann= 3 , 0 , 0
       0      .2       0    49.8     .05       0   59.95      .1       0
Levee=0,,,-1,59.32,364.8086,,	2157
#Block Obstruct= 1 ,-1
   30.72   43.62368.0001
Bank Sta=49.8,59.95
XS Rating Curve= 0 ,0
Exp/Cntr=0.3,0.1

Type RM Length L Ch R = 1 ,18374.77,12.72,13.16,13.09
XS GIS Cut Line= 3
-608959.05689999   -1044877.1776-609013.50209999   -1044826.1352
-609048.81949999   -1044791.2347
#Sta/Elev= 30
       0   375.3   10.49  372.78      15  371.53   32.38  364.68   36.18   364.1
   41.76  363.61   43.91  363.54   45.61   363.3   50.25  363.18    50.4  363.05
   50.88  361.48   53.79  361.32   56.67  361.56   58.83  363.14   59.59  363.37
   65.56  363.23   69.04  363.48   69.57  363.77   75.91  364.14   82.26  364.21
   83.54  364.29   84.04  364.51   84.48  364.55    88.3  364.42   93.29  364.73
   99.22  366.73  104.13  367.35  112.15  368.12  118.98  368.43  124.28  369.54
#Mann= 3 , 0 , 0
       0      .2       0   50.25     .05       0   59.59      .1       0
Levee=0,,,-1,59.01,364.6792,,	2157
#Block Obstruct= 2 ,-1
   30.77   43.17367.4476   43.17   45.61366.4337
Bank Sta=50.25,59.59
XS Rating Curve= 0 ,0
Exp/Cntr=0.3,0.1

Type RM Length L Ch R = 1 ,18361.61,12.22,11.56,10.47
XS GIS Cut Line= 3
    -608967.6932   -1044884.2694     -609015.221   -1044843.1214
-609052.62759999   -1044801.8585
#Sta/Elev= 30
       0  374.49   11.75  371.69   24.58  366.45   28.45  365.54   34.76  363.68
   39.38  362.95   47.67  363.21   50.08  361.39   52.34  361.26   54.92  361.49
   56.46  362.18   56.84   362.1    57.1  362.77    57.1  363.21   65.69  363.12
   65.93  363.09   66.18  362.54   66.26  363.08   66.97  363.08   66.97  362.55
   68.93  363.26   69.65  363.34   83.69  364.12   88.17  364.27   90.45  364.11
  101.29  364.51  107.11  365.44  112.43  365.73  117.17  366.78  118.56  367.67
#Mann= 3 , 0 , 0
       0      .1       0   47.67     .05       0    57.1      .1       0
Levee=0,,,-1,57.89,364.7152,,	2157
Bank Sta=47.67,57.1
XS Rating Curve= 0 ,0
Exp/Cntr=0.3,0.1

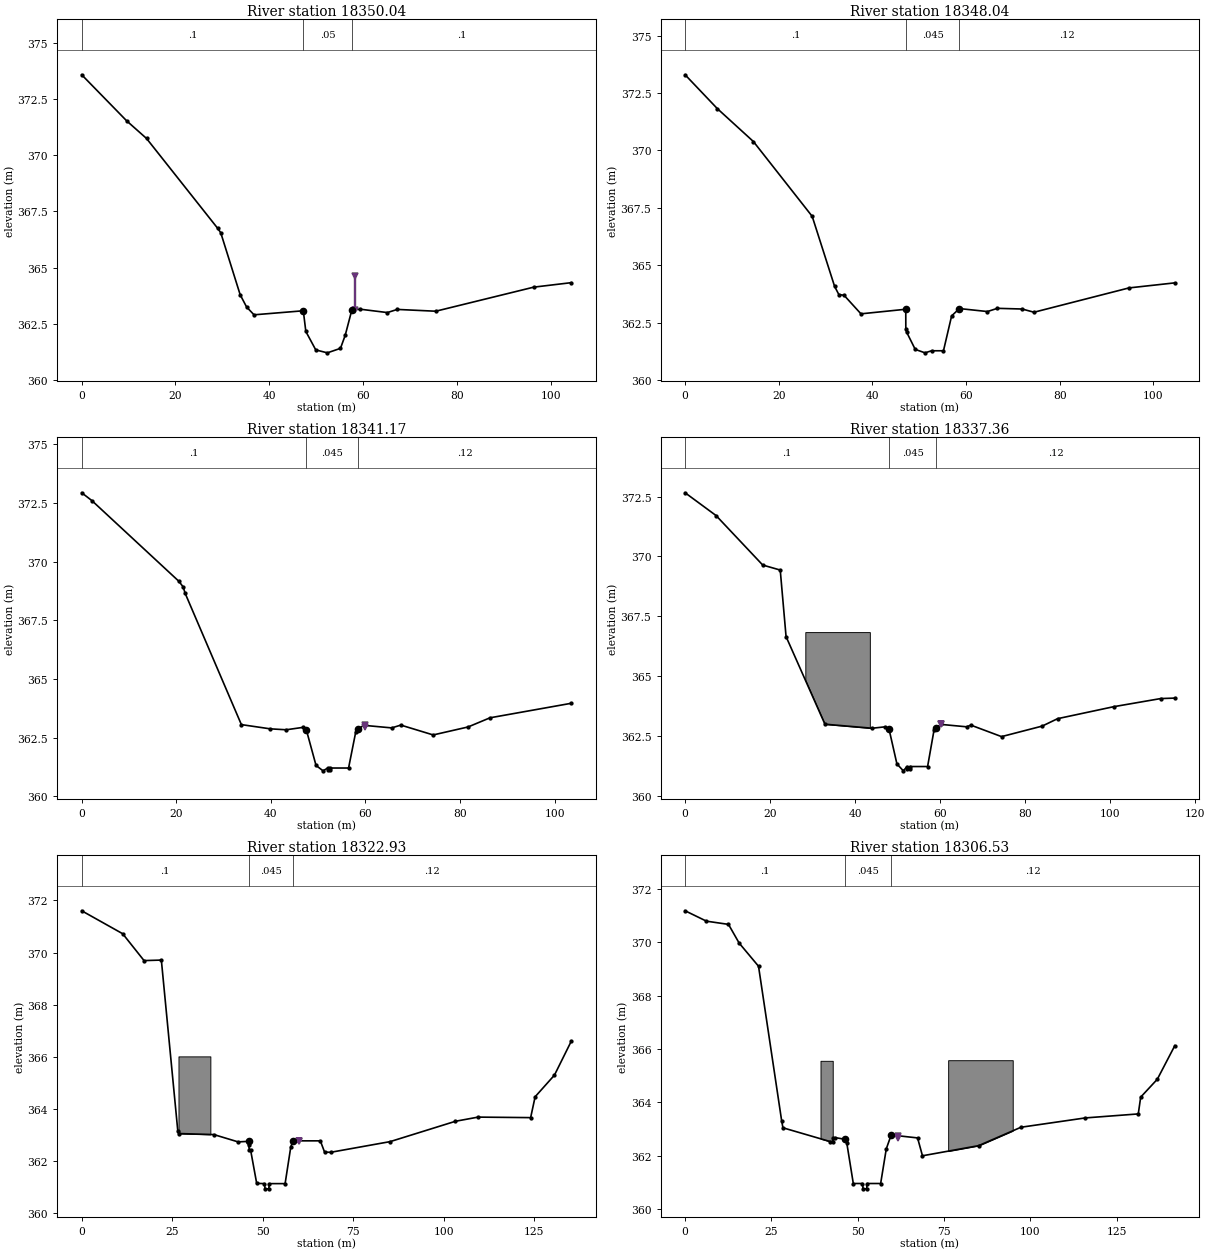
Type RM Length L Ch R = 1 ,18350.04,2,2,2.21
XS GIS Cut Line= 4
    -608978.2241   -1044895.2065    -609008.2817   -1044865.0536
-609022.72899999   -1044851.2234-609048.56549999   -1044818.2857
#Sta/Elev= 22
       0  373.57     9.6  371.52   13.82  370.74   28.98  366.75   29.65  366.55
    33.8  363.79   35.16  363.25   36.75   362.9   47.26  363.08    47.8  362.16
   49.92  361.34   52.39  361.21   55.19  361.41    56.2  361.99   57.62  363.12
   57.71  363.12   59.38  363.15   65.19     363    67.3  363.14   75.51  363.06
   96.41  364.13  104.44  364.33
#Mann= 3 , 0 , 0
       0      .1       0   47.26     .05       0   57.71      .1       0
Levee=0,,,-1,58.38,364.6284,,	2157
Bank Sta=47.26,57.71
XS Rating Curve= 0 ,0
Exp/Cntr=0.3,0.1

Type RM Length L Ch R = 1 ,18348.04,7.11,6.87,7.11
XS GIS Cut Line= 4
    -608980.1664   -1044896.0904     -609009.671   -1044866.4922
-609024.11829999    -1044852.662-609051.48649999   -1044819.8097
#Sta/Elev= 23
       0   373.3    6.85  371.83   14.58  370.39   27.13  367.13   31.91  364.08
   32.82  363.72   33.93  363.69   37.54  362.88   47.11  363.08   47.12  362.22
    47.3  362.08   49.13  361.33   51.22  361.18   52.62  361.27   55.16  361.27
    56.9  362.79   58.56  363.11   64.54  362.98   66.68  363.12   71.95  363.09
   74.49  362.95   94.77  364.01  104.55  364.23
#Mann= 3 , 0 , 0
       0      .1       0   47.11    .045       0   58.56     .12       0
Bank Sta=47.11,58.56
XS Rating Curve= 0 ,0
Exp/Cntr=0.3,0.1

Type RM Length L Ch R = 1 ,18341.17,3.64,3.82,3.48
XS GIS Cut Line= 3
    -608984.7855   -1044901.5539    -609031.6963   -1044854.4518
    -609056.4353   -1044826.8159
#Sta/Elev= 26
       0  372.94    2.13  372.61   20.54  369.17   21.45  368.93   21.89  368.65
   33.77  363.06   39.86  362.88   43.25  362.84   46.71  362.94   47.49  362.85
   49.56  361.32   51.05  361.09   52.02  361.21   52.09  361.14   52.43  361.14
    52.5  361.21   56.44  361.21   57.94  362.73   58.53  362.88   59.63  363.03
   65.57  362.92   67.49  363.04   74.34  362.62   81.72  362.96   86.35  363.35
  103.57  363.97
#Mann= 3 , 0 , 0
       0      .1       0   47.49    .045       0   58.53     .12       0
Levee=0,,,-1,59.93,362.97,,
Bank Sta=47.49,58.53
XS Rating Curve= 0 ,0
Exp/Cntr=0.3,0.1

Type RM Length L Ch R = 1 ,18337.36,14.84,14.42,14.55
XS GIS Cut Line= 4
     -608988.397   -1044905.6744    -609016.6957   -1044874.6581
-609031.05539999   -1044860.7368-609065.50409999   -1044820.1635
#Sta/Elev= 27
       0  372.66    7.27  371.71   18.26  369.64   22.38  369.43   23.75  366.65
   32.89  362.99   44.01  362.82   47.08  362.88   47.98  362.78   49.83  361.33
   51.34  361.04    52.2  361.22   52.32   361.1   52.89   361.1      53  361.22
   57.05  361.22   58.55  362.73   59.06  362.85   60.24  362.98   66.23  362.88
   67.23  362.95   74.45  362.47   84.01  362.91   87.64  363.22  100.82  363.72
  111.88  364.06  115.21  364.08
#Mann= 3 , 0 , 0
       0      .1       0   47.98    .045       0   59.06     .12       0
Levee=0,,,-1,60.21,362.99,,
#Block Obstruct= 1 ,-1
   28.28   43.46366.8377
Bank Sta=47.98,59.06
XS Rating Curve= 0 ,0
Exp/Cntr=0.3,0.1

Type RM Length L Ch R = 1 ,18322.93,16.56,16.4,16.08
XS GIS Cut Line= 2
    -608999.2052   -1044914.5843-609092.44469999   -1044816.5633
#Sta/Elev= 30
       0   371.6   11.32  370.72   17.22  369.69      22  369.71   26.56  363.14
   26.79  363.06   36.52  363.02    43.2  362.74   46.09  362.76   46.12  362.61
   46.35  362.41   46.64  362.44   48.34  361.15   50.46  361.14   50.66  360.94
   51.66  360.94   51.86  361.14   56.19  361.14   57.76  362.55   58.39  362.78
   65.92  362.78   67.09  362.35   68.75  362.34    85.2  362.75  103.25  363.53
   109.5  363.69  124.02  363.67  125.26  364.47   130.6   365.3  135.28  366.61
#Mann= 3 , 0 , 0
       0      .1       0   46.09    .045       0   58.39     .12       0
Levee=0,,,-1,59.92,362.76,,
#Block Obstruct= 1 ,-1
   26.73   35.54366.0181
Bank Sta=46.09,58.39
XS Rating Curve= 0 ,0
Exp/Cntr=0.3,0.1

Type RM Length L Ch R = 1 ,18306.53,11.47,11.55,11.69
XS GIS Cut Line= 3
-609011.42359999   -1044926.7722     -609089.892   -1044841.4859
-609102.89469999   -1044819.0525
#Sta/Elev= 30
       0  371.18    6.19  370.79   12.56  370.67   15.64  369.97   21.26   369.1
   27.95  363.31   28.33  363.04    42.1  362.52   42.75  362.52   42.97  362.64
   43.53  362.67   46.24  362.61   46.81  362.48   48.71  360.95   51.35  360.95
   51.55  360.75   52.55  360.75   52.75  360.95   56.63  360.95   58.26  362.25
   59.68  362.77   67.32  362.66   68.74  361.99   85.01  362.37   97.26  363.06
  115.89  363.41  131.24  363.56  131.94  364.19  136.75  364.86  141.82  366.12
#Mann= 3 , 0 , 0
       0      .1       0   46.24    .045       0   59.68     .12       0
Levee=0,,,-1,61.57,362.65,,
#Block Obstruct= 2 ,-1
   39.21   42.75365.5524   76.18   94.88 365.575
Bank Sta=46.24,59.68
XS Rating Curve= 0 ,0
Exp/Cntr=0.3,0.1

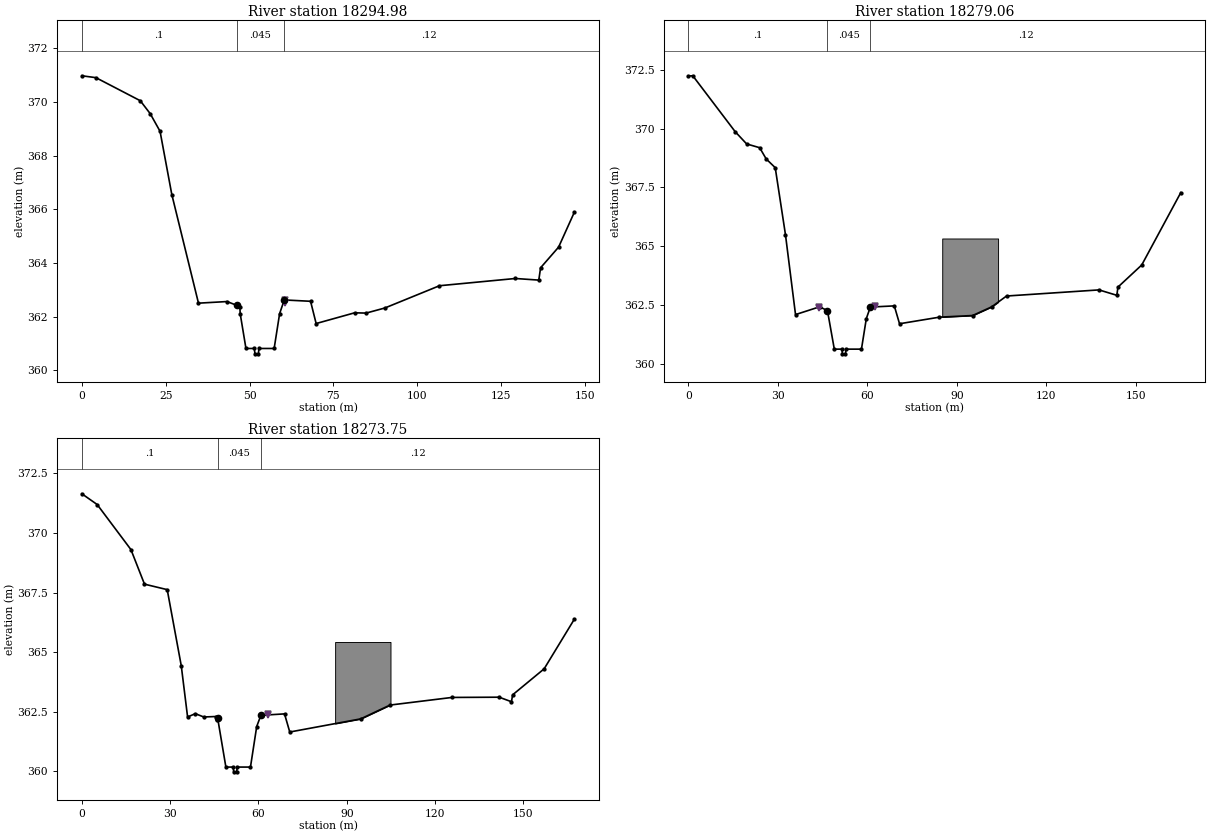
Type RM Length L Ch R = 1 ,18294.98,16.32,15.92,15.19
XS GIS Cut Line= 4
    -609019.4125   -1044934.5905    -609077.4164   -1044872.4435
    -609103.2397   -1044839.8467    -609108.1081   -1044820.1617
#Sta/Elev= 30
       0  370.98    4.19  370.91   17.42  370.05   20.37  369.57   23.32  368.91
   26.83  366.55   34.78   362.5    43.3  362.56   46.18  362.42   47.13  362.35
   47.22  362.11   48.94  360.81   51.43  360.81   51.63  360.61   52.63  360.61
   52.83  360.81   57.35  360.81   58.98  362.11   60.37  362.62   68.21  362.57
   69.87  361.74   81.35  362.14   84.78  362.13   90.37  362.32  106.65  363.15
  129.28  363.42  136.27  363.36  136.81  363.82  142.18  364.59  146.87  365.89
#Mann= 3 , 0 , 0
       0      .1       0   46.18    .045       0   60.37     .12       0
Levee=0,,,-1,60.73,362.5,,
Bank Sta=46.18,60.37
XS Rating Curve= 0 ,0
Exp/Cntr=0.3,0.1

Type RM Length L Ch R = 1 ,18279.06,5.31,5.32,5.33
XS GIS Cut Line= 5
-609032.27279999   -1044946.5812    -609059.4153   -1044915.6818
     -609083.818   -1044887.4375-609116.26419999   -1044848.5425
-609124.47399999   -1044813.5362
#Sta/Elev= 30
       0  372.24     1.5  372.25   15.72  369.87   19.55  369.35   23.91  369.19
   26.11  368.71   29.13  368.34   32.56  365.49   35.93  362.09   43.99  362.42
   46.63  362.26   48.93  360.62   51.46  360.62   51.66  360.42   52.66  360.42
   52.86  360.62   58.03  360.62   59.66  361.92   61.01  362.41   69.04  362.46
   70.79   361.7   84.14  361.98   95.28  362.05  101.69  362.42  106.65  362.88
  137.65  363.14  143.62  362.91     144  363.26  151.97   364.2  165.06  367.28
#Mann= 3 , 0 , 0
       0      .1       0   46.63    .045       0   61.01     .12       0
Levee=-1,43.75,362.38,-1,62.46,362.46,,
#Block Obstruct= 1 ,-1
    85.1  103.82365.3277
Bank Sta=46.63,61.01
XS Rating Curve= 0 ,0
Exp/Cntr=0.3,0.1

Type RM Length L Ch R = 1 ,18273.75,10.28,9.7,8.84
XS GIS Cut Line= 5
    -609036.4443   -1044949.8598-609064.65399999   -1044917.7456
-609089.05669999   -1044889.5013-609120.98169999   -1044852.9628
    -609132.1506   -1044815.9045
#Sta/Elev= 30
       0  371.64     5.2  371.19   16.67   369.3   21.28  367.85      29  367.62
   33.77  364.43   35.92  362.28   38.55  362.42   41.41  362.28    45.5   362.3
   45.88  362.16   46.12  362.24   48.93  360.18   51.39  360.18   51.59  359.98
   52.59  359.98   52.79  360.18   57.28  360.18    59.4  361.88   60.82  362.35
   68.85  362.41   70.63  361.65   94.71   362.2  104.69  362.78  125.75   363.1
  141.77  363.11  145.94  362.92  146.35  363.21  157.05   364.3   167.3  366.38
#Mann= 3 , 0 , 0
       0      .1       0   46.12    .045       0   60.82     .12       0
Levee=0,,,-1,63.29,362.42,,
#Block Obstruct= 1 ,-1
   86.04  104.85365.4245
Bank Sta=46.12,60.82
XS Rating Curve= 0 ,0
Exp/Cntr=0.3,0.1