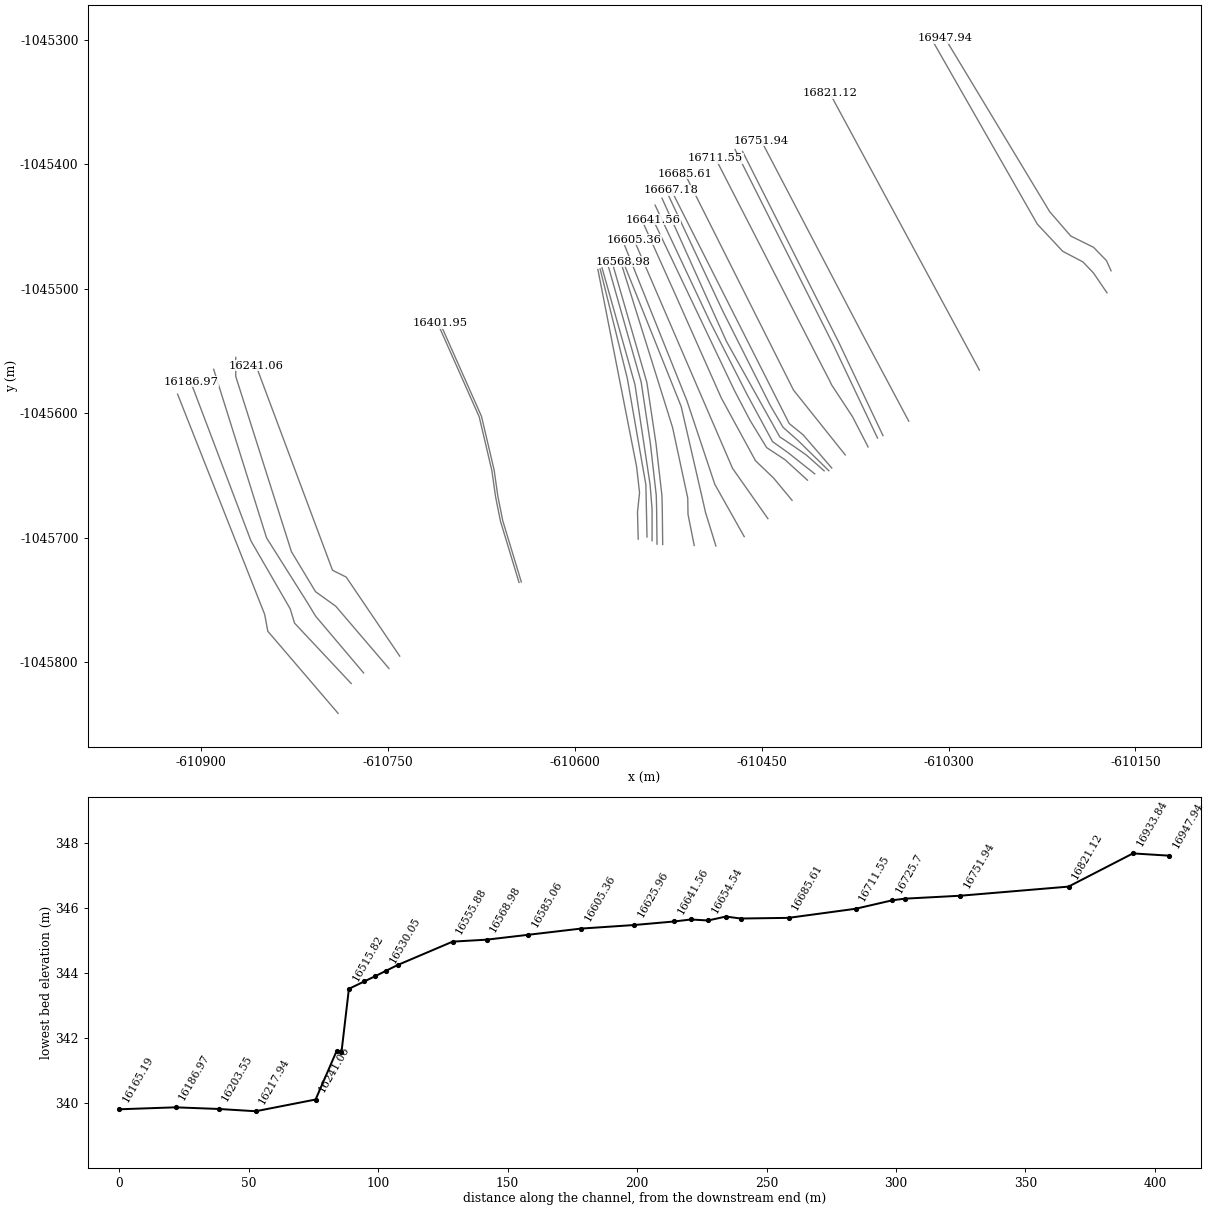
HEC-RAS study PPO_Kvasiny_efektiv.prj: PPO_Kvasiny_efektivita

--- PPO_Kvasiny_efektiv.g01 (geometry) --- (continued)

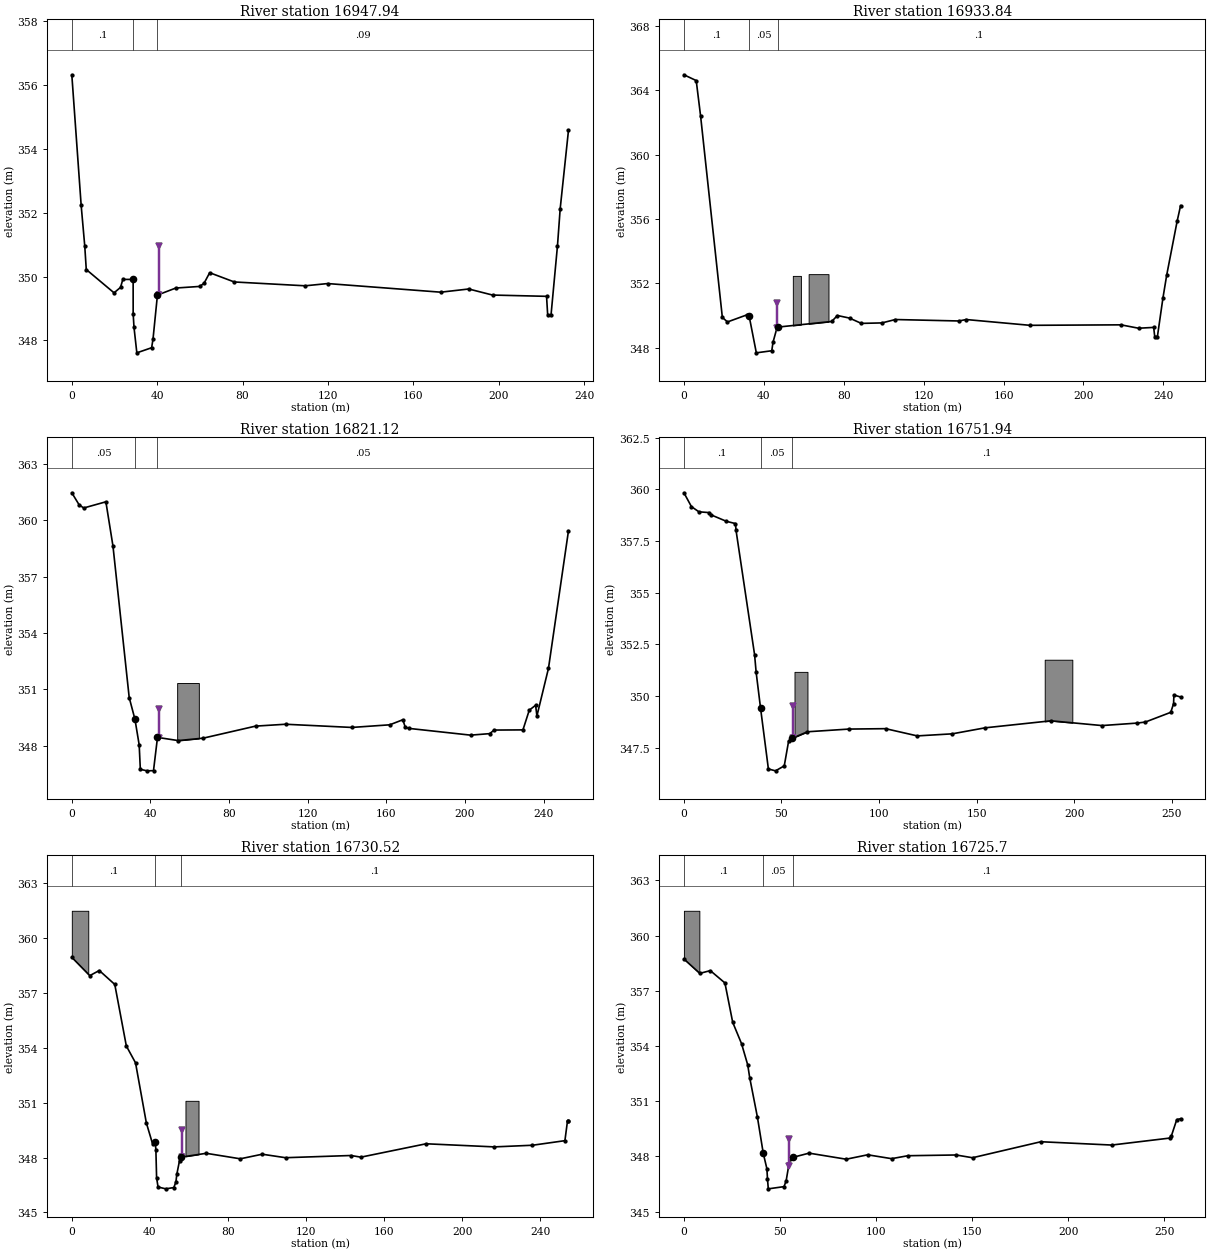
Type RM Length L Ch R = 1 ,16947.94,14.61,14.1,13.66
XS GIS Cut Line= 6
    -610169.5517   -1045485.6161-610173.24989999    -1045477.427
    -610183.6554   -1045466.7471-610201.92269999   -1045457.7056
    -610218.8174   -1045438.1758    -610302.8072   -1045298.9794
#Sta/Elev= 30
       0  356.32    4.38  352.23    6.07  350.95    6.77  350.22   19.78  349.49
   22.82  349.66    23.9  349.91   28.73  349.91   28.74  348.84   29.13  348.41
   30.46  347.61   37.39  347.77   38.04  348.04   40.11  349.42   48.72  349.64
   59.87  349.69   61.96  349.79   64.59  350.12   76.11  349.83  109.33  349.71
  119.86  349.78  172.83  349.51  185.94  349.61  197.09  349.42   222.4  349.38
  222.92   348.8   224.5   348.8  227.52  350.97  228.79  352.13  232.67  354.58
#Mann= 3 , 0 , 0
       0      .1       0   28.73    .045       0   40.11     .09       0
Levee=0,,,-1,40.75,350.9502,,	2158
Bank Sta=28.73,40.11
XS Rating Curve= 0 ,0
Exp/Cntr=0.3,0.1

Type RM Length L Ch R = 1 ,16933.84,27.14,24.89,15.43
XS GIS Cut Line= 6
    -610172.8312   -1045503.2958    -610183.6262   -1045487.4208
    -610192.1378   -1045478.4949    -610208.3665   -1045469.9668
    -610228.7441   -1045448.1827    -610312.5439   -1045301.5194
#Sta/Elev= 30
       0  364.96    6.16   364.6    8.34  362.41   19.24  349.88   21.81   349.6
   31.53  350.04   32.63  349.98   36.25  347.68   43.98  347.81    44.6  348.34
    46.6  349.24   47.05  349.28      74  349.63   76.83     350   82.89  349.84
    88.8  349.51   99.14  349.54  105.83  349.75  137.71  349.66  141.24  349.75
  173.25  349.39  218.78  349.42  227.56  349.21  235.14  349.26  235.67  348.69
  237.01  348.69  239.77  351.08  241.66  352.51   246.9  355.87  248.61  356.83
#Mann= 3 , 0 , 0
       0      .1       0   32.63     .05       0   47.05      .1       0
Levee=0,,,-1,46.74,350.7523,,	2158
#Block Obstruct= 2 ,-1
   54.52   58.56352.4616   62.43   72.37352.5712
Bank Sta=32.63,47.05
XS Rating Curve= 0 ,0
Exp/Cntr=0.3,0.1

Type RM Length L Ch R = 1 ,16821.12,43.01,41.79,41.65
XS GIS Cut Line= 2
-610275.27459999   -1045565.3143    -610395.3498   -1045343.0538
#Sta/Elev= 30
       0  361.46    3.71  360.82    6.05  360.65   17.33  360.98   20.94  358.62
   29.19  350.56   32.12   349.4   34.27  348.04   34.85  346.74   38.31  346.66
   41.55  346.67   43.58  348.44   54.15  348.27   66.86   348.4   93.44  349.04
  108.69  349.14  142.41  348.97  161.72  349.11  168.37  349.38   169.6  348.98
  171.36  348.92  202.82  348.56  212.54  348.64  214.81  348.83  229.46  348.84
  232.68  349.89   235.9  350.15  236.56  349.58  242.45  352.12  252.62  359.44
#Mann= 3 , 0 , 0
       0     .05       0   32.12     .05       0   43.58     .05       0
Levee=0,,,-1,44.24,349.9477,,	2158
#Block Obstruct= 1 ,-1
   53.58   64.61351.3344
Bank Sta=32.12,43.58
XS Rating Curve= 0 ,0
Exp/Cntr=0.3,0.1

Type RM Length L Ch R = 1 ,16751.94,21.77,21.42,20.49
XS GIS Cut Line= 3
-610331.99179999   -1045606.3583     -610368.002   -1045538.7669
    -610450.4891    -1045381.048
#Sta/Elev= 30
       0  359.83    3.86  359.16    7.68  358.91    13.1  358.87   13.71  358.77
   21.76  358.45   26.44  358.34   26.69  358.03   36.22     352   37.03  351.14
    39.3   349.4    43.3  346.47   46.95  346.38   51.43  346.62   53.67  347.82
   55.59  347.96   63.34  348.27    84.5   348.4  103.36  348.42  119.61  348.07
  137.55  348.17  154.31  348.46  188.11   348.8   214.3  348.57  232.32  348.69
   236.5  348.74  249.53  349.21  250.98  349.63  251.15  350.05  254.57  349.95
#Mann= 3 , 0 , 0
       0      .1       0    39.3     .05       0   55.59      .1       0
Levee=0,,,-1,56,349.5115,,	2158
#Block Obstruct= 2 ,-1
  184.93  199.08351.7553   56.68   63.33351.1675
Bank Sta=39.3,55.59
XS Rating Curve= 0 ,0
Exp/Cntr=0.3,0.1

Type RM Length L Ch R = 1 ,16730.52,4.86,4.82,4.85
XS GIS Cut Line= 3
    -610352.6812   -1045617.9347-610388.15709999   -1045543.0952
    -610465.3939   -1045389.8634
#Sta/Elev= 30
       0  358.93    9.19  357.93   14.08  358.21   22.01  357.45   27.93  354.09
   32.64  353.17   38.18  349.89   41.39  348.74   42.75  348.86   43.07   348.4
   43.43   346.9   44.17  346.39   48.14  346.29   52.25  346.36   53.34  346.67
   53.78  347.08   55.17  347.83   55.83  348.02   68.85  348.23    86.3  347.93
   97.54  348.18  109.47  347.99  142.98  348.11   148.1  348.02  181.48  348.75
  216.45  348.58  235.97  348.67  252.59  348.92  253.94  350.02  254.42  350.01
#Mann= 3 , 0 , 0
       0      .1       0   42.75     .05       0   55.83      .1       0
Levee=0,,,-1,56.44,349.5195,,	2158
#Block Obstruct= 2 ,-1
       0    8.43361.4715   58.22   64.91351.0959
Bank Sta=42.75,55.83
XS Rating Curve= 0 ,0
Exp/Cntr=0.3,0.1

Type RM Length L Ch R = 1 ,16725.7 ,12.99,14.15,15.54
XS GIS Cut Line= 3
-610357.07759999   -1045619.9076    -610392.5535   -1045545.0681
    -610471.4441   -1045388.2447
#Sta/Elev= 30
       0  358.73    8.25  357.95   13.74   358.1   21.33  357.43   25.38  355.29
   29.98  354.13   33.21  352.97   34.21  352.29   38.23  350.14   41.28  348.17
   43.17  347.33   43.48  346.77    43.9  346.24   52.08  346.36   53.19  346.68
   55.07  347.84   56.99  347.96   65.11  348.18   84.43  347.85   95.58  348.09
  108.04  347.88  116.51  348.04   141.6  348.08  150.14  347.93  185.69   348.8
  222.57  348.62  252.83     349  253.56  349.11  256.38     350  258.37  350.05
#Mann= 3 , 0 , 0
       0      .1       0   41.28     .05       0   56.99      .1       0
Levee=0,,,-1,54.48,348.9688,,	2161
#Block Obstruct= 1 ,-1
       0    8.03361.3521
Bank Sta=41.28,56.99
XS Rating Curve= 0 ,0
Exp/Cntr=0.3,0.1

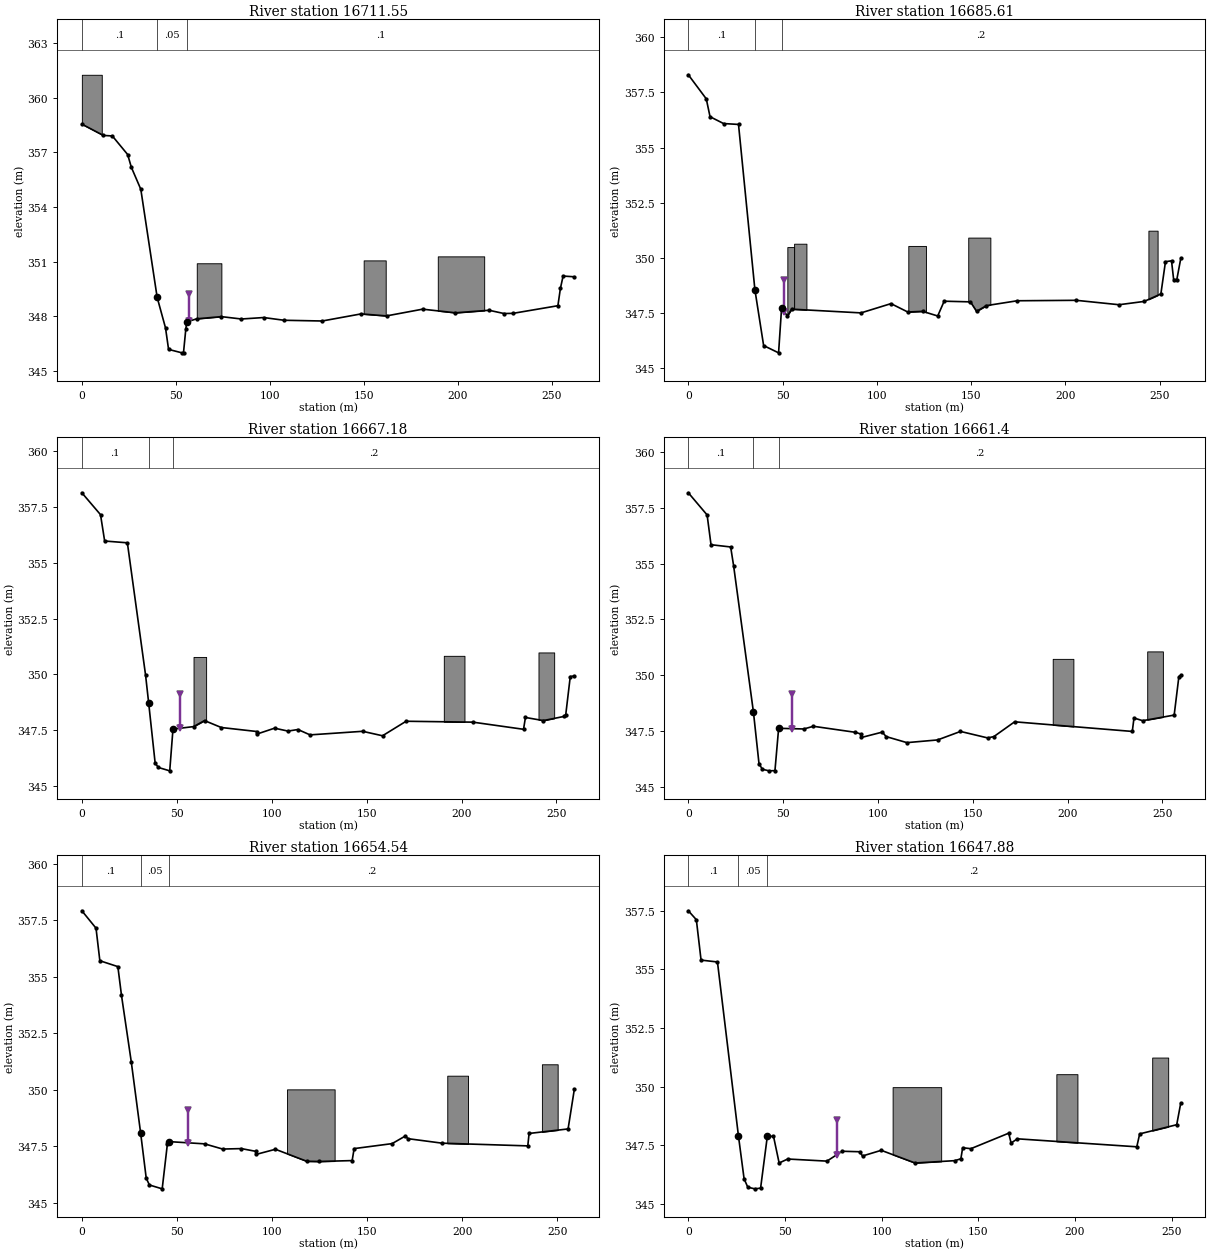
Type RM Length L Ch R = 1 ,16711.55,25.25,25.95,28.78
XS GIS Cut Line= 6
-610364.63259999   -1045627.0364    -610377.2875   -1045602.5042
-610393.99859999   -1045577.0942    -610395.3159   -1045574.2261
    -610401.3596   -1045562.6079    -610487.1075   -1045395.4414
#Sta/Elev= 30
       0  358.55   11.42  357.93   16.23   357.9   24.38  356.88   26.34  356.18
   31.38  354.97   40.08  349.03   44.53  347.35   46.16  346.17   53.25  345.98
   54.11  345.99   55.32  347.27   55.84  347.68   61.13  347.85   74.22  347.97
   84.94  347.84   96.79  347.92  107.67  347.77  127.94  347.73  148.62  348.12
  162.19  348.01  181.37  348.38  198.87  348.18  216.75  348.32  224.73  348.14
  229.48  348.15   253.4  348.57  254.72  349.52  256.17   350.2  262.14  350.16
#Mann= 3 , 0 , 0
       0      .1       0   40.08     .05       0   55.84      .1       0
Levee=0,,,-1,57.02,349.237,,	2161
#Block Obstruct= 4 ,-1
   61.17   74.27350.9031  150.01  161.74351.0612  189.46  214.16351.2825
       0    10.6361.2628
Bank Sta=40.08,55.84
XS Rating Curve= 0 ,0
Exp/Cntr=0.3,0.1

Type RM Length L Ch R = 1 ,16685.61,17.06,18.42,16.35
XS GIS Cut Line= 3
-610382.98559999   -1045633.4457-610424.52349999    -1045581.395
-610511.87249999   -1045407.5064
#Sta/Elev= 30
       0   358.3    9.52  357.21   11.52   356.4    18.7  356.09   26.62  356.05
   35.31  348.56   39.94  346.03   47.87   345.7   49.47  347.74   52.52  347.37
   54.79  347.68   91.59  347.51  107.49  347.93   116.4  347.55  124.24  347.58
  132.27  347.37  135.69  348.04  149.62  348.01  152.87  347.58   158.1  347.84
  174.46  348.06  205.73  348.08  228.44  347.88  241.77  348.03  250.63  348.37
  253.06  349.83  256.27  349.87   257.4  349.02  259.08  349.02  261.19  349.98
#Mann= 3 , 0 , 0
       0      .1       0   35.31     .05       0   49.47      .2       0
Levee=0,,,-1,50.97,348.9799,,	2161
#Block Obstruct= 5 ,-1
    56.1   62.64350.6454   52.52    56.1350.4926  148.46  160.19350.9218
  116.67  126.02350.5445  244.02  248.89351.2354
Bank Sta=35.31,49.47
XS Rating Curve= 0 ,0
Exp/Cntr=0.3,0.1

Type RM Length L Ch R = 1 ,16667.18,6.2,5.78,6.81
XS GIS Cut Line= 4
    -610393.8158    -1045643.949-610416.82609999   -1045617.2862
    -610427.9386   -1045608.2904-610522.61459999   -1045420.9473
#Sta/Elev= 30
       0  358.13    9.83  357.15   12.01  355.97   23.98  355.89   33.56  349.97
   35.22   348.7   38.62  346.02   40.35  345.83   46.29  345.68      48  347.55
   58.83  347.66   64.61  347.93   73.46  347.62   92.26  347.44   92.35  347.33
  101.51  347.59  108.59  347.46  113.83  347.53   120.2  347.29  147.91  347.45
  158.38  347.25   170.8   347.9  205.99  347.86  232.66  347.54  233.67  348.07
  243.08  347.93  254.22  348.12  254.91   348.2  257.28   349.9  259.42  349.93
#Mann= 3 , 0 , 0
       0      .1       0   35.22     .05       0      48      .2       0
Levee=0,,,-1,51.6,349.0984,,	2161
#Block Obstruct= 3 ,-1
   58.83   65.46350.7798  190.67  201.55350.8297  240.54   248.8 350.981
Bank Sta=35.22,48
XS Rating Curve= 0 ,0
Exp/Cntr=0.3,0.1

Type RM Length L Ch R = 1 ,16661.4 ,5.64,6.86,5.9
XS GIS Cut Line= 6
    -610396.1494   -1045646.1225-610420.53339999   -1045622.2464
-610432.85249999   -1045611.3244    -610443.2665   -1045593.5444
-610481.36659999   -1045517.8522    -610525.4721   -1045423.9106
#Sta/Elev= 30
       0  358.16    9.91  357.17   11.97  355.84   22.33  355.74   23.87  354.91
   34.35  348.36   37.29  346.05   39.09  345.81   42.58  345.74   45.69  345.75
   47.63  347.64   60.93  347.61   65.96  347.73   88.16  347.46   91.18  347.38
    91.3  347.23  102.31  347.47  104.31  347.27  115.28     347  131.44  347.12
  143.54   347.5  157.87  347.21  161.14  347.27   172.1  347.93  234.14   347.5
  235.04   348.1  239.62  347.98  256.23  348.23  258.71  349.95  259.72  350.01
#Mann= 3 , 0 , 0
       0      .1       0   34.35     .05       0   47.63      .2       0
Levee=0,,,-1,54.42,349.1576,,	2161
#Block Obstruct= 2 ,-1
  192.18  203.07350.7415  242.01  250.28351.0749
Bank Sta=34.35,47.63
XS Rating Curve= 0 ,0
Exp/Cntr=0.3,0.1

Type RM Length L Ch R = 1 ,16654.54,6.93,6.66,6.8
XS GIS Cut Line= 6
     -610399.919   -1045646.2163-610414.10069999   -1045633.6221
    -610423.8823   -1045626.7642    -610435.5652   -1045618.9463
    -610478.4107   -1045542.1985    -610530.1288   -1045427.2973
#Sta/Elev= 30
       0  357.92    7.45  357.15    9.46  355.71   18.93  355.45   20.83  354.18
   25.96  351.25   30.91  348.08   33.84  346.09   35.52  345.79   42.23  345.62
   44.97  347.61   45.65  347.71    64.5  347.61   74.01  347.38   83.87   347.4
   91.33  347.28   91.45  347.14  101.75  347.37  118.19  346.84  124.78  346.83
  142.08  346.87  143.13   347.4  163.07  347.62  170.12  347.96  171.35  347.84
  189.38  347.64  234.41  347.52  235.09  348.07  255.59  348.27  258.87  350.02
#Mann= 3 , 0 , 0
       0      .1       0   30.91     .05       0   45.65      .2       0
Levee=0,,,-1,55.88,349.1129,,	2161
#Block Obstruct= 3 ,-1
  241.83  250.11351.1296  192.08  202.98 350.625  107.84  132.87350.0207
Bank Sta=30.91,45.65
XS Rating Curve= 0 ,0
Exp/Cntr=0.3,0.1

Type RM Length L Ch R = 1 ,16647.88,5.99,6.32,7.53
XS GIS Cut Line= 6
-610407.45239999   -1045648.6625    -610428.5344   -1045631.8985
-610441.36149999   -1045622.7545-610461.68149999   -1045585.1624
    -610491.7806   -1045526.1073-610535.63219999   -1045432.9065
#Sta/Elev= 30
       0  357.49    4.15  357.11    6.59  355.39   15.07  355.31   25.93   347.9
   28.84  346.08   30.75  345.72   34.39  345.65   37.38  345.68   40.85  347.88
   44.05  347.89   46.97  346.75   51.41  346.92   71.69  346.83   79.54  347.25
   88.55  347.23   90.11  347.05   99.78  347.29  117.27  346.75  137.81  346.85
  140.96  346.93  141.89   347.4  146.14  347.36  165.71  348.02  166.93   347.6
  170.19  347.78  231.94  347.44  233.44  347.99  252.59  348.38   254.7  349.31
#Mann= 3 , 0 , 0
       0      .1       0   25.93     .05       0   40.85      .2       0
Levee=0,,,-1,76.74,348.5952,,	2159
#XS Ineff= 2 , 0
                           42.41          347.69
Permanent Ineff=
       F       F
#Block Obstruct= 3 ,-1
  105.66  130.77  349.98  190.35  201.24350.5325  239.91  248.18351.2398
Bank Sta=25.93,40.85
XS Rating Curve= 0 ,0
Exp/Cntr=0.3,0.1

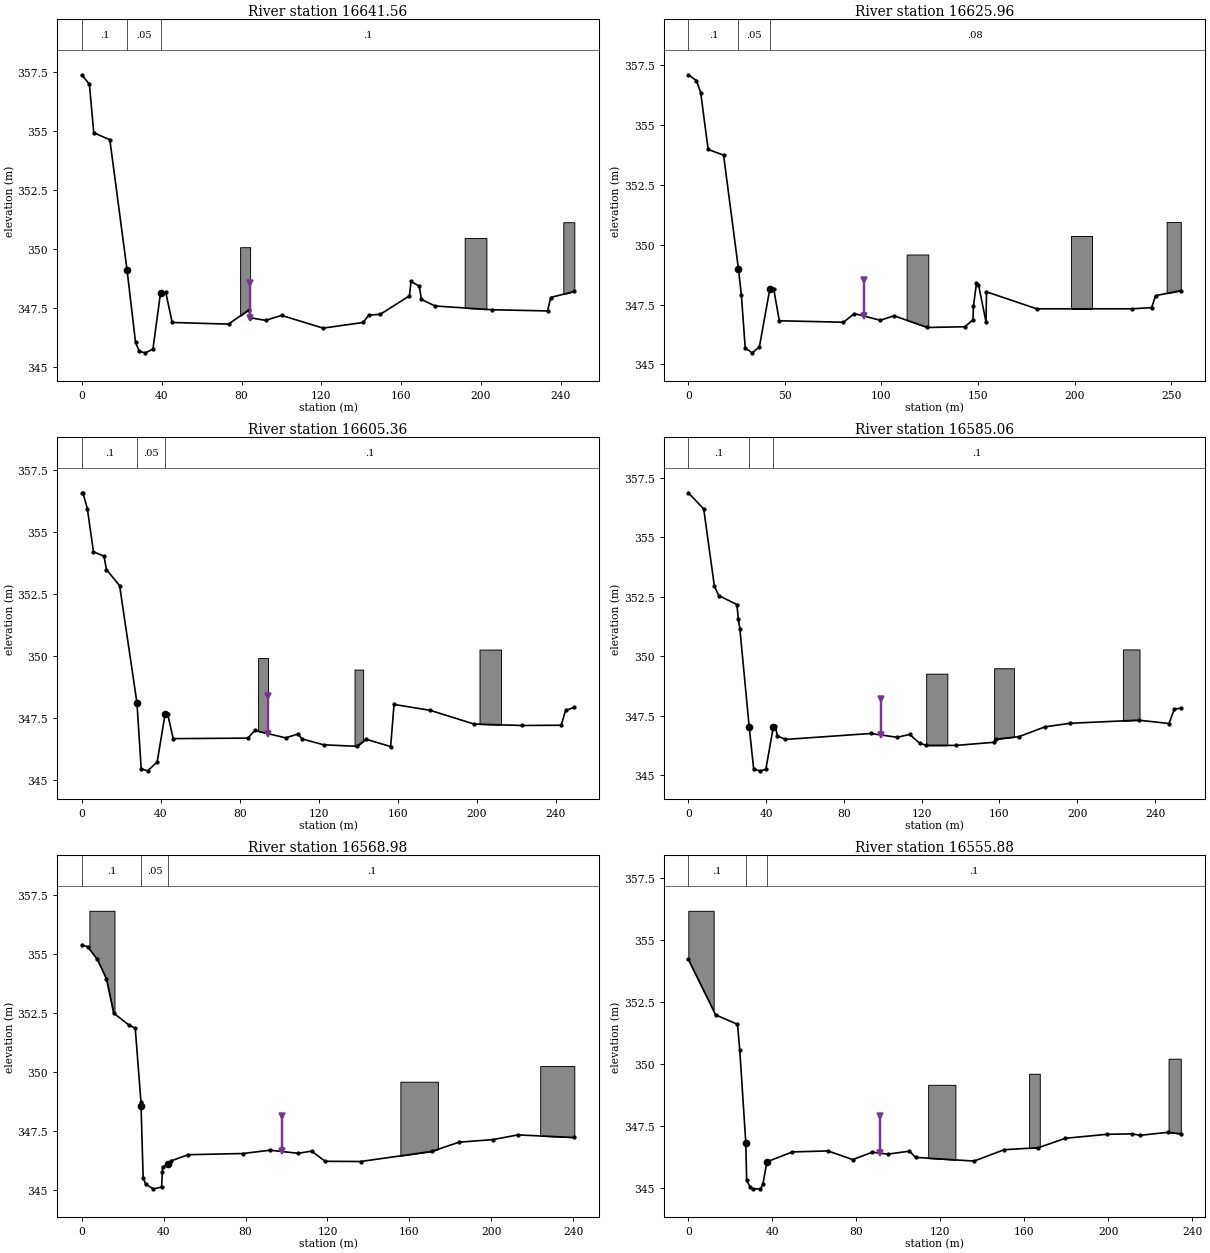
Type RM Length L Ch R = 1 ,16641.56,17.07,15.6,12.26
XS GIS Cut Line= 6
-610413.30689999   -1045653.7066-610431.29479999   -1045637.3368
-610446.09189999    -1045627.568    -610459.5562   -1045605.4465
    -610472.0445   -1045581.5282    -610537.3255   -1045444.4423
#Sta/Elev= 30
       0   357.4    3.78     357    5.96  354.94   14.03  354.64   22.68  349.09
    26.9  346.03   28.84  345.65   31.89  345.59   35.63  345.75   39.44  348.15
   42.05  348.16   45.25  346.88   73.49  346.81   83.79  347.42   84.32  347.08
   92.09  346.97   100.1  347.18  120.88  346.64  140.97  346.88  143.73  347.19
  149.61  347.23  164.14  348.01  164.93  348.62  169.11  348.42  170.12  347.86
  176.98  347.58  205.67  347.42  233.34  347.37  234.95  347.94  246.77   348.2
#Mann= 3 , 0 , 0
       0      .1       0   22.68     .05       0   39.44      .1       0
Levee=0,,,-1,84.49,348.5743,,	2159
#XS Ineff= 2 , 0
                           41.88           347.8
Permanent Ineff=
       F       F
#Block Obstruct= 3 ,-1
   79.31   84.32350.0773  191.83  202.72350.4694  241.25  246.77351.1385
Bank Sta=22.68,39.44
XS Rating Curve= 0 ,0
Exp/Cntr=0.3,0.1

Type RM Length L Ch R = 1 ,16625.96,21.61,20.6,17.48
XS GIS Cut Line= 6
-610425.68789999   -1045669.8678     -610440.574   -1045651.9392
-610455.03269999   -1045638.1208     -610482.421   -1045587.8698
    -610520.3187      -1045502.6-610545.36879999   -1045446.8765
#Sta/Elev= 30
       0   357.1    4.18  356.86    6.41  356.35   10.26  353.98   18.26  353.74
   25.94  348.99   27.45  347.91   29.46  345.68   33.12  345.48   36.79  345.73
   42.22  348.16   44.24  348.13   47.11  346.82   80.33  346.76   85.96  347.12
   99.43  346.84  106.46  347.03   123.8  346.54   143.2  346.57  147.34  346.86
  147.63  347.45  149.17  348.39  150.21  348.33  154.14  346.76  154.35  348.03
  180.32  347.32  229.76  347.32  239.84  347.37  241.88  347.87  254.94  348.08
#Mann= 3 , 0 , 0
       0      .1       0   25.94     .05       0   42.22     .08       0
Levee=0,,,-1,91.1,348.5402,,	2159
#XS Ineff= 2 , 0
                           43.59          347.69
Permanent Ineff=
       F       F
#Block Obstruct= 3 ,-1
     113  124.22349.5901  198.32  209.22350.3801  247.62  254.94350.9503
Bank Sta=25.94,42.22
XS Rating Curve= 0 ,0
Exp/Cntr=0.3,0.1

Type RM Length L Ch R = 1 ,16605.36,21.02,20.3,16.27
XS GIS Cut Line= 3
-610445.09629999   -1045684.5852-610473.44709999   -1045644.2738
-610552.67139999    -1045460.529
#Sta/Elev= 30
       0  356.58     .55  356.59    2.78  355.95    5.88  354.21   11.21  354.03
   12.46  353.49   19.13  352.84   27.91  348.11   30.05  345.45   33.32  345.37
   38.15  345.73   42.18  347.67   43.48  347.65   46.26  346.67   84.14  346.69
   87.53     347  103.21   346.7  109.51  346.86  111.41  346.66  122.47  346.42
  139.16  346.36   144.1  346.64  156.37  346.35  158.08  348.05  176.45  347.81
  198.52  347.26  222.94   347.2  242.73  347.21  244.96  347.81  249.38  347.93
#Mann= 3 , 0 , 0
       0      .1       0   27.91     .05       0   42.18      .1       0
Levee=0,,,-1,94.36,348.3709,,	2159
#XS Ineff= 2 , 0
                           42.87          347.36
Permanent Ineff=
       F       F
#Block Obstruct= 3 ,-1
   89.25   94.26349.9202  138.07  142.43349.4565  201.36  212.27350.2634
Bank Sta=27.91,42.18
XS Rating Curve= 0 ,0
Exp/Cntr=0.3,0.1

Type RM Length L Ch R = 1 ,16585.06,17.86,16.08,10.48
XS GIS Cut Line= 4
    -610464.0819   -1045699.0756    -610487.7346   -1045656.9739
    -610509.9596   -1045590.2987    -610560.0797   -1045465.2915
#Sta/Elev= 30
       0  356.87    7.92  356.19   13.39  352.95   15.62  352.55   24.98  352.17
   25.73  351.56   26.49  351.16    31.3  347.03   33.63  345.24   36.97  345.18
   39.85  345.24   43.72  347.03   44.65  347.06   45.84  346.65   49.93   346.5
   93.75  346.75  107.37  346.59  113.82  346.71  118.99  346.34  122.48  346.25
  137.76  346.25  157.18  346.38  158.11  346.51  170.11  346.62  183.44  347.03
  196.43  347.18  231.58  347.31  247.21  347.17  249.92  347.78  253.25  347.81
#Mann= 3 , 0 , 0
       0      .1       0    31.3     .05       0   43.72      .1       0
Levee=0,,,-1,99.07,348.1866,,	2159
#XS Ineff= 2 , 0
                           43.98          346.83
Permanent Ineff=
       F       F
#Block Obstruct= 3 ,-1
  122.33  133.19349.2643  157.26  167.42349.4925  223.47  232.02350.2849
Bank Sta=31.3,43.72
XS Rating Curve= 0 ,0
Exp/Cntr=0.3,0.1

Type RM Length L Ch R = 1 ,16568.98,14.3,13.1,11.02
XS GIS Cut Line= 5
    -610486.8255   -1045706.5634-610495.14299999   -1045679.7281
    -610497.7888   -1045668.0863    -610514.7221    -1045594.532
    -610561.2439   -1045478.4149
#Sta/Elev= 29
       0  355.37    2.76  355.32    7.58  354.77   12.03  353.94   15.54  352.49
   22.92  351.99   26.09  351.85   28.89   348.7   28.92  348.54   29.95  345.51
   31.19  345.23   34.85  345.03   38.95   345.1   39.31  345.75   39.49  345.96
   42.33  346.09   43.66  346.22   51.97  346.48   78.74  346.53   91.89  346.67
  105.62  346.54  112.26  346.63  118.88   346.2  136.17  346.19     171  346.62
  184.22  347.01  200.78  347.12  212.99  347.32   240.6  347.21
#Mann= 3 , 0 , 0
       0      .1       0   28.92     .05       0   42.33      .1       0
Levee=0,,,-1,97.59,348.1275,,	2159
#Block Obstruct= 3 ,-1
    3.69   15.95356.8368  155.62  173.94 349.579  223.92   240.6350.2427
Bank Sta=28.92,42.33
XS Rating Curve= 0 ,0
Exp/Cntr=0.3,0.1

Type RM Length L Ch R = 1 ,16555.88,20.77,21.27,17.9
XS GIS Cut Line= 5
    -610504.2404   -1045706.1507    -610509.2146    -1045681.174
    -610509.4305   -1045668.0863-610521.60139999   -1045611.4654
    -610562.8314   -1045479.6849
#Sta/Elev= 27
       0  354.23   13.02  351.99   23.42  351.61   24.51  350.56   27.39  346.81
   27.78  345.31   29.57  345.03   30.58  344.97   34.36  344.97    35.5  345.15
   37.44  346.06   49.54  346.46    66.5   346.5   78.34  346.15   87.71  346.45
    94.9  346.37   105.3  346.49  108.23  346.24  136.11  346.09  150.44  346.55
  166.72  346.63  179.56  347.01  199.26  347.17  211.42  347.19  215.11  347.13
  228.36  347.25  234.55  347.19
#Mann= 3 , 0 , 0
       0      .1       0   27.39     .05       0   37.44      .1       0
Levee=0,,,-1,91.29,347.9076,,	2159
#Block Obstruct= 4 ,-1
       0   12.06356.1919  114.23   127.2349.1687  162.31  167.39349.6144
  228.72  234.55350.2217
Bank Sta=27.39,37.44
XS Rating Curve= 0 ,0
Exp/Cntr=0.3,0.1

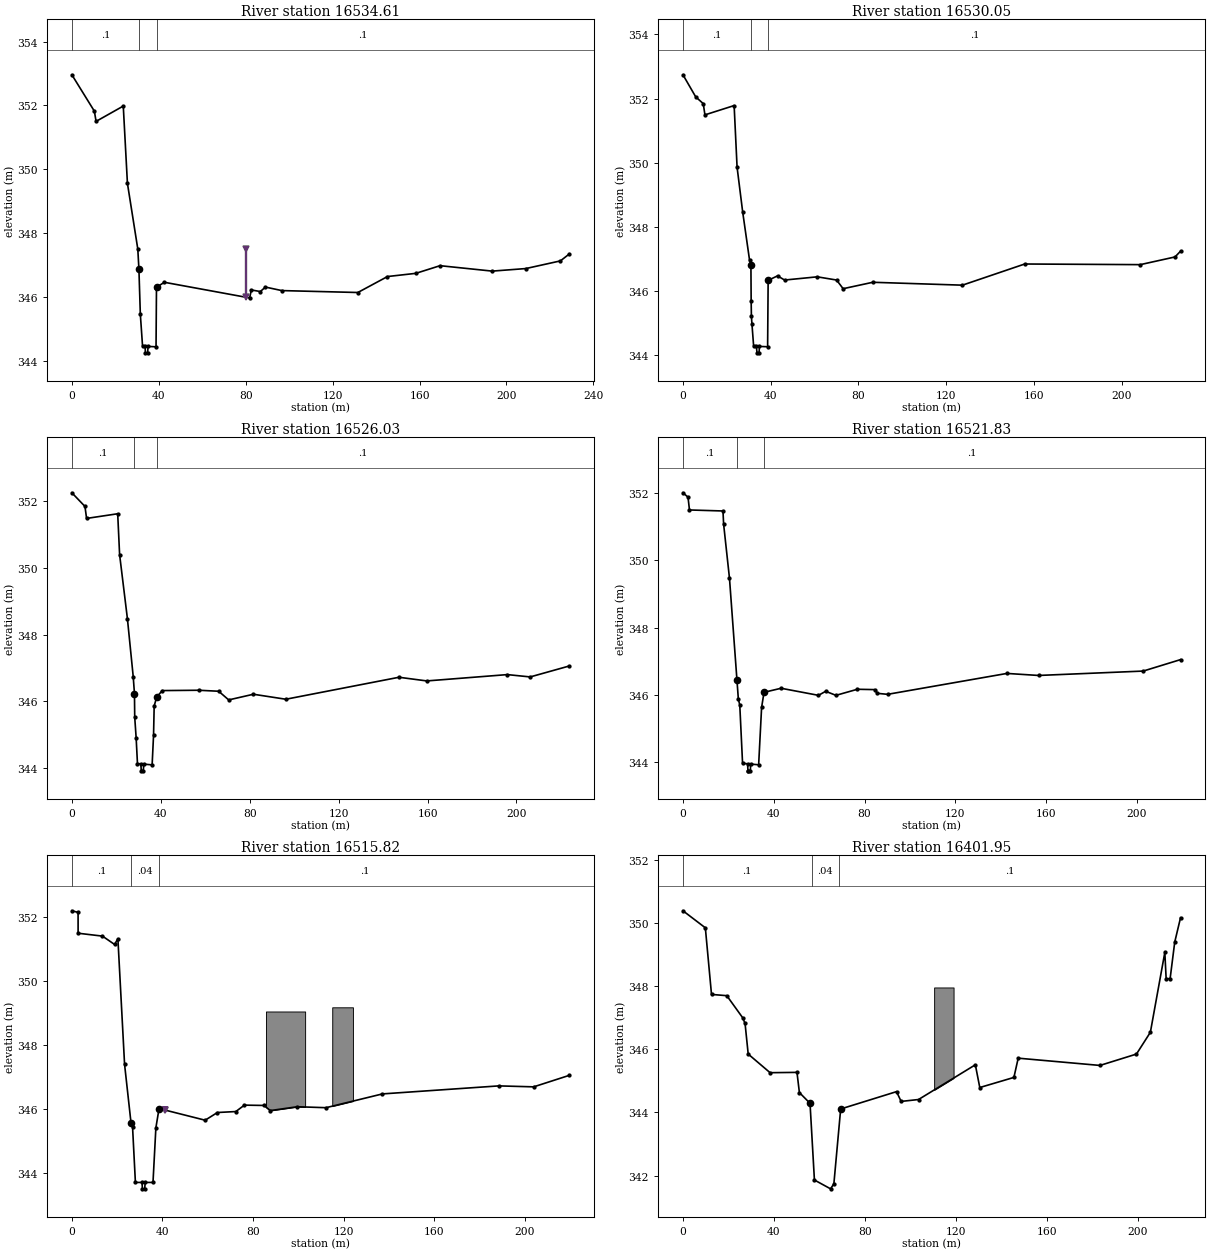
Type RM Length L Ch R = 1 ,16534.61,4.61,4.56,4.51
XS GIS Cut Line= 6
-610529.54529999   -1045705.4184    -610529.8783    -1045676.323
-610530.17399999   -1045665.9981-610534.91189999   -1045624.3717
-610542.27789999   -1045575.2226-610569.46539999   -1045481.1129
#Sta/Elev= 30
       0  352.96   10.36  351.82   11.14   351.5   23.66  351.98   25.57  349.56
   30.35   347.5   30.86  346.87   31.51  345.46   32.53  344.46   33.67  344.45
   33.87  344.25   34.87  344.25   35.07  344.45   38.74  344.44   38.94  346.29
   39.07  346.31   42.57  346.46   81.81  345.97    82.6  346.22   86.73  346.17
   89.08  346.31   96.62   346.2  131.61  346.14  145.25  346.64  158.29  346.74
  169.44  346.98  193.45  346.81   208.9  346.89  224.82  347.13  228.98  347.35
#Mann= 3 , 0 , 0
       0      .1       0   30.86     .04       0   39.07      .1       0
Levee=0,,,-1,80.25,347.4962,,	2159
Bank Sta=30.86,39.07
XS Rating Curve= 0 ,0
Exp/Cntr=0.3,0.1

Type RM Length L Ch R = 1 ,16530.05,3.73,4.02,4.32
XS GIS Cut Line= 6
    -610534.1055   -1045705.0639-610534.43849999   -1045675.9685
    -610534.7342   -1045665.6436    -610539.4721   -1045624.0172
    -610546.8381   -1045574.8681    -610573.0214   -1045482.6369
#Sta/Elev= 30
       0  352.74    5.83  352.05    9.26  351.84   10.02  351.49   23.34  351.78
   24.68  349.86   27.24  348.46   30.35  346.97   30.99  346.81    31.1   345.7
   31.21  345.22   31.46  344.97   32.23  344.28   33.48  344.28   33.76  344.07
   34.69  344.07   34.89  344.27   38.61  344.26   38.85  346.33   43.12  346.47
   46.35  346.34   61.25  346.44   70.06  346.34   73.04  346.07   86.57  346.27
  127.43  346.18  155.85  346.84  208.55  346.82  224.39  347.06   226.9  347.24
#Mann= 3 , 0 , 0
       0      .1       0   30.99     .04       0   38.85      .1       0
Bank Sta=30.99,38.85
XS Rating Curve= 0 ,0
Exp/Cntr=0.3,0.1

Type RM Length L Ch R = 1 ,16526.03,4.58,4.2,3.62
XS GIS Cut Line= 5
    -610538.0693   -1045702.3362-610538.07229999    -1045677.112
    -610539.6568   -1045657.3569-610551.82759999   -1045576.9234
    -610578.2707   -1045483.1449
#Sta/Elev= 30
       0  352.26     5.9  351.85    6.62  351.49   20.62  351.63   21.48   350.4
   24.99  348.48    27.6  346.74   28.16  346.23   28.28  345.52   28.91  344.91
   29.51  344.13   31.02  344.12   31.22  343.92   32.08  343.91   32.44  344.11
   36.11  344.09   36.75  344.98   37.03  345.86    38.2  346.13   40.68  346.32
   57.07  346.33   66.05   346.3   70.55  346.04   81.67  346.21   96.26  346.06
  147.15  346.72  159.66  346.61   195.9   346.8  206.17  346.73  223.83  347.06
#Mann= 3 , 0 , 0
       0      .1       0   28.16     .04       0    38.2      .1       0
Bank Sta=28.16,38.2
XS Rating Curve= 0 ,0
Exp/Cntr=0.3,0.1

Type RM Length L Ch R = 1 ,16521.83,6.74,6.01,5.22
XS GIS Cut Line= 4
    -610542.1235   -1045699.3356    -610543.0548   -1045657.4255
    -610557.9562   -1045571.9967    -610579.7877   -1045484.1398
#Sta/Elev= 30
       0     352    2.23  351.87    2.87  351.49   17.63  351.46   17.91  351.07
    20.5  349.46   23.79  346.44    24.4  345.88   25.03   345.7   26.26  343.97
   28.45  343.96   28.64  343.76   28.85  343.75   29.66  343.75   29.86  343.95
   33.34  343.93   34.64  345.63   35.71  346.08   43.23   346.2    59.7  345.99
   62.86  346.11   67.39  345.99   76.82  346.17   84.53  346.16   85.58  346.05
   90.13  346.02   142.7  346.64  156.61  346.58  202.73  346.71  219.17  347.05
#Mann= 3 , 0 , 0
       0      .1       0   23.79     .04       0   35.71      .1       0
Bank Sta=23.79,35.71
XS Rating Curve= 0 ,0
Exp/Cntr=0.3,0.1

Type RM Length L Ch R = 1 ,16515.82,2.86,2.86,2.83
XS GIS Cut Line= 5
    -610549.2021   -1045701.0436    -610549.7798   -1045679.3474
    -610548.1328   -1045663.7179    -610550.4721   -1045643.0045
    -610581.5868   -1045484.5631
#Sta/Elev= 30
       0  352.19    2.75  352.14    2.76  351.49   13.52   351.4   18.86  351.14
   20.33  351.32   23.28   347.4   26.15  345.56   26.81  345.44   28.06  343.72
   30.97  343.72   31.17  343.52   32.17  343.52   32.37  343.72   35.83  343.72
    37.1  345.42   38.47  346.01   38.68  346.02   58.86  345.66   64.28   345.9
   72.41  345.93   76.19  346.13   84.83  346.12   87.61  345.96   99.59  346.08
  112.21  346.05  137.16  346.48  188.56  346.73  203.93   346.7  219.73  347.06
#Mann= 3 , 0 , 0
       0      .1       0   26.15     .04       0   38.68      .1       0
Levee=0,,,-1,40.99,345.99,,
#Block Obstruct= 2 ,-1
   85.71  103.01  349.05  114.98  124.12349.1804
Bank Sta=26.15,38.68
XS Rating Curve= 0 ,0
Exp/Cntr=0.3,0.1

Type RM Length L Ch R = 1 ,16401.95,1.88,1.88,1.88
XS GIS Cut Line= 6
    -610643.0462   -1045735.4757    -610657.9483   -1045686.2902
-610661.88529999   -1045666.6815-610664.87119999    -1045645.638
-610675.02239999   -1045602.4955-610708.26749999   -1045527.6306
#Sta/Elev= 30
       0  350.39    9.85  349.85   12.56  347.74   19.29   347.7   26.28     347
   27.32  346.82    28.7  345.85   38.33  345.26   50.16  345.27   51.22  344.63
    55.9  344.29   57.83  341.86   64.94  341.58   66.39  341.74   69.38  344.11
   93.96  344.66   95.97  344.35  103.63  344.41  128.62  345.51  130.57  344.79
  145.58  345.11  147.47  345.72  183.43  345.49  199.49  345.85  205.61  346.54
  211.97  349.07  212.55  348.24   214.3  348.24  216.33   349.4  218.88  350.17
#Mann= 3 ,-1 , 0
       0      .1       0   56.59     .04       0   68.65      .1       0
#Block Obstruct= 1 ,-1
  110.49  119.04347.9603
Bank Sta=55.9,69.38
XS Rating Curve= 0 ,0
Exp/Cntr=0.3,0.1

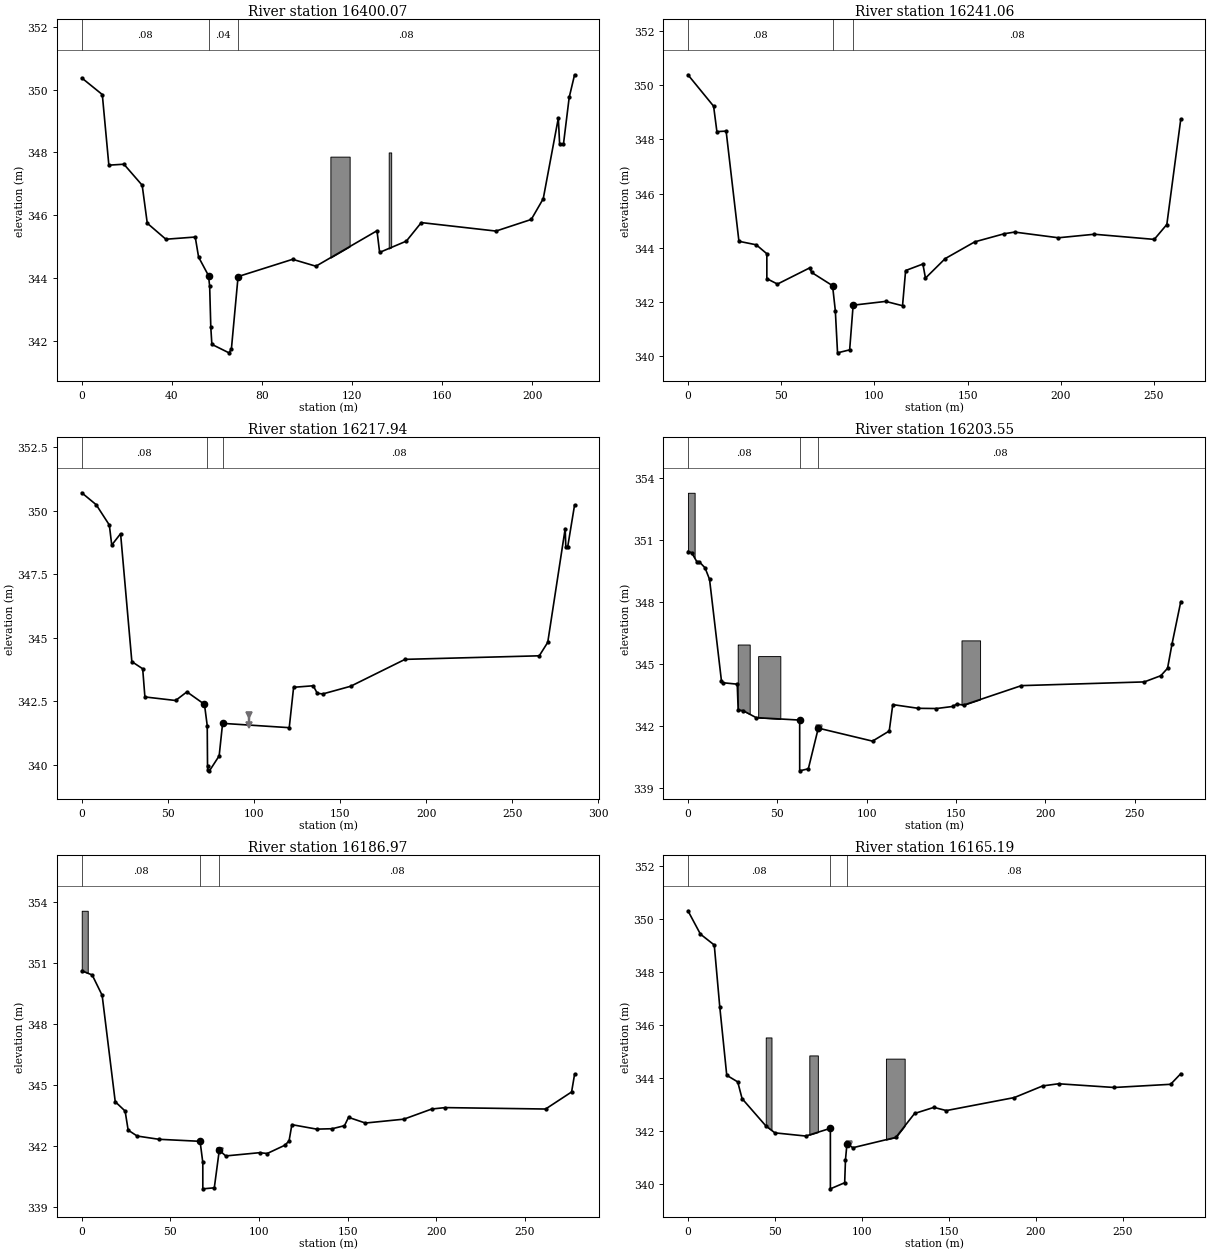
Type RM Length L Ch R = 1 ,16400.07,8.96,8.12,7.29
XS GIS Cut Line= 6
-610644.88569999   -1045735.8526-610659.78779999   -1045686.6671
    -610663.7248   -1045667.0584    -610666.7107   -1045646.0149
    -610676.8619   -1045602.8724     -610710.107   -1045528.0075
#Sta/Elev= 30
       0  350.37    9.13  349.84   12.04  347.59   18.73  347.62   26.84  346.95
    29.1  345.74   37.36  345.23    50.4   345.3    51.9  344.66    56.3  344.07
   56.81  343.73   57.32  342.42   57.79  341.88   65.38  341.61   66.46  341.73
   69.43  344.04   93.66  344.59  103.99  344.37  131.13   345.5  132.29  344.81
  144.17  345.17   150.8  345.76  183.97  345.49  199.64  345.86  204.96  346.52
  211.66  349.09  212.24  348.26  213.94  348.26  216.49  349.75  218.88  350.47
#Mann= 3 , 0 , 0
       0     .08       0    56.3     .04       0   69.43     .08       0
#Block Obstruct= 2 ,-1
  110.43  118.98347.8619  136.33  137.43347.9948
Bank Sta=56.3,69.43
XS Rating Curve= 0 ,0
Exp/Cntr=0.3,0.1

Type RM Length L Ch R = 1 ,16241.06,21.08,23.12,26.17
XS GIS Cut Line= 4
-610740.67799999   -1045794.9927    -610783.6451   -1045731.5412
-610794.63679999   -1045726.0454-610856.08969999   -1045561.6711
#Sta/Elev= 30
       0  350.39   13.77  349.23   15.54  348.29   20.49  348.31   27.36  344.24
   36.66  344.11   42.33  343.78   42.34  342.86   48.03  342.66   65.38  343.26
   66.37  343.09   77.59   342.6   79.07  341.68   80.26  340.12   86.76  340.23
   88.63  341.88  106.11  342.02  115.13  341.86  116.79  343.16  126.05   343.4
  127.44  342.88  138.01   343.6   153.9  344.22  169.78  344.52  175.28  344.58
  198.75  344.37  218.04   344.5  250.18  344.31  256.93  344.86  264.41  348.75
#Mann= 3 , 0 , 0
       0     .08       0   77.59     .04       0   88.63     .08       0
Bank Sta=77.59,88.63
XS Rating Curve= 0 ,0
Exp/Cntr=0.3,0.1

Type RM Length L Ch R = 1 ,16217.94,17.82,14.38,10.85
XS GIS Cut Line= 6
    -610749.3409   -1045804.8633    -610792.0326   -1045754.9198
    -610808.2784   -1045743.2547    -610827.6222   -1045711.1307
    -610872.3427   -1045570.3783    -610872.3427   -1045555.1515
#Sta/Elev= 30
       0  350.71    8.39  350.24   16.02  349.44   17.41  348.65   22.55   349.1
   29.09  344.06   35.38  343.78   36.67  342.67   54.49  342.53   61.05  342.87
   71.24  342.38   72.85  341.54   73.02  339.95    73.1  339.81   74.14  339.76
   79.78  340.35   81.77  341.63  120.46  341.46     123  343.05  134.37  343.11
  136.79  342.81  140.02  342.79  156.08  343.09  187.68  344.15  265.62  344.29
  270.54  344.82  280.67   349.3  281.02  348.59  282.12  348.58  286.12  350.23
#Mann= 3 ,-1 , 0
       0     .08       0   72.44     .04       0   81.72     .08       0
Levee=0,,,-1,97.34,341.97,,
Bank Sta=71.24,81.77
XS Rating Curve= 0 ,0
Exp/Cntr=0.3,0.1

Type RM Length L Ch R = 1 ,16203.55,16.98,16.59,13.12
XS GIS Cut Line= 5
    -610769.6559   -1045808.4823    -610808.1264   -1045763.0171
    -610815.1211   -1045751.5259    -610847.5962   -1045700.0653
    -610890.0638   -1045564.6689
#Sta/Elev= 30
       0  350.46    2.07   350.4    4.97  349.97    6.36  349.96    9.56  349.67
   12.09  349.11   18.75  344.19   19.58   344.1   27.59  344.03    28.1  342.77
   30.81  342.75   38.12  342.41   62.52  342.29   62.53  339.83   67.37  339.93
   72.94   341.9  103.27  341.27  112.63  341.76  114.61  343.04  128.88  342.86
  139.06  342.85  148.15  342.95  150.27  343.06  154.36  343.02  186.61  343.96
  255.33  344.14  264.57  344.44  268.36   344.8  270.82  345.96  275.76  348.03
#Mann= 3 , 0 , 0
       0     .08       0   62.52     .04       0   72.94     .08       0
Levee=0,,,-1,73.61,341.88,,
#Block Obstruct= 4 ,-1
  153.07  163.46346.1526       0    3.74353.3066   27.86   34.56 345.952
   39.28   51.69345.3915
Bank Sta=62.52,72.94
XS Rating Curve= 0 ,0
Exp/Cntr=0.3,0.1

Type RM Length L Ch R = 1 ,16186.97,23.06,21.77,16.29
XS GIS Cut Line= 5
    -610779.6482   -1045816.9759    -610825.1134   -1045768.5129
    -610828.6108   -1045757.0217-610860.08659999   -1045702.5634
    -610908.5496   -1045574.6612
#Sta/Elev= 30
       0  350.62    5.89  350.41   11.51  349.41    18.9  344.17   24.48  343.71
   26.19  342.77   31.27  342.48   43.49  342.32   66.78  342.22   68.32  341.18
   68.33  339.88   74.81  339.93   77.62  341.78   81.26   341.5  100.37  341.66
  104.66  341.62   114.7  342.03     117  342.24  118.59  343.04   132.6  342.82
  141.36  342.84  148.28  342.99  150.56   343.4  160.08  343.12  181.77  343.31
  197.52  343.81  205.12  343.88  261.78  343.81  276.45  344.65  278.14  345.52
#Mann= 3 , 0 , 0
       0     .08       0   66.78     .04       0   77.62     .08       0
Levee=0,,,-1,78.12,341.73,,
#Block Obstruct= 1 ,-1
       0    3.38 353.571
Bank Sta=66.78,77.62
XS Rating Curve= 0 ,0
Exp/Cntr=0.3,0.1

Type RM Length L Ch R = 1 ,16165.19,23.88,24.21,22.28
XS GIS Cut Line= 4
    -610790.1402   -1045840.9575-610846.59699999    -1045775.008
    -610849.0951   -1045761.5183-610919.04149999   -1045584.6535
#Sta/Elev= 27
       0   350.3    7.18  349.42   15.14  349.01   18.29  346.69   22.32   344.1
   28.64  343.85   31.14  343.22   44.85  342.19   50.01  341.93   67.73  341.81
   81.92   342.1   81.93  339.82   90.15  340.05   90.61  340.92   91.47  341.52
   91.57  341.52   94.87  341.37  119.58  341.76  130.35  342.66  141.45  342.89
  148.64  342.77  187.72  343.26  204.08   343.7  213.17  343.78  245.14  343.64
  277.62  343.76  283.46  344.16
#Mann= 3 , 0 , 0
       0     .08       0   81.92     .04       0   91.57     .08       0
Levee=0,,,-1,92.49,341.5,,
#Block Obstruct= 3 ,-1
   44.75   48.05345.5259   69.81   74.72344.8481  113.88  124.65344.7277
Bank Sta=81.92,91.57
XS Rating Curve= 0 ,0
Exp/Cntr=0.3,0.1