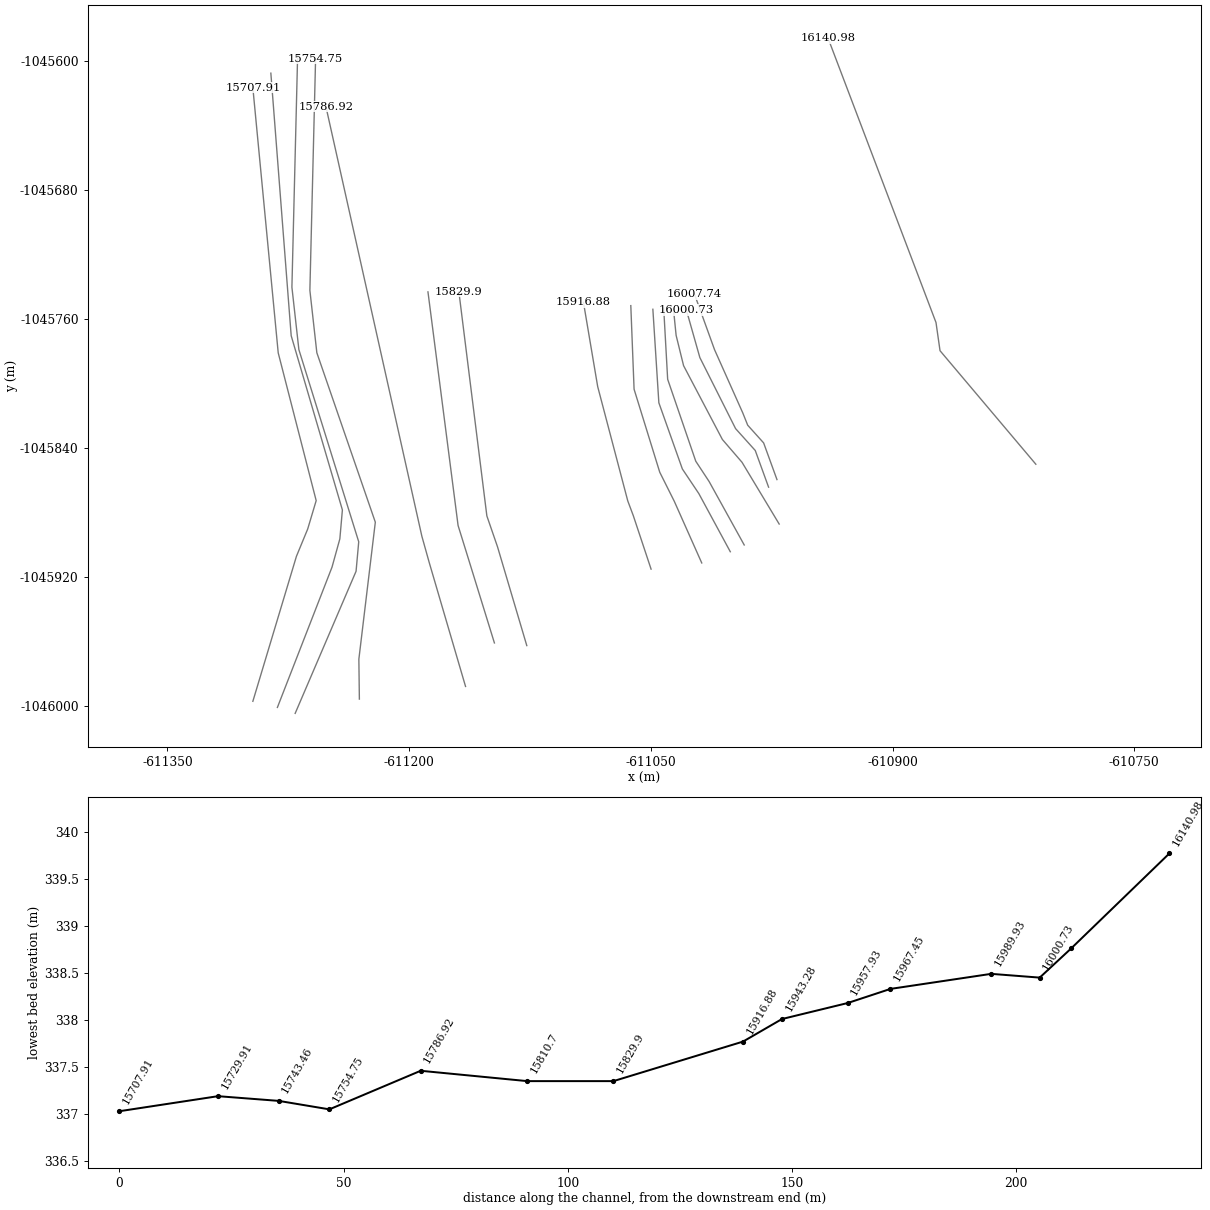
HEC-RAS study PPO_Kvasiny_efektiv.prj: PPO_Kvasiny_efektivita

--- PPO_Kvasiny_efektiv.g01 (geometry) --- (continued)

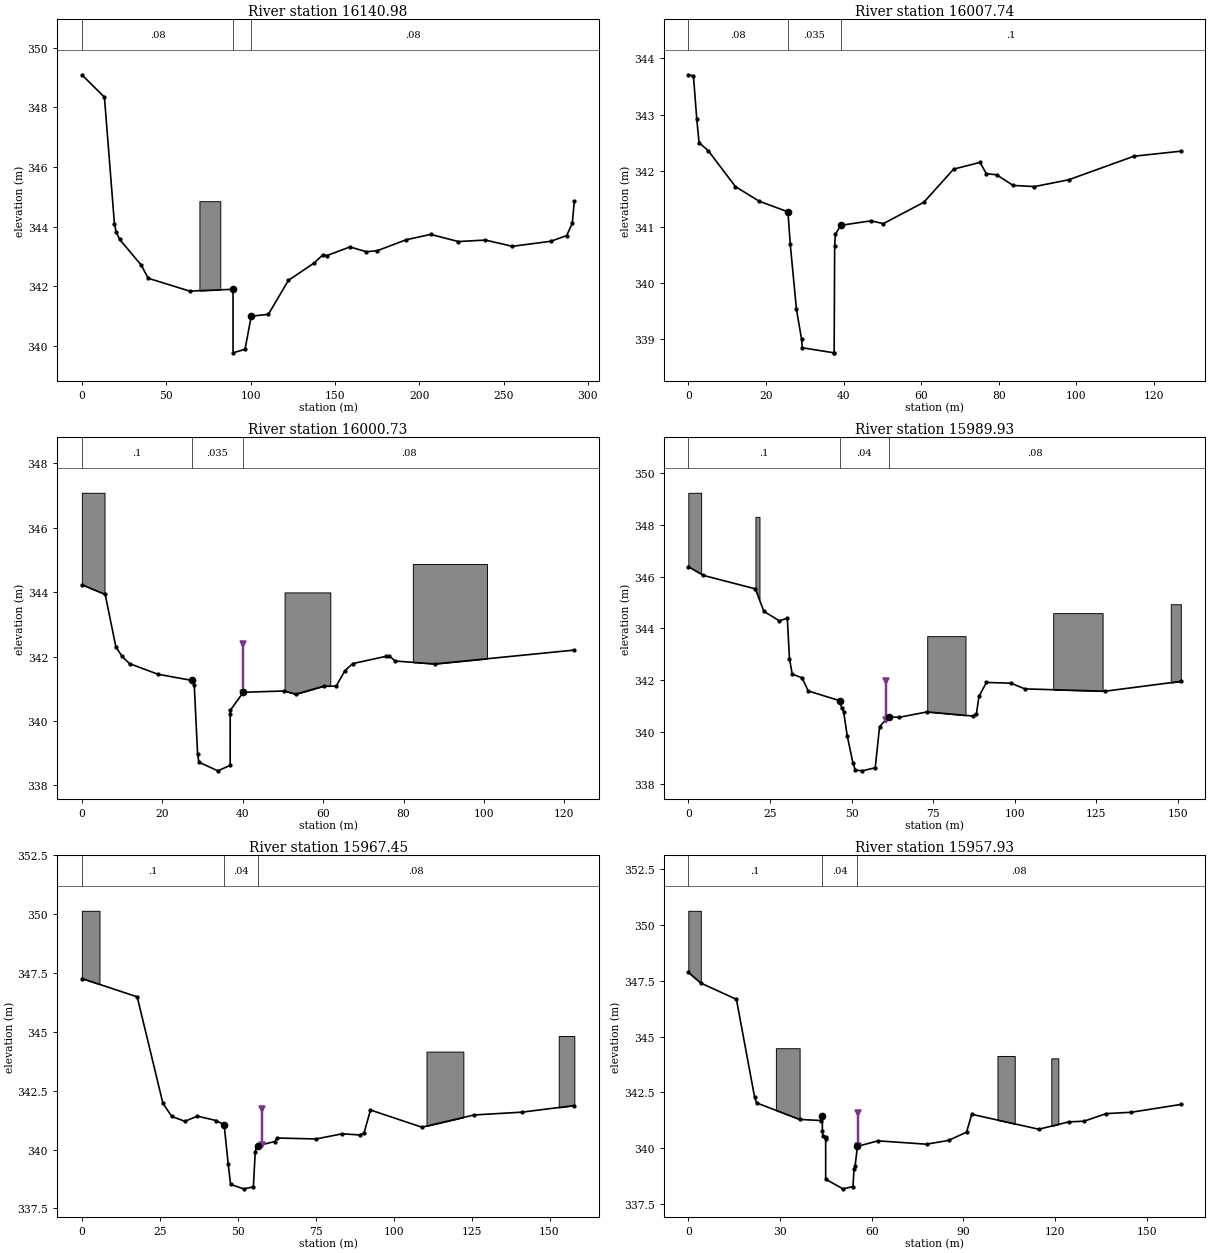
Type RM Length L Ch R = 1 ,16140.98,20.09,21.91,20.25
XS GIS Cut Line= 4
    -610811.1241   -1045849.9506    -610870.5786   -1045779.5045
-610873.07669999   -1045762.0179    -610940.0255   -1045585.6527
#Sta/Elev= 29
       0  349.09   13.38  348.34   19.31   344.1   20.29  343.83   22.43  343.57
   35.21  342.71   39.32  342.27   63.88  341.84   89.62   341.9   89.63  339.77
   96.74  339.89  100.43     341  110.58  341.06  122.46   342.2   137.9  342.79
  142.93  343.06  145.31  343.03  158.93  343.32  168.61  343.16  174.96  343.19
  192.29  343.56  206.78  343.74  223.24   343.5   239.2  343.55  255.24  343.34
  278.02  343.51   287.4   343.7  290.74  344.11  291.95  344.86
#Mann= 3 , 0 , 0
       0     .08       0   89.62     .04       0  100.43     .08       0
#Block Obstruct= 1 ,-1
   69.69   82.07344.8526
Bank Sta=89.62,100.43
XS Rating Curve= 0 ,0
Exp/Cntr=0.3,0.1

Type RM Length L Ch R = 1 ,16007.74,6.71,7.01,8.54
XS GIS Cut Line= 6
-610971.77129999   -1045859.4797    -610980.0408   -1045836.7296
    -610989.9356   -1045825.7279    -610992.9954   -1045818.0942
-611010.51089999   -1045778.8608    -611023.0044   -1045744.3002
#Sta/Elev= 29
       0  343.71    1.32  343.69    2.18  342.92    2.77   342.5    5.13  342.36
   12.14  341.72   18.24  341.46   25.68  341.27   26.28  340.69   27.86  339.54
    29.2     339   29.37  338.85   37.58  338.76   37.59  338.76   37.72  340.66
   37.91  340.87   39.28  341.03   47.07  341.11   50.26  341.06    60.7  341.44
   68.38  342.03   75.18  342.15   76.81  341.95   79.46  341.93   83.71  341.74
   89.23  341.72   98.01  341.84  114.86  342.26  126.94  342.35
#Mann= 3 , 0 , 0
       0     .08       0   25.68    .035       0   39.28      .1       0
Bank Sta=25.68,39.28
XS Rating Curve= 0 ,0
Exp/Cntr=0.3,0.1

Type RM Length L Ch R = 1 ,16000.73,9.83,10.81,10.61
XS GIS Cut Line= 5
     -610976.975   -1045864.1751    -610985.2445    -1045841.425
    -610997.4496   -1045827.8546-611019.62709999   -1045783.7506
    -611027.9807   -1045754.2729
#Sta/Elev= 26
       0  344.23     5.8  343.93    8.46   342.3    9.96  342.01   11.85  341.78
   18.91  341.45   27.28  341.26   27.95  341.12   28.78  338.98    29.1  338.72
   33.82  338.45   36.88  338.62   36.89   340.2   36.91  340.33   40.15  340.89
   50.35  340.93   53.21  340.83   60.15  341.08   63.25  341.08   65.41  341.56
   67.34  341.78   75.75  342.01   76.44  342.02   77.92  341.86   87.77  341.77
  122.46   342.2
#Mann= 3 , 0 , 0
       0      .1       0   27.28    .035       0   40.15     .08       0
Levee=0,,,-1,40.08,342.3748,,	2160
#Block Obstruct= 3 ,-1
       0    5.64347.0853    82.3  100.74344.8723   50.41   61.78343.9916
Bank Sta=27.28,40.15
XS Rating Curve= 0 ,0
Exp/Cntr=0.3,0.1

Type RM Length L Ch R = 1 ,15989.93,23.84,22.47,19.81
XS GIS Cut Line= 6
    -610970.3973   -1045887.0677    -610993.4662   -1045848.7396
    -611005.6395   -1045834.6026    -611029.7291    -1045788.774
    -611034.3488   -1045770.0031    -611035.9998    -1045753.747
#Sta/Elev= 30
       0  346.39    4.63  346.05   20.52  345.53   23.14  344.66   27.92  344.29
   30.32   344.4   30.98  342.83   31.83  342.23   34.82  342.09   36.74  341.58
   46.45   341.2   46.96  340.92   47.56  340.78   48.68  339.84   50.39  338.81
   51.14  338.52   53.27  338.49   57.25  338.61   58.58   340.2   61.37  340.58
   64.54  340.56   73.16  340.77   87.05  340.61   88.25   340.7   89.02  341.37
   91.32  341.91   98.87  341.88  103.09  341.66   127.6  341.57  150.84  341.95
#Mann= 3 , 0 , 0
       0      .1       0   46.45     .04       0   61.37     .08       0
Levee=0,,,-1,60.53,341.9759,,	2160
#Block Obstruct= 5 ,-1
   20.56    21.8348.3146  111.76  126.89  344.59   73.17    84.9   343.7
       0    3.93349.2465  147.77  150.84344.9349
Bank Sta=46.45,61.37
XS Rating Curve= 0 ,0
Exp/Cntr=0.3,0.1

Type RM Length L Ch R = 1 ,15967.45,9.35,9.53,9.59
XS GIS Cut Line= 5
-610992.09319999   -1045900.0587    -611013.8884   -1045860.6581
-611022.15659999   -1045848.0903-611039.60269999   -1045797.2262
-611042.06069999   -1045753.1775
#Sta/Elev= 26
       0  347.27   17.76  346.49   26.01  341.96   28.84  341.41   33.02   341.2
   37.08  341.42   43.15  341.23   45.64  341.05   46.95  339.37    47.7  338.52
   51.85  338.33   55.01  338.41   55.61  339.89   56.02  340.12   56.35  340.16
   61.82  340.34   62.73  340.49    75.1  340.45   83.56  340.67   89.14  340.62
    90.5   340.7   92.58  341.68  109.06  340.95   125.8  341.47  141.22  341.59
  157.96  341.87
#Mann= 3 , 0 , 0
       0      .1       0   45.64     .04       0   56.35     .08       0
Levee=0,,,-1,57.76,341.7307,,	2160
#Block Obstruct= 3 ,-1
  110.54  122.37344.1635       0    5.65350.1486  152.96  157.96344.8275
Bank Sta=45.64,56.35
XS Rating Curve= 0 ,0
Exp/Cntr=0.3,0.1

Type RM Length L Ch R = 1 ,15957.93,15.71,14.65,13.63
XS GIS Cut Line= 5
     -611000.734   -1045904.2531    -611020.2591   -1045868.1678
-611030.47859999   -1045852.8987-611045.06769999   -1045811.8192
-611048.78449999   -1045753.7894
#Sta/Elev= 30
       0  347.88    4.05   347.4   15.74  346.67   21.67   342.3   22.34  342.03
   36.42  341.29    43.5  341.24   43.53  341.44   43.83  341.45   43.88  340.76
   44.08  340.53   44.92  340.42   44.94  340.49   44.95  338.61   50.61  338.18
   53.89  338.28    54.2  339.05   54.58   339.2   55.32  340.08   62.03  340.33
   77.96  340.18   85.16  340.35   91.04  340.72   92.73  341.52  114.67  340.85
  124.49  341.18  129.49  341.21  136.74  341.55   144.9  341.61  161.14  341.96
#Mann= 3 , 0 , 0
       0      .1       0   43.83     .04       0   55.32     .08       0
Levee=0,,,-1,55.65,341.5947,,	2160
#Block Obstruct= 4 ,-1
  118.77  121.07344.0259  101.15   106.8344.1338       0    4.09350.6369
   28.65   36.42344.4799
Bank Sta=43.83,55.32
XS Rating Curve= 0 ,0
Exp/Cntr=0.3,0.1

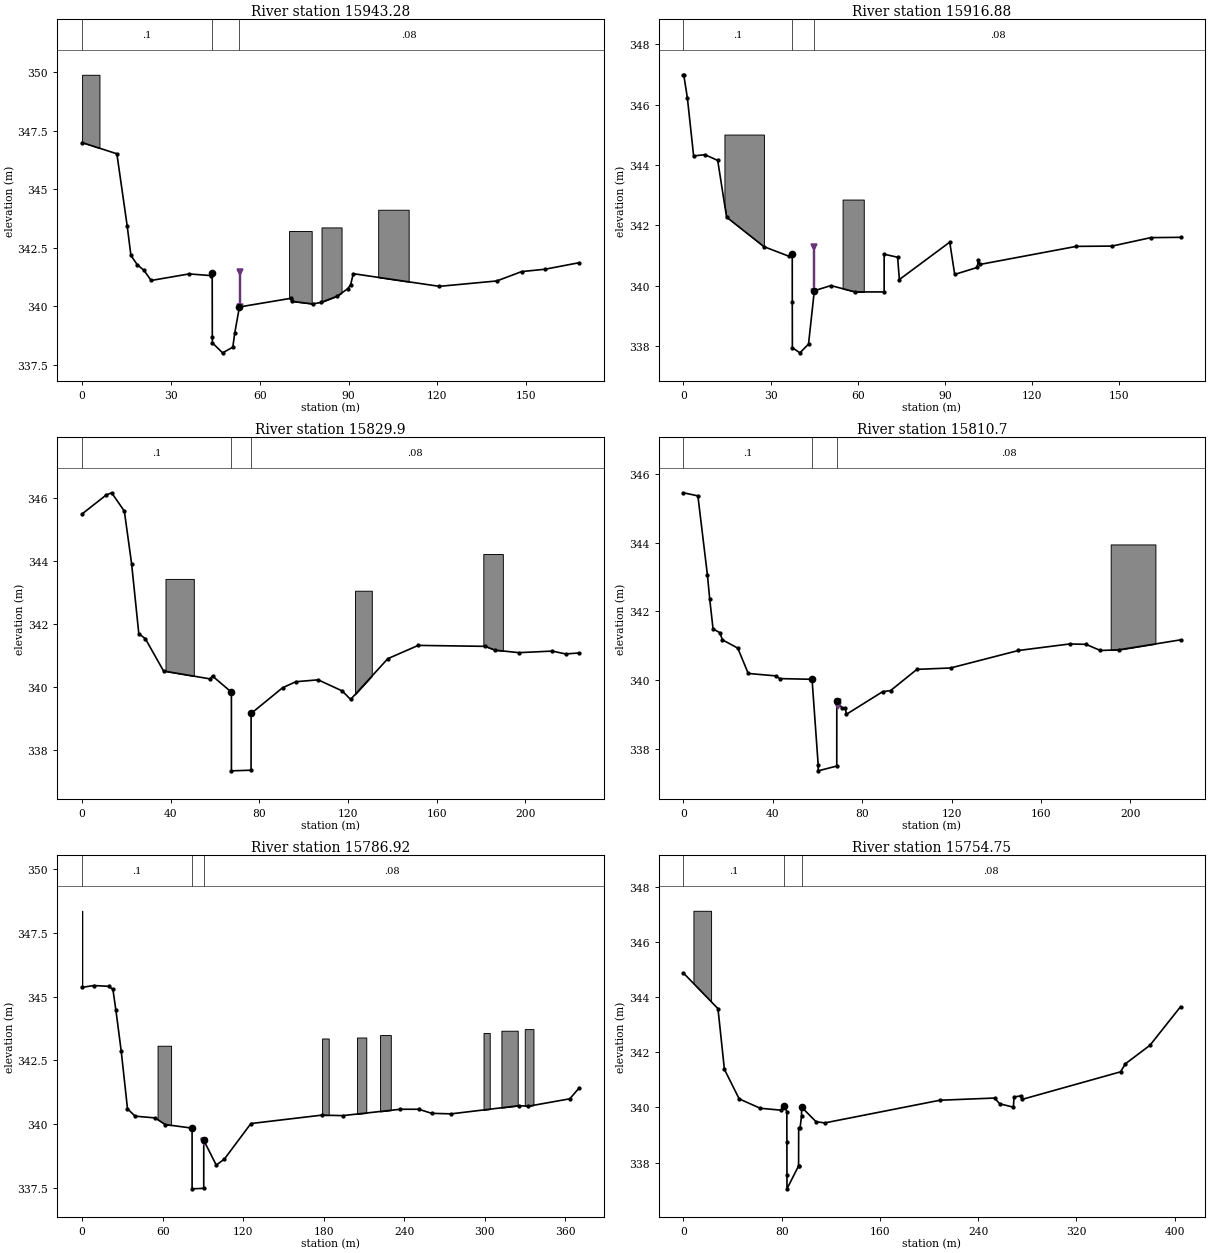
Type RM Length L Ch R = 1 ,15943.28,9.23,8.7,8.01
XS GIS Cut Line= 5
-611018.45259999   -1045911.2168    -611035.5181   -1045872.8951
-611044.51399999   -1045854.9034-611060.44139999   -1045803.4049
-611062.47329999   -1045751.5215
#Sta/Elev= 30
       0  346.99   11.75  346.51   15.23  343.43   16.49  342.17    18.6  341.78
   20.91  341.53   23.32   341.1   36.13  341.38   43.42  341.31   43.45  341.42
   43.94  341.41   43.98  338.67   43.99  338.44   47.44  338.01    50.9  338.25
   51.56  338.86   53.14  339.97    70.6  340.34   70.79  340.21   77.82   340.1
   80.64  340.16   86.13  340.43   89.75  340.75   90.69  340.92   91.59  341.39
  120.67  340.85  140.07  341.08  148.45  341.48  156.33  341.58  167.89  341.86
#Mann= 3 , 0 , 0
       0      .1       0   43.94     .04       0   53.14     .08       0
Levee=0,,,-1,53.22,341.4764,,	2160
#Block Obstruct= 4 ,-1
       0    5.87349.8845    69.9   77.54 343.214   80.86   87.63 343.366
     100  110.29344.1213
Bank Sta=43.94,53.14
XS Rating Curve= 0 ,0
Exp/Cntr=0.3,0.1

Type RM Length L Ch R = 1 ,15916.88,28.68,28.89,29.62
XS GIS Cut Line= 5
    -611049.8937   -1045915.0428    -611060.9182    -1045881.891
    -611064.3608   -1045872.7106    -611083.0196   -1045801.8009
-611091.84849999   -1045749.5303
#Sta/Elev= 30
       0  346.99     .14  346.97    1.35  346.23    3.51   344.3    7.42  344.34
    11.8  344.15   14.85  342.27   27.72  341.29    36.4  340.97   37.45  341.06
   37.46  339.45   37.49  337.94   40.08  337.77   43.05  338.06   45.05  339.83
   50.76     340   59.07  339.79   69.07  339.79   69.08  341.04   73.71  340.94
   74.31   340.2   91.65  341.44   93.35  340.37  101.08   340.6   101.5  340.85
  101.99   340.7   135.2   341.3  147.48  341.31  160.85  341.59  171.08   341.6
#Mann= 3 , 0 , 0
       0      .1       0   37.45     .04       0   45.05     .08       0
Levee=0,,,-1,44.99,341.2633,,	2160
#Block Obstruct= 2 ,-1
   54.77   62.06342.8527   14.11    27.7 345.008
Bank Sta=37.45,45.05
XS Rating Curve= 0 ,0
Exp/Cntr=0.3,0.1

Type RM Length L Ch R = 1 ,15829.9 ,19.46,19.19,18.61
XS GIS Cut Line= 4
-611127.02369999   -1045962.5109-611145.18809999   -1045901.2055
    -611151.8026   -1045882.0232    -611169.1645    -1045742.966
#Sta/Elev= 28
       0  345.48   10.89  346.08   13.33  346.15   19.07  345.57   22.36   343.9
    25.6  341.69   28.57  341.53   36.77  340.51   57.75  340.26   58.86  340.35
   67.39  339.84    67.4  337.35   76.27  337.37   76.28  339.16   76.36  339.17
   90.51  339.98   96.45  340.17  106.54  340.23  117.37  339.88  121.19  339.61
  137.99   340.9  151.71  341.32  181.95  341.29  186.38  341.17  197.12  341.09
  212.17  341.14   218.2  341.05  224.37  341.08
#Mann= 3 , 0 , 0
       0      .1       0   67.39    .035       0   76.36     .08       0
#Block Obstruct= 3 ,-1
   37.64   50.42343.4244  123.19  130.76343.0505  181.09   189.9344.2119
Bank Sta=67.39,76.36
XS Rating Curve= 0 ,0
Exp/Cntr=0.3,0.1

Type RM Length L Ch R = 1 ,15810.7 ,23.98,23.78,23.78
XS GIS Cut Line= 4
-611147.12029999   -1045960.8525-611163.70899999   -1045907.1587
-611169.66209999   -1045887.9764    -611188.3553   -1045742.9866
#Sta/Elev= 29
       0  345.46    6.47  345.37   10.74  343.06   11.78  342.35   13.26  341.49
   16.26  341.38   17.47  341.17   24.31  340.93   29.01  340.19    41.3  340.12
   43.17  340.04   57.56  340.02   60.31  337.52   60.32  337.35   68.62  337.49
   68.63  339.39   71.01  339.18   72.44  339.17   72.96     339   89.18  339.66
    92.7  339.69  104.49  340.31  119.55  340.35  149.92  340.86   172.8  341.05
   180.1  341.04  186.59  340.86  194.88  340.88  222.47  341.17
#Mann= 3 , 0 , 0
       0      .1       0   57.56     .04       0   68.63     .08       0
Levee=0,,,-1,69.14,339.23,,
#Block Obstruct= 1 ,-1
   191.2  211.22343.9536
Bank Sta=57.56,68.63
XS Rating Curve= 0 ,0
Exp/Cntr=0.3,0.1

Type RM Length L Ch R = 1 ,15786.92,22.11,20.36,18.99
XS GIS Cut Line= 4
     -611165.032   -1045987.8568    -611187.5216   -1045911.1275
-611192.15179999    -1045894.591    -611251.6831   -1045628.0227
#Sta/Elev= 27
       0  345.36    8.56  345.43   19.87   345.4   22.95  345.28   25.17  344.47
   29.12  342.87   33.82   340.6   39.46  340.31   54.42  340.24   61.97  339.98
   81.93  339.84   81.94  337.46   90.61  337.48   90.62  339.36   99.95  338.39
  106.03  338.63  125.74  340.02  178.62  340.35  194.02  340.33  237.09  340.58
  250.73  340.58  260.41  340.42  274.87   340.4  325.38  340.72  332.41   340.7
  363.26  340.99  370.26  341.42
#Mann= 3 , 0 , 0
       0      .1       0   81.93    .035       0   90.62     .08       0
Levee=0,,,-1,90.99,339.3,,
#Block Obstruct= 8 ,-1
   56.21    66.3343.0709  221.93  229.93343.4889  329.69  336.18343.7225
  312.31  324.45343.6595     299  303.61343.5717       0     .15348.3615
  178.74  183.69343.3546  204.71  211.66343.3929
Bank Sta=81.93,90.62
XS Rating Curve= 0 ,0
Exp/Cntr=0.3,0.1

Type RM Length L Ch R = 1 ,15754.75,11.28,11.29,11.04
XS GIS Cut Line= 6
     -611230.918   -1045995.6999    -611231.2355   -1045970.9348
    -611221.0212    -1045885.914    -611257.3088   -1045780.7867
    -611261.6351    -1045742.032    -611258.0872   -1045598.3207
#Sta/Elev= 30
       0  344.87   28.12  343.58   33.36  341.38   45.38  340.31    62.5  339.97
    79.6   339.9   82.07  340.05   84.19  339.85   84.22  338.74   84.29  337.54
    84.3  337.05   93.74  337.88   93.75  337.89   93.83  339.24   94.91  339.25
   96.15  339.68   96.21  340.01  108.01  339.48  115.21  339.44  208.71  340.26
  253.27  340.34  257.54  340.13  268.64  340.01  269.15  340.38  275.01  340.42
   275.6  340.29  355.89  341.29  359.79  341.58  379.77  342.25  404.72  343.65
#Mann= 3 , 0 , 0
       0      .1       0   82.07    .035       0   96.21     .08       0
#Block Obstruct= 1 ,-1
    8.14   22.52347.1254
Bank Sta=82.07,96.21
XS Rating Curve= 0 ,0
Exp/Cntr=0.3,0.1

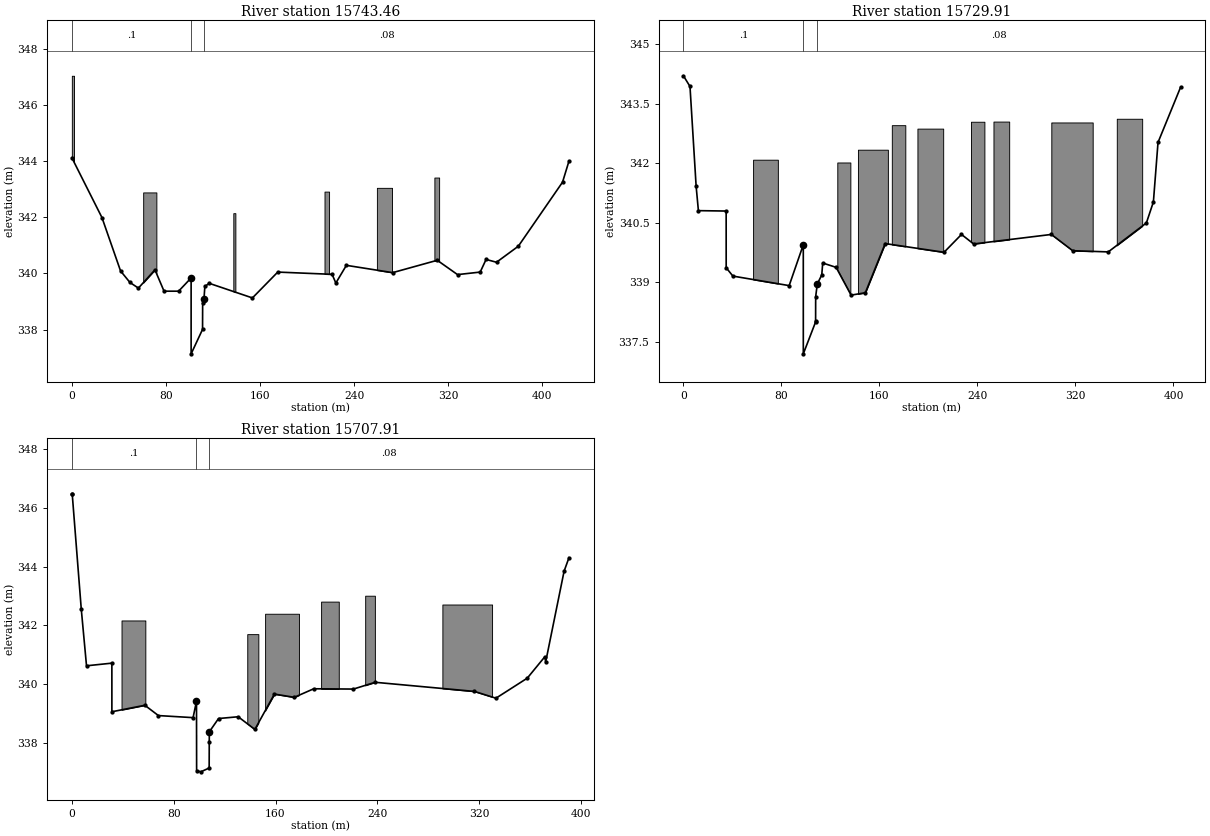
Type RM Length L Ch R = 1 ,15743.46,14.98,13.54,10.62
XS GIS Cut Line= 6
    -611270.7595   -1046004.5644    -611232.9684    -1045916.367
-611231.32099999   -1045898.0854-611268.45829999   -1045778.8404
    -611272.7846   -1045740.0857    -611269.2368   -1045596.3744
#Sta/Elev= 30
       0  344.12   25.61  341.99   41.43  340.09   49.41  339.68    56.6  339.48
   70.68  340.13   78.41  339.37   90.78  339.37  101.39  339.84  101.42  339.84
  101.43  337.14  111.14  338.01  111.23  338.95  112.36   339.1  113.11  339.54
  116.83  339.65  153.54  339.13  175.09  340.05  221.29  339.97  224.48  339.66
  233.43  340.29  272.77  340.03  310.69  340.47  327.95  339.96  347.21  340.05
  352.21   340.5  361.08   340.4  379.62  340.97  417.22  343.25  422.69     344
#Mann= 3 , 0 , 0
       0      .1       0  101.39    .035       0  112.36     .08       0
#Block Obstruct= 6 ,-1
       0    1.87347.0369   60.66   71.88342.8853   137.3  139.05342.1466
  214.83  218.71342.9147  259.38  272.25 343.048  308.26  312.29343.4149
Bank Sta=101.39,112.36
XS Rating Curve= 0 ,0
Exp/Cntr=0.3,0.1

Type RM Length L Ch R = 1 ,15729.91,23.06,22.01,19.38
XS GIS Cut Line= 6
    -611281.7885   -1046000.8759-611247.89779999   -1045913.8258
    -611243.0385   -1045896.2879    -611241.4543   -1045878.3214
    -611273.2296   -1045770.2109    -611285.8491   -1045607.2642
#Sta/Elev= 30
       0   344.2    5.36  343.93   10.38  341.41   12.22   340.8   34.88  340.79
    34.9  339.36   40.38  339.15    86.3  338.91   97.84  339.94   97.85  337.19
  107.83  337.99  107.89  338.03  107.94  338.63  109.25  338.95  112.92  339.18
  113.68  339.48  124.63  339.37  136.84  338.67  148.48  338.73  164.67  339.97
  212.71  339.75  226.96   340.2  236.88  339.96   300.3   340.2  317.72  339.79
  346.77  339.76  377.88  340.49   383.6  341.02  387.37  342.52  405.77  343.91
#Mann= 3 , 0 , 0
       0      .1       0   97.84    .035       0  109.25     .08       0
#Block Obstruct= 9 ,-1
  125.59  136.26342.0143  142.44  166.88342.3365     191  212.02 342.868
   56.85   77.08342.0844  300.27  334.05343.0232  253.06  265.89343.0455
  353.72  374.44343.1166  170.09  181.11342.9549   234.7  245.66343.0414
Bank Sta=97.84,109.25
XS Rating Curve= 0 ,0
Exp/Cntr=0.3,0.1

Type RM Length L Ch R = 1 ,15707.91,3.89,3.89,3.9
XS GIS Cut Line= 6
    -611297.0154   -1045997.0692-611269.98739999   -1045907.1252
    -611262.9829    -1045890.143    -611257.7215   -1045872.5269
    -611281.2811   -1045780.8493    -611297.0154   -1045616.4002
#Sta/Elev= 30
       0  346.46     .29  346.47     7.4  342.56   11.53  340.63   31.45  340.72
   31.46  339.07   57.35  339.29   68.02  338.94   95.25  338.87   97.93  339.43
   98.03  337.07   101.3  337.03  107.88  337.16  107.95  338.03  108.02  338.39
  115.25  338.84  130.67   338.9  143.77  338.47  159.13  339.67  174.73  339.56
  190.03  339.85  221.21  339.84  238.26  340.07  316.29  339.76  333.17  339.53
  357.76  340.21  371.62  340.94  372.23  340.76  386.69  343.84  390.53   344.3
#Mann= 3 , 0 , 0
       0      .1       0   97.93    .035       0  108.02     .08       0
#Block Obstruct= 6 ,-1
   39.03   57.74342.1694  291.09  330.12342.7108  195.81   209.7342.8094
  151.82  178.41342.3976  137.81  146.51341.7051  230.44  238.06343.0097
Bank Sta=97.93,108.02
XS Rating Curve= 0 ,0
Exp/Cntr=0.3,0.1

--- PPO_Kvasiny_efektiv.g02 (geometry) ---

Geom Title=N-Q10
Program Version=5.03

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
River Reach=Bela            ,Bela_reach

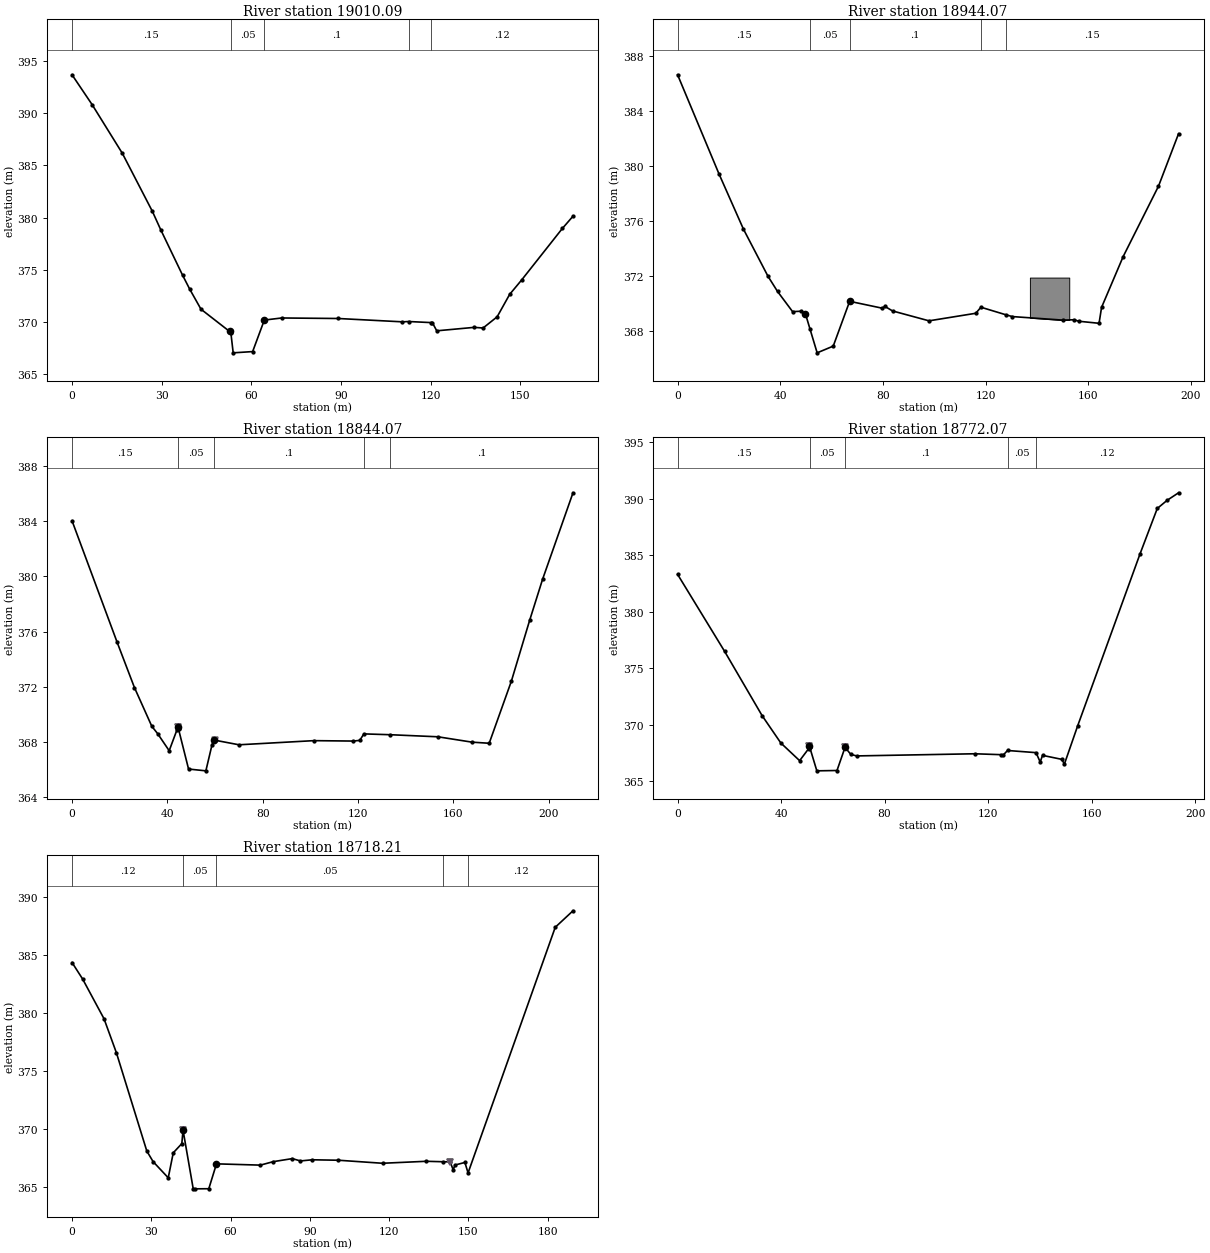
Type RM Length L Ch R = 1 ,19010.09,63.81,66.01,58.86
XS GIS Cut Line= 5
-608502.66209999   -1044593.6857    -608536.6251   -1044560.8986
     -608549.118   -1044545.2805    -608586.5786   -1044508.0775
     -608607.896   -1044465.4426
#Sta/Elev= 28
       0  393.68    6.75  390.81   16.83  386.16    26.9  380.59   29.66  378.85
   36.98  374.49   39.39  373.14   43.16  371.22   52.73  369.09   53.15 368.985
   53.94  367.04   60.45  367.16   64.36  370.18    64.4370.1805   70.18  370.38
   89.09  370.33   110.6  370.01  112.68  370.04     120  369.94  120.58  369.94
  122.07  369.15  134.59  369.48  137.58  369.42  142.28  370.49  146.47  372.64
  150.45  374.01  164.12  378.96  167.67  380.13
#Mann= 5 ,-1 , 0
       0     .15       0   53.15     .05       0    64.4      .1       0
  112.68     .05       0     120     .12       0
Bank Sta=52.73,64.36
XS Rating Curve= 0 ,0
Exp/Cntr=0.3,0.1

Type RM Length L Ch R = 1 ,18944.07,107.06,100,81.52
XS GIS Cut Line= 5
    -608546.4782   -1044642.7763-608578.86259999   -1044608.0005
     -608594.864   -1044596.0024    -608642.9144   -1044514.1948
    -608653.0656   -1044483.0645
#Sta/Elev= 29
       0  386.63   16.09  379.43   25.66  375.39   35.22  371.96   38.92  370.86
   44.79  369.39   48.23  369.42    49.8  369.23   51.56368.1339   54.36  366.39
   60.63  366.88   67.02  370.14   67.03370.1393   79.71  369.64   80.76  369.77
   83.72  369.44   97.93  368.72  116.15  369.27  118.16  369.71   127.9369.1595
  130.38  369.03  150.14  368.77  154.47   368.8  156.24  368.69  164.17  368.54
  165.15   369.7  173.57   373.4  187.32  378.52  195.14  382.34
#Mann= 5 ,-1 , 0
       0     .15       0   51.56     .05       0   67.03      .1       0
  118.16     .05       0   127.9     .15       0
#Block Obstruct= 1 ,-1
  137.23  152.56371.8682
Bank Sta=49.8,67.02
XS Rating Curve= 0 ,0
Exp/Cntr=0.3,0.1

Type RM Length L Ch R = 1 ,18844.07,72.16,72,73.34
XS GIS Cut Line= 6
-608649.34349999   -1044712.1427    -608661.1943   -1044671.2681
    -608666.6842   -1044652.0363-608687.57959999     -1044587.96
    -608711.2657   -1044551.4157    -608740.0273   -1044528.7448
#Sta/Elev= 28
       0  384.04   18.89  375.24   26.18  371.94   33.47  369.13    35.9   368.6
   40.75  367.36   44.03  368.88   44.31  369.11   44.35  369.09   44.67  368.93
   48.88  366.03   56.14   365.9   58.65  367.74   59.34  368.14   59.46368.1367
   70.03  367.79  101.43  368.09     118  368.06  120.69  368.11  122.41  368.58
  133.48  368.52  153.46  368.37  167.81  367.98  174.98   367.9  184.29  372.41
  191.95  376.82  197.36  379.79  210.13  386.07
#Mann= 5 ,-1 , 0
       0     .15       0   44.35     .05       0   59.46      .1       0
  122.41     .05       0  133.48      .1       0
Levee=-1,44.3,369.1,-1,59.9,368.04,,
Bank Sta=44.31,59.34
XS Rating Curve= 0 ,0
Exp/Cntr=0.3,0.1

Type RM Length L Ch R = 1 ,18772.07,49.5,53.87,46.34
XS GIS Cut Line= 5
-608717.01799999   -1044739.5508    -608729.3973    -1044693.413
    -608735.3242   -1044674.3114    -608762.3599   -1044598.1112
    -608783.6774   -1044558.5216
#Sta/Elev= 28
       0  383.29   18.17  376.48   32.67  370.79   39.91  368.37   47.16  366.81
   50.67  367.88   50.91  368.11   50.99368.0506   53.81  365.91    61.6  365.94
    64.7367.9844   64.71  367.99   66.95  367.36   69.23  367.23  114.85  367.42
     125  367.34  125.72  367.28   127.5  367.71  138.51  367.52  140.12  366.69
  141.02  367.28  148.38  366.93  149.49  366.52  154.63  369.91  178.71  385.11
  185.36  389.12  189.15  389.84  193.59  390.51
#Mann= 5 ,-1 , 0
       0     .15       0   50.99     .05       0    64.7      .1       0
   127.5     .05       0  138.51     .12       0
Levee=-1,50.87,368.11,-1,64.69,367.98,,
Bank Sta=50.91,64.71
XS Rating Curve= 0 ,0
Exp/Cntr=0.3,0.1

Type RM Length L Ch R = 1 ,18718.21,29.06,21.79,6.52
XS GIS Cut Line= 5
-608753.54699999   -1044753.4637     -608781.487   -1044705.5211
    -608789.4245   -1044670.2786    -608798.9496    -1044622.336
-608821.80959999   -1044578.8384
#Sta/Elev= 30
       0  384.35    4.01  382.93   12.11  379.51   16.79  376.59   28.31  368.13
   30.69  367.22   36.42  365.83   38.32  367.98   41.56  368.77   42.02  369.93
   45.86   364.9   46.37  364.88   51.77  364.89   54.68  367.03   71.29  366.92
    76.2  367.22   83.37  367.48   86.48  367.28   90.94  367.38  100.86  367.34
  117.53  367.08  134.11  367.25  140.49  367.21  143.13   367.2  144.27  366.52
  144.99  366.93  148.71  367.15  149.91  366.25  182.91  387.38  189.63   388.8
#Mann= 5 ,-1 , 0
       0     .12       0   42.02     .05       0   54.68     .05       0
  140.49     .05       0  149.91     .12       0
Levee=-1,42.02,369.93,-1,142.96,367.15,,
Bank Sta=42.02,54.68
XS Rating Curve= 0 ,0
Exp/Cntr=0.3,0.1