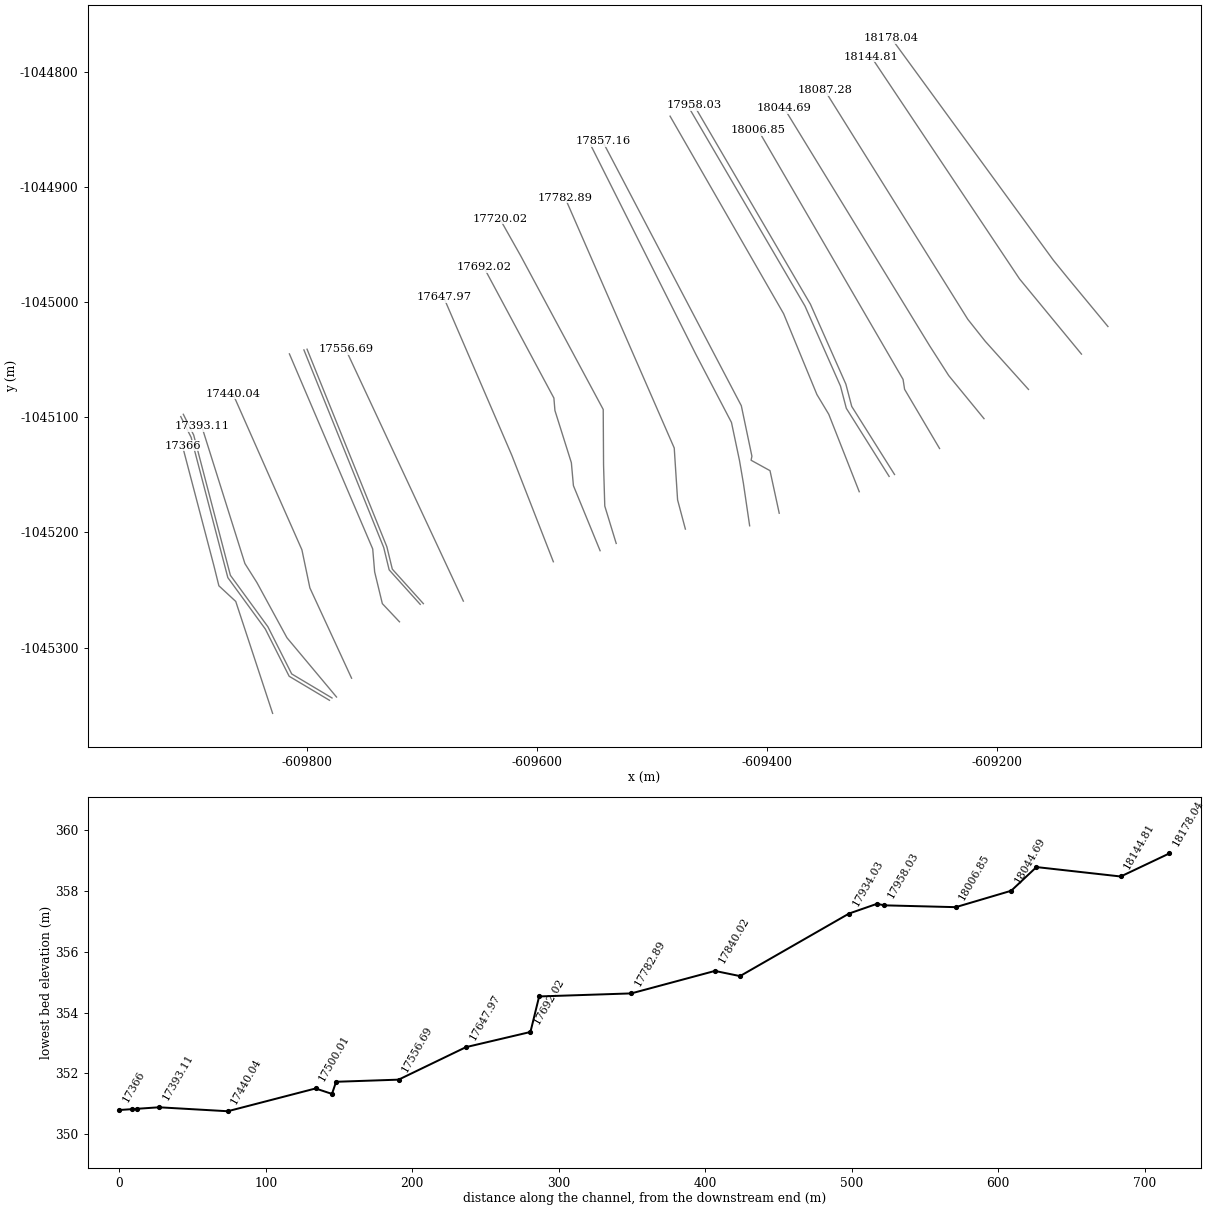
HEC-RAS study PPO_Kvasiny_efektiv.prj: PPO_Kvasiny_efektivita

--- PPO_Kvasiny_efektiv.g02 (geometry) --- (continued)

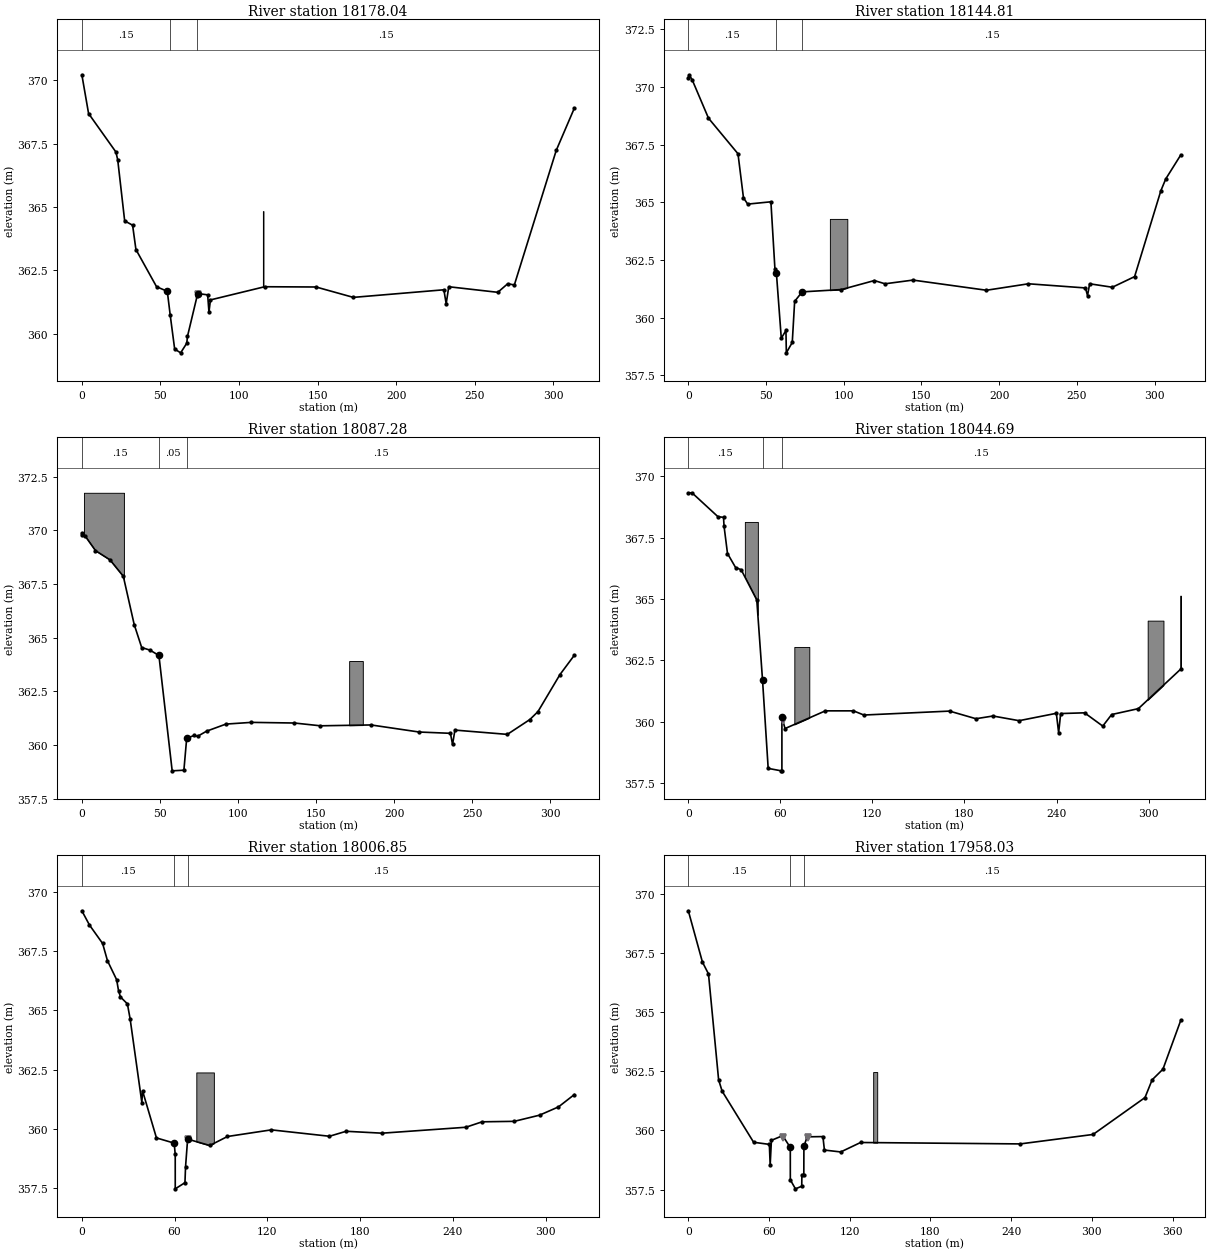
Type RM Length L Ch R = 1 ,18178.04,32.9,33.23,33.2
XS GIS Cut Line= 4
    -609103.6508   -1045021.0811-609138.55079999   -1044978.8772
    -609151.1605   -1044963.3531    -609291.7859   -1044770.6855
#Sta/Elev= 30
       0  370.22    4.28  368.69   21.67  367.17   22.82  366.86   27.24  364.45
   32.28  364.28    34.4  363.32   47.53  361.85   54.36  361.67   56.22360.7247
   59.04  359.39   62.85  359.24   66.74  359.62   67.19  359.89   73.29 361.474
   73.82  361.58   80.03  361.53   80.86  360.85   81.81  361.33  116.27  361.85
  148.98  361.84   172.7  361.43   230.3  361.73  231.77  361.18  233.41  361.85
   264.6  361.63  270.94  361.97  275.13  361.92  301.82  367.24  313.29   368.9
#Mann= 3 ,-1 , 0
       0     .15       0   56.22     .05       0   73.29     .15       0
Levee=0,,,-1,73.96,361.53,,
#Block Obstruct= 1 ,-1
  115.17  115.55 364.834
Bank Sta=54.36,73.82
XS Rating Curve= 0 ,0
Exp/Cntr=0.3,0.1

Type RM Length L Ch R = 1 ,18144.81,57.17,57.54,57.11
XS GIS Cut Line= 3
    -609126.6578   -1045045.0457    -609180.4545    -1044979.726
-609309.43919999   -1044786.5799
#Sta/Elev= 30
       0   370.4     .58  370.52     2.5   370.3   12.98  368.64   31.96   367.1
   35.49  365.19   38.21  364.92   53.14  365.02   55.75  362.09   56.66  361.95
   59.82  359.11   62.82  359.45   63.07  358.48   66.88  358.93   68.42  360.71
   73.26  361.12   98.47  361.22  119.71  361.61  126.56  361.47  144.56  361.63
  191.84  361.19  218.85  361.47  255.53  361.29  256.86  360.96  258.24  361.47
  272.83  361.32  287.16  361.78  304.06   365.5   307.2  366.01  316.88  367.05
#Mann= 3 , 0 , 0
       0     .15       0   56.66     .05       0   73.26     .15       0
#Block Obstruct= 1 ,-1
   91.09   102.3364.2794
Bank Sta=56.66,73.26
XS Rating Curve= 0 ,0
Exp/Cntr=0.3,0.1

Type RM Length L Ch R = 1 ,18087.28,17.9,17.24,16.41
XS GIS Cut Line= 4
    -609172.6953   -1045075.7374-609210.22019999   -1045033.9658
    -609225.4338   -1045014.7835-609349.78819999   -1044815.6841
#Sta/Elev= 30
       0  369.87     .34  369.79     1.9  369.76    8.72  369.06   17.99  368.63
   26.56  367.86   33.53  365.61   38.32  364.54   43.62  364.42   49.35  364.17
   57.84  358.79   65.35  358.82   67.14  360.31   71.92  360.44   74.13   360.4
   79.88  360.64   92.26  360.97  108.58  361.05  136.13  361.02  152.81  360.89
   185.2  360.93  215.99   360.6  236.03  360.54   237.4  360.02  238.91  360.69
  272.48  360.49  286.86  361.18  292.07  361.55  306.19  363.28  315.38  364.18
#Mann= 3 , 0 , 0
       0     .15       0   49.35     .05       0   67.14     .15       0
#Block Obstruct= 2 ,-1
    1.34   26.94371.7567  171.18  179.93363.9105
Bank Sta=49.35,67.14
XS Rating Curve= 0 ,0
Exp/Cntr=0.3,0.1

Type RM Length L Ch R = 1 ,18044.69,39.68,37.85,34.98
XS GIS Cut Line= 4
    -609211.3246   -1045101.1375    -609241.9703   -1045063.7315
    -609258.5068   -1045037.9345    -609384.8456   -1044831.5591
#Sta/Elev= 30
       0  369.31    2.39  369.32   19.27  368.35   22.94  368.32   23.29  367.96
   25.53  366.85   30.81  366.28   34.45  366.19   44.62  364.96   48.36  361.71
   52.05  358.11   60.57  358.01   60.99  358.01      61  360.18   63.04  359.73
   89.32  360.45  107.65  360.45   114.4  360.28  170.26  360.44  187.43  360.13
  198.58  360.24  215.58  360.05  239.86  360.35  241.36  359.56  242.68  360.34
  258.25  360.37  270.11  359.83  275.91   360.3  293.32  360.54  320.97  362.15
#Mann= 3 , 0 , 0
       0     .15       0   48.36     .05       0      61     .15       0
Levee=0,,,-1,61.43,360.05,,
#Block Obstruct= 4 ,-1
   36.85   45.32 368.134   69.09   78.84363.0494  299.39  309.67364.1195
  320.66  320.97365.1357
Bank Sta=48.36,61
XS Rating Curve= 0 ,0
Exp/Cntr=0.3,0.1

Type RM Length L Ch R = 1 ,18006.85,47.57,48.82,45.88
XS GIS Cut Line= 4
-609249.95389999   -1045127.0667-609280.33489999   -1045075.6377
    -609281.6579   -1045067.0388    -609407.3352   -1044850.7415
#Sta/Elev= 30
       0  369.21    4.91  368.61   13.43  367.83   16.58   367.1    22.5   366.3
   23.75  365.83      25  365.57   29.46  365.28   31.22  364.65   38.82  361.11
   39.25  361.61   48.26  359.62   59.73   359.4   60.41  358.92   60.42  357.47
    66.7  357.73   67.07  358.39   68.43  359.57   82.73   359.3   94.22  359.68
  122.56  359.96  160.18  359.69  170.96   359.9  194.24  359.82  248.41  360.07
  258.94   360.3  279.72  360.32  296.07  360.58  308.35  360.93  318.59  361.45
#Mann= 3 , 0 , 0
       0     .15       0   59.73     .05       0   68.43     .15       0
Levee=0,,,-1,68.59,359.54,,
#Block Obstruct= 1 ,-1
   74.05    85.4362.3846
Bank Sta=59.73,68.43
XS Rating Curve= 0 ,0
Exp/Cntr=0.3,0.1

Type RM Length L Ch R = 1 ,17958.03,4.98,4.96,5.01
XS GIS Cut Line= 5
-609289.07889999   -1045149.6626    -609326.2672   -1045090.5068
    -609331.3531   -1045071.1643-609362.16739999   -1045001.6811
     -609463.228   -1044828.8855
#Sta/Elev= 30
       0  369.29   10.49  367.12   14.99  366.62   22.52  362.14   25.14  361.66
   48.53   359.5   60.23  359.41   60.84  358.54   61.76  359.58   70.13  359.78
   75.55 359.302    75.8   359.3   75.82  357.91   79.63  357.53    84.3  357.64
   84.42  358.13   85.85  358.13   85.91  359.33   86.02359.3391   88.33  359.73
  100.05  359.74  101.16  359.17  113.29  359.09  128.04  359.49  246.69  359.43
  300.86  359.83  339.45  361.39  344.75  362.14  352.79  362.59  366.06  364.66
#Mann= 3 ,-1 , 0
       0     .15       0   75.55     .04       0   86.02     .15       0
Levee=-1,70.67,359.7,-1,88.68,359.7,,
#Block Obstruct= 1 ,-1
   137.4   140.4362.4691
Bank Sta=75.55,86.02
XS Rating Curve= 0 ,0
Exp/Cntr=0.5,0.3

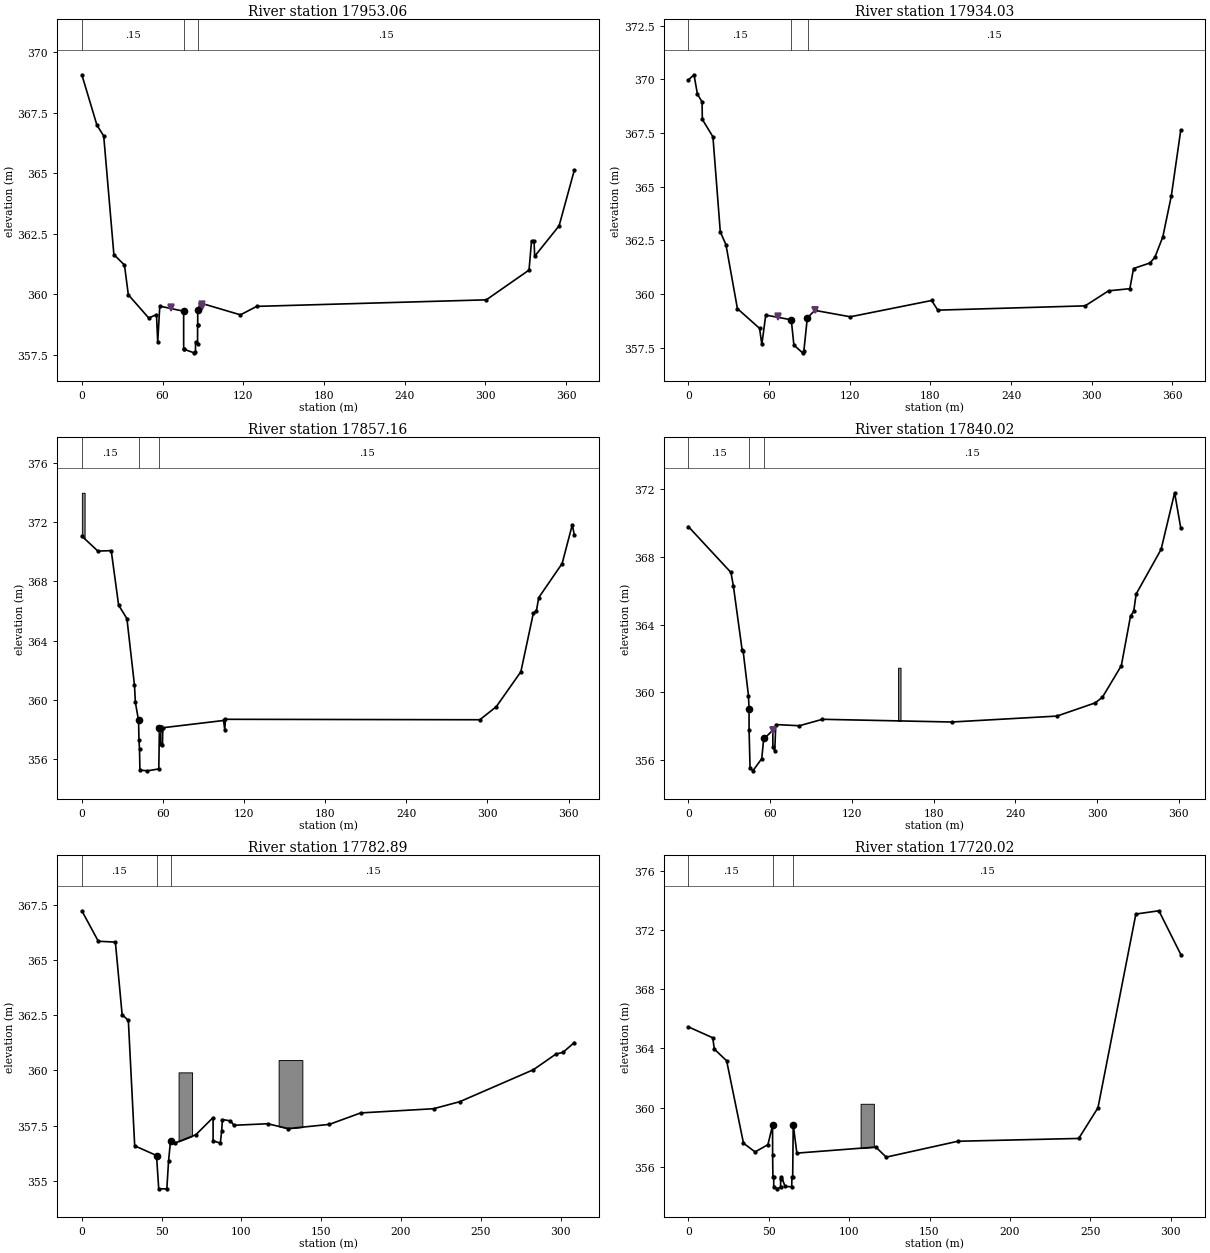
Type RM Length L Ch R = 1 ,17953.06,18.09,19.04,21.99
XS GIS Cut Line= 5
    -609293.7773   -1045151.3166    -609330.9657   -1045092.1607
    -609336.0515   -1045072.8183    -609366.8658   -1045003.3351
-609467.92639999   -1044830.5395
#Sta/Elev= 30
       0  369.07    11.2  366.99   16.25  366.54   23.81  361.64   31.67  361.21
   34.54  359.98   49.71  359.02   55.47  359.16   56.39  358.03   57.93  359.51
   75.67   359.3   75.68  357.75   75.77  357.73   83.46  357.58   84.45  357.61
   84.51  358.04   86.02  357.94   86.03  358.73   86.12  358.74   86.13  359.33
   88.09  359.64  117.88  359.15     130   359.5  300.62  359.77  332.39     361
  334.26  362.21  336.13  362.19  336.58  361.57  354.75  362.83  366.06  365.13
#Mann= 3 , 0 , 0
       0     .15       0   75.67     .04       0   86.13     .15       0
Levee=-1,66.05,359.48,-1,89.61,359.48,,
Bank Sta=75.67,86.13
XS Rating Curve= 0 ,0
Exp/Cntr=0.5,0.3

Type RM Length L Ch R = 1 ,17934.03,65.98,74.44,72.11
XS GIS Cut Line= 5
    -609319.7439   -1045164.6074-609346.21489999    -1045097.348
    -609356.5102   -1045080.2014-609385.44929999   -1045009.9555
    -609484.1037    -1044838.313
#Sta/Elev= 30
       0  369.98    4.24  370.22     6.8  369.31   10.23  368.96   10.42  368.14
    18.3  367.33   23.78   362.9   27.99   362.3   36.51  359.32   52.99   358.4
   54.67  357.65   57.58  359.02   76.56   358.8   78.51  357.62   84.98  357.26
   85.93  357.35   88.49  358.89   94.07  359.24  120.45  358.94  180.97   359.7
   185.5  359.25  295.12  359.45   312.5  360.15  328.34  360.25  331.09  361.19
  343.38  361.45  347.01  361.72  352.88  362.67   359.2  364.58  366.23  367.65
#Mann= 3 ,-1 , 0
       0     .15       0   76.56     .04       0    88.7     .15       0
Levee=-1,66.74,358.96,-1,94.23,359.25,,
Bank Sta=76.56,88.49
XS Rating Curve= 0 ,0
Exp/Cntr=0.3,0.1

Type RM Length L Ch R = 1 ,17857.16,23.71,17.14,11.38
XS GIS Cut Line= 6
    -609389.2674   -1045183.2983-609397.27959999   -1045146.3236
-609413.71029999   -1045137.2749    -609412.9959   -1045133.7824
-609422.20239999   -1045089.9074    -609542.6629   -1044860.2654
#Sta/Elev= 30
       0  371.05   11.88  370.04   21.73  370.07   27.19  366.39   33.34  365.48
   38.94  360.97   39.59  359.83   41.94   358.6   42.26  357.26   42.66  356.66
   42.95  355.25   48.54   355.2   56.92  355.33   57.37  358.08   58.25  357.99
   58.31  357.04   59.65  356.96   59.87  358.11  104.85   358.6   105.7  357.95
  106.21  358.68  294.39  358.65  306.56  359.53  324.74  361.89     334  365.85
   336.2  365.98  337.98   366.9  355.28   369.2  362.81  371.82   364.3  371.12
#Mann= 3 , 0 , 0
       0     .15       0   41.94     .05       0   57.37     .15       0
Levee=0,,,-1,57.79,358.05,,
#Block Obstruct= 1 ,-1
       0    2.05373.9771
Bank Sta=41.94,57.37
XS Rating Curve= 0 ,0
Exp/Cntr=0.3,0.1

Type RM Length L Ch R = 1 ,17840.02,57.92,57.13,54.77
XS GIS Cut Line= 6
-609414.96049999    -1045194.222    -609420.4036   -1045157.2118
-609423.78489999   -1045137.4997    -609430.7512   -1045104.4406
    -609461.8814    -1045044.887    -609553.0165   -1044863.5194
#Sta/Elev= 30
       0  369.78   31.27  367.07   33.07  366.27   39.48   362.5   40.23  362.42
   44.13  359.81   44.54  359.04   44.59  357.75   45.31  355.55   47.35  355.37
   53.89  356.09   55.31  357.26   55.77  357.28   62.02  357.77   62.03  356.76
   63.43  356.55   64.18   358.1   81.51  358.03   98.41  358.41   193.3  358.25
   270.5   358.6  298.63  359.38  303.86  359.71  317.73  361.57  324.51  364.51
   326.8  364.77  328.62   365.8  346.91  368.43  356.85  371.77  361.37  369.68
#Mann= 3 ,-1 , 0
       0     .15       0   44.37     .05       0   55.44     .15       0
Levee=0,,,-1,61.97,357.76,,
#Block Obstruct= 1 ,-1
   153.9  155.72361.4517
Bank Sta=44.54,55.77
XS Rating Curve= 0 ,0
Exp/Cntr=0.3,0.1

Type RM Length L Ch R = 1 ,17782.89,62.55,62.87,61.97
XS GIS Cut Line= 4
    -609470.8038    -1045197.095-609477.57719999    -1045171.695
    -609480.4835   -1045126.6469    -609575.3674   -1044909.2278
#Sta/Elev= 30
       0  367.23   10.31  365.85   21.01  365.81   25.25  362.52   29.14  362.26
   33.12  356.58   46.79  356.14   48.18  354.63   53.26  354.63   54.36  355.91
   55.59  356.81   58.12   356.7   71.43  357.08   82.25  357.86   82.26  356.81
   86.78   356.7   87.64  357.27   88.13  357.77   93.12  357.71   95.37  357.51
  116.46  357.58  129.29  357.36  155.07  357.55  174.76  358.07  220.41  358.26
  236.89  358.58  283.05  360.03  297.17  360.74  301.47  360.81  308.65  361.26
#Mann= 3 , 0 , 0
       0     .15       0   46.79     .05       0   55.59     .15       0
#Block Obstruct= 2 ,-1
  123.33   138.2360.4653   60.62   69.08 359.908
Bank Sta=46.79,55.59
XS Rating Curve= 0 ,0
Exp/Cntr=0.3,0.1

Type RM Length L Ch R = 1 ,17720.02,5.95,5.94,5.93
XS GIS Cut Line= 6
-609530.90949999   -1045209.5616-609540.83509999   -1045177.0778
     -609541.896   -1045141.5778    -609542.1886   -1045093.1615
    -609613.9235   -1044959.6171    -609631.9701   -1044927.5846
#Sta/Elev= 30
       0  365.46   15.22  364.72   16.15  363.96   23.83  363.17   34.31  357.61
   41.52  357.02    49.5  357.51    52.4  358.81   52.43  356.79   52.61  355.32
   53.11  355.32   53.12  354.64   55.31  354.53   57.39  354.66   57.44  355.22
   57.94  355.34   60.19  354.69   64.31  354.67   64.44  355.31   64.91  355.32
   65.24  358.87    67.5  356.94  116.56  357.35  123.08  356.67  167.63  357.74
  242.81  357.93  254.77     360  278.34  373.07  292.67  373.29  306.28  370.34
#Mann= 3 ,-1 , 0
       0     .15       0    52.4     .04       0   65.24     .15       0
#Block Obstruct= 1 ,-1
  107.15  115.38360.2692
Bank Sta=52.4,65.24
XS Rating Curve= 0 ,0
Exp/Cntr=0.5,0.3

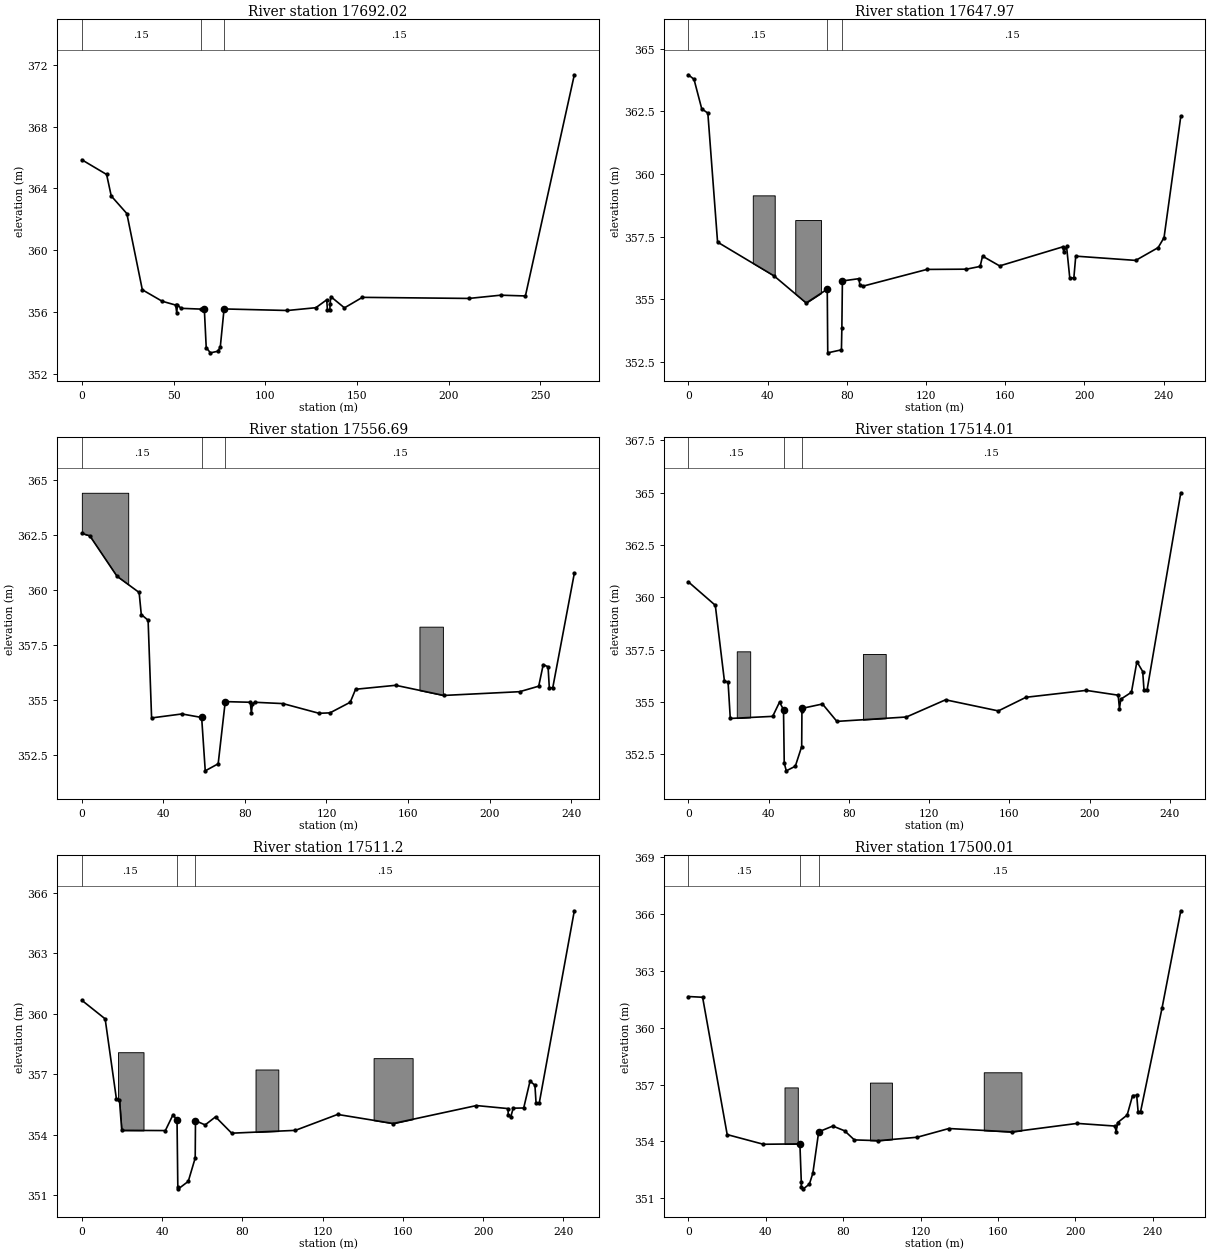
Type RM Length L Ch R = 1 ,17692.02,41.2,44.05,46.63
XS GIS Cut Line= 6
-609544.89559999   -1045215.8779-609568.07849999   -1045159.3655
-609569.86809999   -1045139.4457    -609584.1468   -1045094.0638
-609585.04899999   -1045083.2359-609645.95609999   -1044969.5427
#Sta/Elev= 30
       0  365.85    13.5   364.9   16.02  363.51   24.53  362.37   32.97  357.44
   43.75   356.7   51.15  356.45   51.73  355.95   52.11  356.46   54.11  356.24
   64.97  356.19   66.77  356.21   67.81  353.69   70.12  353.36   74.01  353.46
   75.45  353.71   77.54   356.2   112.1   356.1  127.58  356.28  133.49  356.79
  133.91  356.12   135.2  356.12  135.36  356.53   135.7     357  143.17  356.27
  152.93  356.95  211.03  356.88  228.34  357.09  241.83  357.04   268.5  371.35
#Mann= 3 ,-1 , 0
       0     .15       0   64.97    .045       0   77.71     .15       0
Bank Sta=66.77,77.54
XS Rating Curve= 0 ,0
Exp/Cntr=0.3,0.1

Type RM Length L Ch R = 1 ,17647.97,44.69,45.95,47.64
XS GIS Cut Line= 4
-609585.52739999   -1045225.4584-609605.14359999   -1045175.1529
-609621.57099999    -1045133.065    -609680.7776   -1044995.7996
#Sta/Elev= 30
       0  363.96    2.87  363.78    6.78   362.6    9.86  362.43   14.77  357.28
   43.32  355.93   59.51  354.85   70.15   355.4    70.4  352.86   77.31  352.98
   77.53  353.86    77.8  355.73   86.09  355.82   86.61  355.58   88.12  355.52
  120.47  356.19  140.44   356.2  147.34  356.31  148.56  356.72   157.2  356.33
  189.04  357.09  189.57  356.89  190.98  357.11   192.6  355.85  194.66  355.85
  195.62  356.72  225.89  356.55  237.22  357.06   240.2  357.46  248.66   362.3
#Mann= 3 , 0 , 0
       0     .15       0   70.15    .043       0    77.8     .15       0
#Block Obstruct= 2 ,-1
   32.55   43.62359.1464   53.99   67.02358.1605
Bank Sta=70.15,77.8
XS Rating Curve= 0 ,0
Exp/Cntr=0.3,0.1

Type RM Length L Ch R = 1 ,17556.69,44.71,42.68,40.34
XS GIS Cut Line= 2
    -609663.7304   -1045259.6598    -609765.9736   -1045040.7789
#Sta/Elev= 30
       0  362.56    3.89  362.45    17.2  360.62    28.1  359.88   29.15  358.88
    32.5  358.62   34.21  354.19    49.1  354.37   58.77  354.21   60.53  351.79
   66.87  352.11   70.34  354.93   82.63   354.9   83.15  354.41   83.69  354.83
   84.78   354.9   98.66  354.84  116.35   354.4  121.72  354.42  131.64   354.9
  134.28  355.49  153.96  355.67  177.53  355.21  214.78  355.38  224.11  355.63
  226.33  356.61   228.7  356.51  229.31  355.56     231  355.56  241.58  360.75
#Mann= 3 , 0 , 0
       0     .15       0   58.77     .04       0   70.34     .15       0
#Block Obstruct= 2 ,-1
   165.6  177.11358.3292       0   22.74 364.402
Bank Sta=58.77,70.34
XS Rating Curve= 0 ,0
Exp/Cntr=0.3,0.1

Type RM Length L Ch R = 1 ,17514.01,2.8,2.8,2.82
BEGIN DESCRIPTION:
17708  PF 227 ŽELEZNÝ MOSTEK V KVASINÁCH (F39)
END DESCRIPTION:
XS GIS Cut Line= 4
    -609698.4602   -1045261.8683     -609725.443   -1045231.8903
-609730.18059999   -1045212.4594-609799.52079999   -1045040.7983
#Sta/Elev= 30
       0  360.74   13.45  359.62   17.99  356.01   19.82  355.95   20.92  354.22
   42.05  354.32   45.47     355   47.45354.6392   47.81  352.09   48.83  351.72
   53.33  351.94   56.51  352.88   56.63  354.56   56.64   354.7   66.87  354.91
   74.05  354.08  108.73  354.29  128.22  355.11  154.53  354.58  168.29  355.23
  198.31  355.56  214.27  355.33  214.89  354.69  215.58  355.14  220.87  355.47
  223.59  356.93  226.48  356.46  227.14  355.57  228.65  355.57  245.47  364.99
#Mann= 3 ,-1 , 0
       0     .15       0   47.45     .04       0   56.63     .15       0
#Block Obstruct= 2 ,-1
   24.15   30.84357.4231   87.04   98.39357.2969
Bank Sta=47.45,56.64
XS Rating Curve= 0 ,0
Exp/Cntr=0.5,0.3

Type RM Length L Ch R = 1 ,17511.2 ,12.67,11.2,9.7
XS GIS Cut Line= 4
    -609701.1935   -1045262.4972-609728.17619999   -1045232.5193
-609732.91389999   -1045213.0884-609802.25409999   -1045041.4272
#Sta/Elev= 30
       0  360.67   11.61  359.75   17.21  355.79   18.74  355.74   19.88  354.22
   41.62  354.21   45.47     355   47.44  354.71   47.83  351.43   48.13  351.32
   53.04  351.69    56.5  352.85   56.64   354.7   61.45  354.49   66.63  354.89
   74.68  354.08  106.42  354.22  127.47  355.01  155.19  354.56  196.68  355.45
  212.48   355.3  212.49  354.98  213.78  354.89  215.01  355.32  220.24  355.33
  223.38  356.66  225.83  356.46   226.4  355.57  227.98  355.57  245.47  365.11
#Mann= 3 , 0 , 0
       0     .15       0   47.44     .04       0   56.64     .15       0
#Block Obstruct= 3 ,-1
   18.01   30.73358.0956   86.57   97.92357.2387  145.42  164.87357.8016
Bank Sta=47.44,56.64
XS Rating Curve= 0 ,0
Exp/Cntr=0.5,0.3

Type RM Length L Ch R = 1 ,17500.01,58,59.97,58.41
XS GIS Cut Line= 5
-609719.21379999    -1045277.659    -609734.1021   -1045261.8683
     -609740.789   -1045234.2777    -609742.4705   -1045214.3485
-609814.86039999   -1045044.8588
#Sta/Elev= 30
       0  361.64    7.38   361.6   20.08  354.36   38.77  353.85   57.64  353.87
   58.36  351.86   58.37  351.62   59.47   351.5   62.53  351.75   64.32  352.32
   67.25  354.44   67.66  354.52   74.65  354.81   80.73  354.56   85.77  354.08
   98.15  354.04  118.21  354.22   134.6  354.68  167.05   354.5  200.88  354.95
  220.42  354.81  220.99   354.5  221.74  354.99  226.68  355.39   229.5  356.42
  231.61  356.43  232.34  355.57  233.62  355.57  244.74  361.05  254.39  366.16
#Mann= 3 , 0 , 0
       0     .15       0   57.64     .04       0   67.66     .15       0
#Block Obstruct= 3 ,-1
   49.69   56.55356.8469   93.82  105.17357.1008  152.62  172.07357.6448
Bank Sta=57.64,67.66
XS Rating Curve= 0 ,0
Exp/Cntr=0.3,0.1

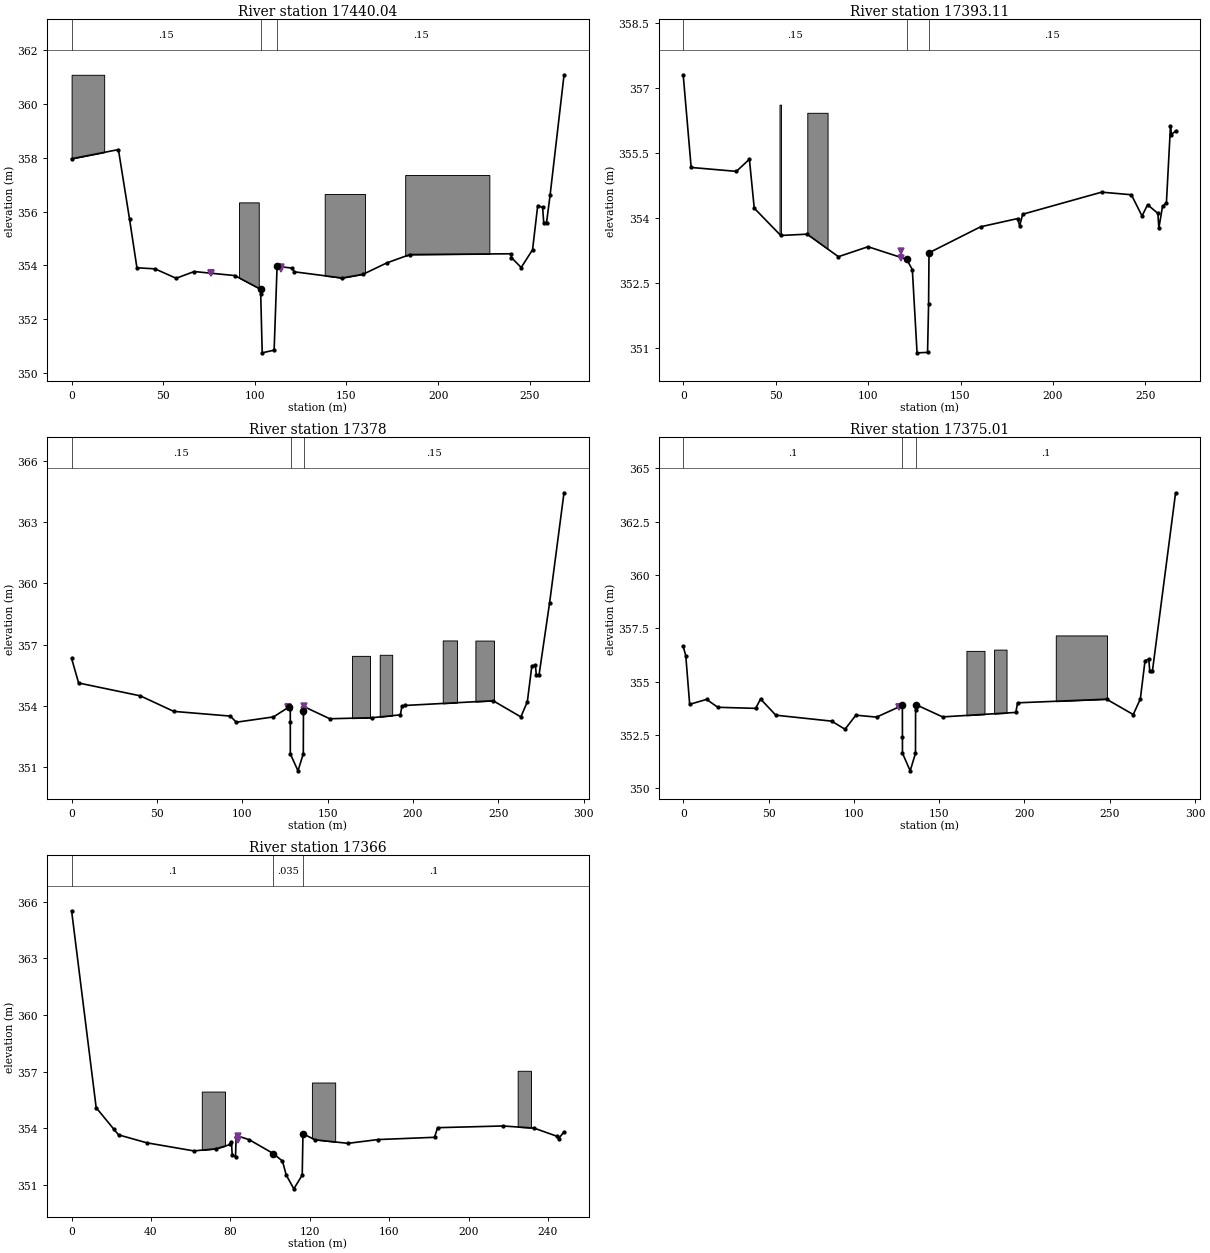
Type RM Length L Ch R = 1 ,17440.04,41.3,46.93,51.33
XS GIS Cut Line= 4
-609760.83949999    -1045326.651-609797.06219999   -1045248.2126
    -609803.9891   -1045215.1089    -609864.0548   -1045079.3023
#Sta/Elev= 29
       0  357.96   25.55   358.3   31.64  355.71   35.65  353.91   45.53  353.87
   57.03  353.52   66.93  353.77   89.06  353.62  103.17  353.11   103.2  352.94
  104.02  350.75  110.53  350.85  112.14  353.96  120.22   353.9  121.54  353.76
  147.61  353.53  159.11  353.67     172  354.09  184.58   354.4  239.73  354.43
  240.01  354.29  245.36  353.92  251.56  354.58  254.38  356.22  257.06  356.15
  257.65  355.59   259.2  355.59  261.12   356.6  268.72  361.06
#Mann= 3 , 0 , 0
       0     .15       0  103.17     .04       0  112.14     .15       0
Levee=-1,76.04,353.71,-1,114.49,353.85,,
#Block Obstruct= 4 ,-1
       0   17.78361.0793  182.05  227.99357.3547  138.13  160.15356.6496
   91.36  102.14356.3394
Bank Sta=103.17,112.14
XS Rating Curve= 0 ,0
Exp/Cntr=0.3,0.1

Type RM Length L Ch R = 1 ,17393.11,13.26,15.1,14.97
XS GIS Cut Line= 5
    -609773.9127   -1045343.0054    -609816.9842   -1045291.5139
-609843.09259999   -1045243.5518-609853.51619999   -1045227.0443
    -609891.0705   -1045107.7374
#Sta/Elev= 30
       0   357.3    4.31  355.16   28.77  355.07   35.81  355.35   38.43  354.22
   52.76  353.59   67.02  353.62   83.96   353.1   99.99  353.33  120.87  353.04
  123.95   352.8   126.5  350.88  132.18  350.89  132.74  352.01  132.96  353.19
  160.85  353.79  180.88  353.98  182.01  353.81  183.61  354.08  226.35  354.59
  242.41  354.53  248.19  354.04   251.2   354.3  256.76   354.1  257.29  353.76
   259.3  354.27  261.37  354.34  263.58  356.12  264.05  355.92  266.34     356
#Mann= 3 , 0 , 0
       0     .15       0  120.87     .04       0  132.96     .15       0
Levee=-1,117.96,353.22,0,,,,
#Block Obstruct= 2 ,-1
   52.09    52.9356.6096   67.13    78.1356.4224
Bank Sta=120.87,132.96
XS Rating Curve= 0 ,0
Exp/Cntr=0.3,0.1

Type RM Length L Ch R = 1 ,17378   ,2.96,2.99,2.78
XS GIS Cut Line= 6
     -609777.842   -1045343.8274-609812.85159999     -1045322.95
    -609833.5683   -1045281.9181    -609866.1356    -1045237.247
    -609898.0165   -1045115.3894    -609907.0396   -1045097.3429
#Sta/Elev= 30
       0  356.33    4.12  355.13   40.29   354.5   59.87  353.74   93.02  353.51
   96.51  353.21  118.31  353.47  127.69  353.97  128.16  353.84  128.17  353.23
  128.18  351.66  132.69  350.83  135.79  351.67  135.87  353.64   135.9  353.74
  136.49  353.96   151.3  353.38  175.95  353.43  192.67  353.57  193.59  353.99
  195.42  354.03  247.07  354.26  263.29  353.47  267.08  354.21  269.69  355.94
  271.77  356.02  272.35  355.51  273.92  355.51  280.14  359.06  288.57  364.44
#Mann= 3 ,-1 , 0
       0     .15       0  128.43     .04       0  136.02     .15       0
Levee=-1,127,353.97,-1,136.06,353.99,,
#Block Obstruct= 4 ,-1
   164.3  174.89356.4578  180.57  187.88356.5107   217.5   225.9357.2125
  236.65  247.52 357.206
Bank Sta=127.69,135.9
XS Rating Curve= 0 ,0
Exp/Cntr=0.5,0.3

Type RM Length L Ch R = 1 ,17375.01,8.74,9.01,9.67
XS GIS Cut Line= 6
    -609780.0582   -1045345.8438    -609815.0678   -1045324.9665
-609835.78449999   -1045283.9345-609868.35179999   -1045239.2635
    -609900.2327   -1045117.4058     -609909.256   -1045099.3593
#Sta/Elev= 30
       0  356.66    1.51  356.22     3.8  353.94   13.71  354.17   20.31   353.8
   42.47  353.75   45.33  354.19   54.28  353.43   87.05  353.15   94.83  352.77
   101.2  353.43  113.33  353.34  128.45  353.89  128.49  352.43   128.5  351.65
  133.03  350.82  136.13  351.64   136.2  353.67  136.26  353.93  152.01  353.35
  194.94  353.56  195.97  354.01  248.13  354.18  263.75  353.46  267.91  354.19
  270.65  355.98  272.83  356.06  273.43  355.51  275.01  355.51  288.57  363.86
#Mann= 3 , 0 , 0
       0      .1       0  128.45     .04       0  136.26      .1       0
Levee=-1,126.27,353.8,0,,,,
#Block Obstruct= 3 ,-1
  165.99  176.58 356.446  182.19   189.5356.5049  218.36  248.38357.1706
Bank Sta=128.45,136.26
XS Rating Curve= 0 ,0
Exp/Cntr=0.5,0.3

Type RM Length L Ch R = 1 ,17366   ,28.61,25.35,19.86
XS GIS Cut Line= 5
    -609829.4397   -1045357.2129    -609861.4726   -1045259.9622
    -609876.1358   -1045246.3611    -609880.4211   -1045229.0826
    -609907.8099   -1045124.7443
#Sta/Elev= 30
       0  365.52   12.38  355.09   21.35  353.94   23.66  353.65    37.8  353.23
    61.6   352.8    72.7  352.91   79.98  353.14   80.52  353.26   80.93  352.56
   82.58   352.5    82.9  353.53    83.5   353.6   89.54  353.39   101.6  352.66
  106.24  352.26  108.13  351.52  111.97  350.79  116.19  351.52  116.56  353.71
   122.6  353.39  139.25   353.2  154.31   353.4  182.83  353.52  184.41  354.03
  217.23  354.12  232.88  354.01  244.41  353.58   245.3  353.44  248.07  353.81
#Mann= 3 , 0 , 0
       0      .1       0   101.6    .035       0  116.56      .1       0
Levee=-1,84.01,353.38,0,,,,
#Block Obstruct= 3 ,-1
   65.59   77.29355.9429  121.07  132.79 356.422  224.73  231.42357.0443
Bank Sta=101.6,116.56
XS Rating Curve= 0 ,0
Exp/Cntr=0.3,0.1