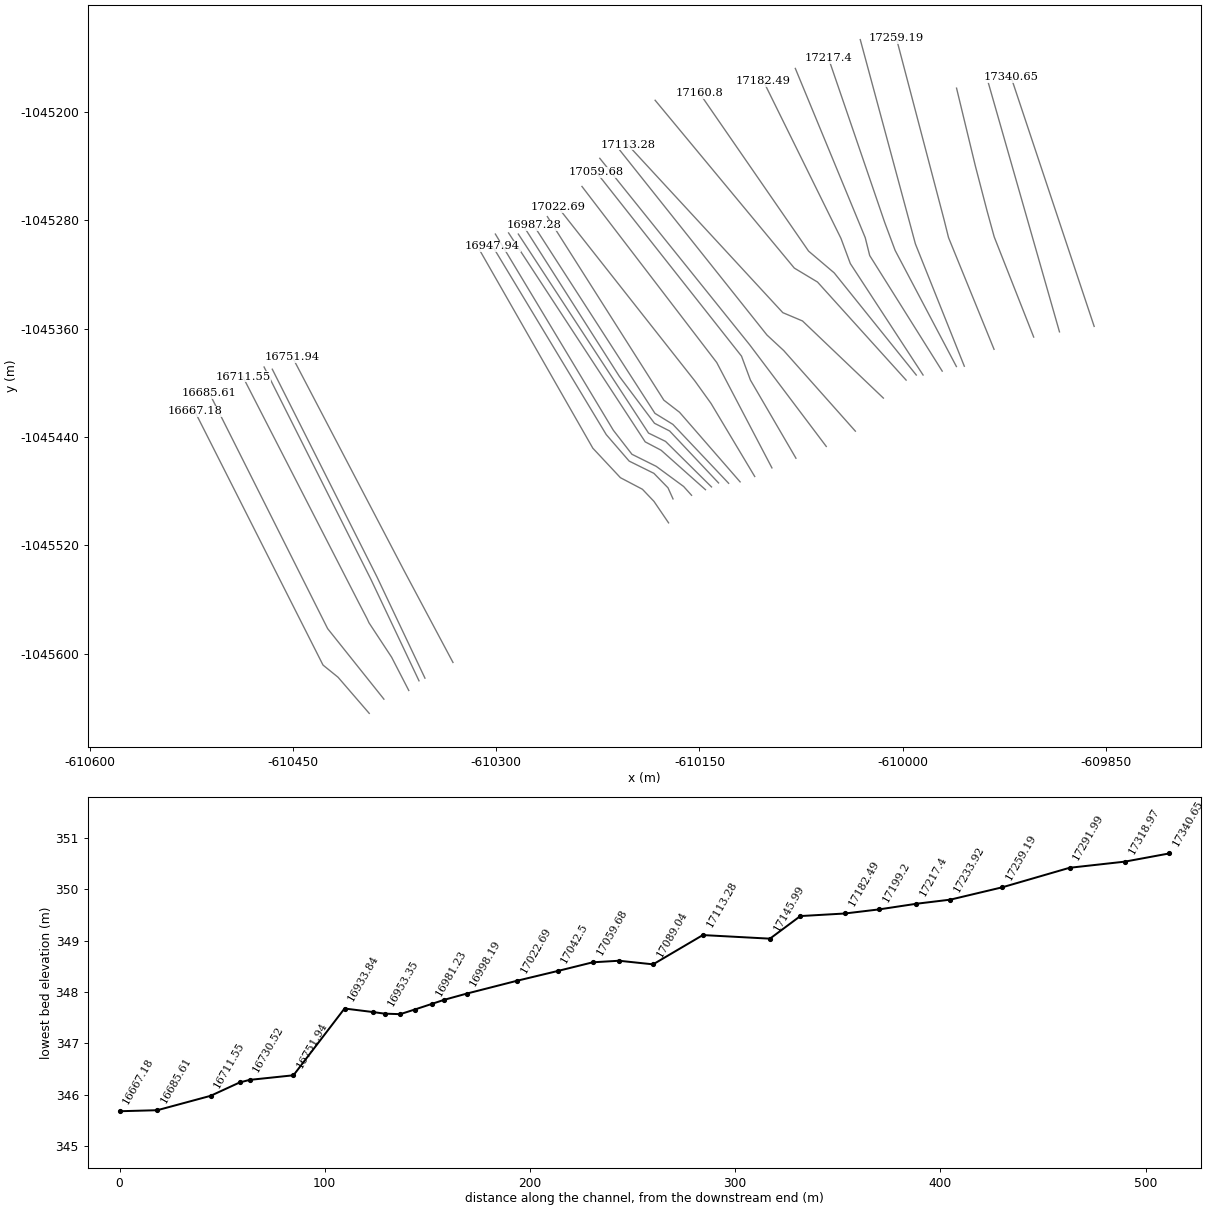
HEC-RAS study PPO_Kvasiny_efektiv.prj: PPO_Kvasiny_efektivita

--- PPO_Kvasiny_efektiv.g02 (geometry) --- (continued)

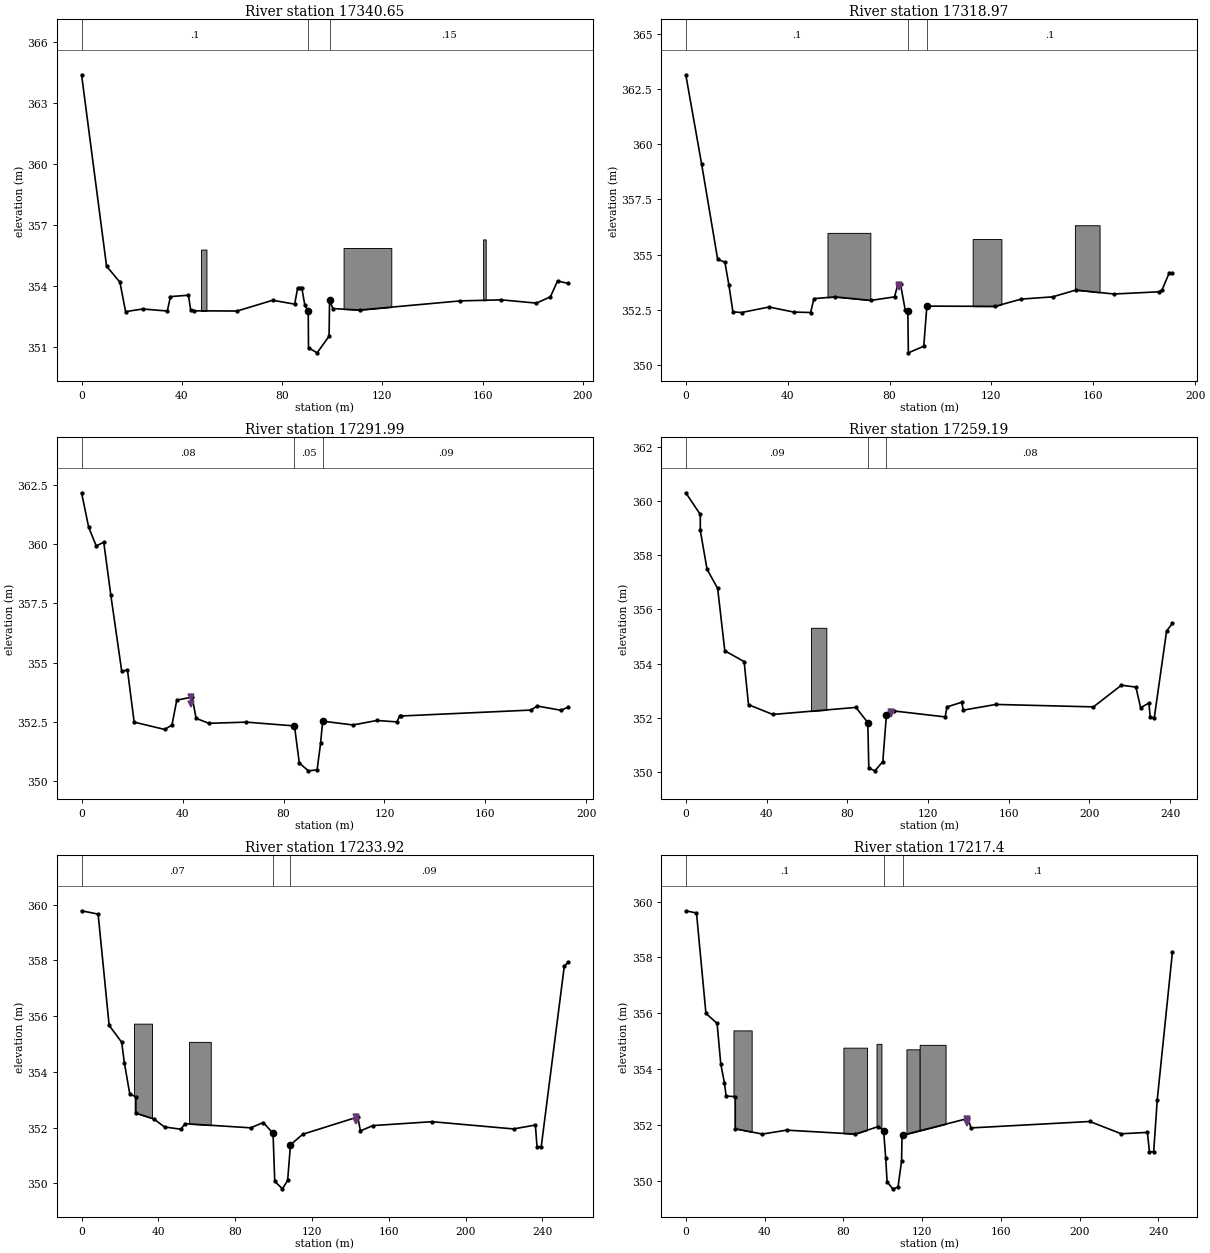
Type RM Length L Ch R = 1 ,17340.65,22.16,21.68,21.33
XS GIS Cut Line= 2
    -609858.6317   -1045358.2556    -609920.0152   -1045174.1052
#Sta/Elev= 30
       0   364.4    9.97  354.97    15.3  354.18   17.56  352.73   24.41  352.86
   34.21  352.76   35.44  353.47   42.65  353.54   43.48  352.83   44.98  352.77
   62.04  352.76   76.22  353.29      85   353.1   86.18  353.89   87.07   353.9
   87.83   353.9   89.06  353.05   90.41  352.74   90.52  350.95   93.96   350.7
   98.72  351.52   98.92  353.29  100.25  352.88  110.89  352.81  151.11  353.26
  167.41  353.31  181.44  353.15  187.01  353.46  189.85  354.24  194.11  354.12
#Mann= 3 , 0 , 0
       0      .1       0   90.41    .037       0   98.92     .15       0
#Block Obstruct= 3 ,-1
  104.51  123.54355.8673   47.65   49.81355.7874  160.17   161.2356.2895
Bank Sta=90.41,98.92
XS Rating Curve= 0 ,0
Exp/Cntr=0.3,0.1

Type RM Length L Ch R = 1 ,17318.97,27.08,26.98,26.72
XS GIS Cut Line= 2
    -609884.2434   -1045362.2772    -609936.7369   -1045178.5502
#Sta/Elev= 30
       0  363.16    6.23   359.1   12.51  354.79   15.36  354.65   16.89  353.64
   18.51   352.4   21.88  352.37   32.69  352.62    42.4  352.39   49.01  352.37
   50.32     353   58.54  353.08   72.71  352.92   81.96  353.08   83.21  353.62
   84.33  353.65   86.16  352.48   87.18  352.44   87.38  350.54   93.44  350.84
   94.66  352.66  121.45  352.65  131.72  352.98  143.99  353.08  153.18  353.39
  168.15  353.21  185.65  353.31  186.95  353.38  189.85  354.18  191.08  354.15
#Mann= 3 , 0 , 0
       0      .1       0   87.18    .045       0   94.66      .1       0
Levee=-1,83.6,353.55,0,,,,
#Block Obstruct= 3 ,-1
   55.63   72.46355.9849  112.64  123.92355.7037  152.78  162.47356.3312
Bank Sta=87.18,94.66
XS Rating Curve= 0 ,0
Exp/Cntr=0.3,0.1

Type RM Length L Ch R = 1 ,17291.99,31.82,32.8,32.37
XS GIS Cut Line= 5
    -609903.2769   -1045366.1317    -609932.4292   -1045292.1715
    -609937.7335   -1045272.8878    -609946.3473   -1045239.7977
-609960.23189999   -1045182.3602
#Sta/Elev= 30
       0  362.18     2.8  360.73    5.81  359.93    8.79  360.09   11.59  357.85
    15.9  354.64   18.19  354.68   20.83  352.48   32.95  352.17   35.81  352.36
   37.72  353.41   43.82  353.54   45.36  352.64   50.44  352.43    65.3  352.48
   84.34  352.32   86.25  350.75   89.88  350.42    93.3  350.46   94.69  351.59
   95.51  352.52  107.58  352.36  116.98  352.55  124.91  352.49  125.98  352.73
  126.71  352.74  177.97  352.99  180.53  353.16  189.99  352.98  192.78  353.12
#Mann= 3 , 0 , 0
       0     .08       0   84.34     .05       0   95.51     .09       0
Levee=-1,43.53,353.25,0,,,,
Bank Sta=84.34,95.51
XS Rating Curve= 0 ,0
Exp/Cntr=0.3,0.1

Type RM Length L Ch R = 1 ,17259.19,24.97,25.27,25.19
XS GIS Cut Line= 4
-609932.55249999   -1045375.1618    -609966.1363   -1045292.7288
-609969.44359999   -1045279.4995-610004.63879999   -1045145.5948
#Sta/Elev= 30
       0   360.3    7.18   359.5    7.19  358.91   10.53  357.48   15.79  356.77
   19.33  354.47   28.91  354.07   31.07  352.48   43.13  352.12   84.27  352.38
   90.18  351.82   90.67  350.14   93.69  350.04   97.61  350.38   99.38  352.09
     103  352.25  128.52  352.03  129.41   352.4  136.72  352.57  137.49  352.28
  153.66  352.49  201.97   352.4  215.81   353.2  222.99  353.13  225.34  352.37
  229.44  352.54  230.09  352.02  232.08  351.99   238.2   355.2   241.1  355.48
#Mann= 3 , 0 , 0
       0     .09       0   90.18     .05       0   99.38     .08       0
Levee=0,,,-1,101.76,352.14,,
#Block Obstruct= 1 ,-1
   62.01   69.63355.3181
Bank Sta=90.18,99.38
XS Rating Curve= 0 ,0
Exp/Cntr=0.3,0.1

Type RM Length L Ch R = 1 ,17233.92,15.49,16.52,17.84
XS GIS Cut Line= 4
    -609954.4877   -1045387.6656    -609990.6103    -1045297.359
-609995.24049999    -1045280.161-610031.30889999   -1045146.5473
#Sta/Elev= 30
       0  359.78    8.63  359.66   14.36  355.67    20.9  355.06   22.29  354.32
    25.1  353.21   28.11   353.1   28.12  352.52   37.62  352.31   43.21  352.02
   51.78  351.94   53.85  352.14   88.06  351.99   94.68  352.18   99.73  351.79
  100.62  350.07   104.6   349.8  107.33   350.1  108.81  351.38  115.24  351.76
  143.86  352.38  145.24  351.88  151.69  352.07  182.57  352.21  224.98  351.95
  236.36  352.09  237.22  351.31  239.41  351.31  251.42  357.79  253.47  357.94
#Mann= 3 , 0 , 0
       0     .07       0   99.73     .05       0  108.81     .09       0
Levee=0,,,-1,143.07,352.22,,
#Block Obstruct= 2 ,-1
   27.33   36.67 355.729   55.99   67.28355.0744
Bank Sta=99.73,108.81
XS Rating Curve= 0 ,0
Exp/Cntr=0.3,0.1

Type RM Length L Ch R = 1 ,17217.4 ,18.02,18.21,18.04
XS GIS Cut Line= 4
-609960.33769999   -1045387.8889    -610005.5549   -1045302.1949
-610013.21709999   -1045281.6724    -610054.8039   -1045160.1999
#Sta/Elev= 30
       0  359.67    5.44  359.59   10.23     356    15.9  355.64   17.77  354.19
   19.65   353.5    20.5  353.04   25.06  353.02   25.07  351.87   38.89  351.68
   51.19  351.82   86.09  351.68   97.87  351.95  100.48   351.8  101.54  350.83
  102.25  349.97  105.12  349.72  107.79  349.78  109.61  350.72  109.82   351.6
  110.08  351.64  143.38  352.24  144.85   351.9  205.21  352.13  221.17  351.69
  234.46  351.74  235.52  351.04  237.67  351.05  239.46   352.9  247.19   358.2
#Mann= 3 , 0 , 0
       0      .1       0  100.48     .05       0  110.08      .1       0
Levee=0,,,-1,142.9,352.08,,
#Block Obstruct= 5 ,-1
   80.06   92.08354.7722   96.89   99.38354.9088  112.08   118.8 354.712
   118.8  131.96354.8729   24.23   33.46355.3898
Bank Sta=100.48,110.08
XS Rating Curve= 0 ,0
Exp/Cntr=0.3,0.1

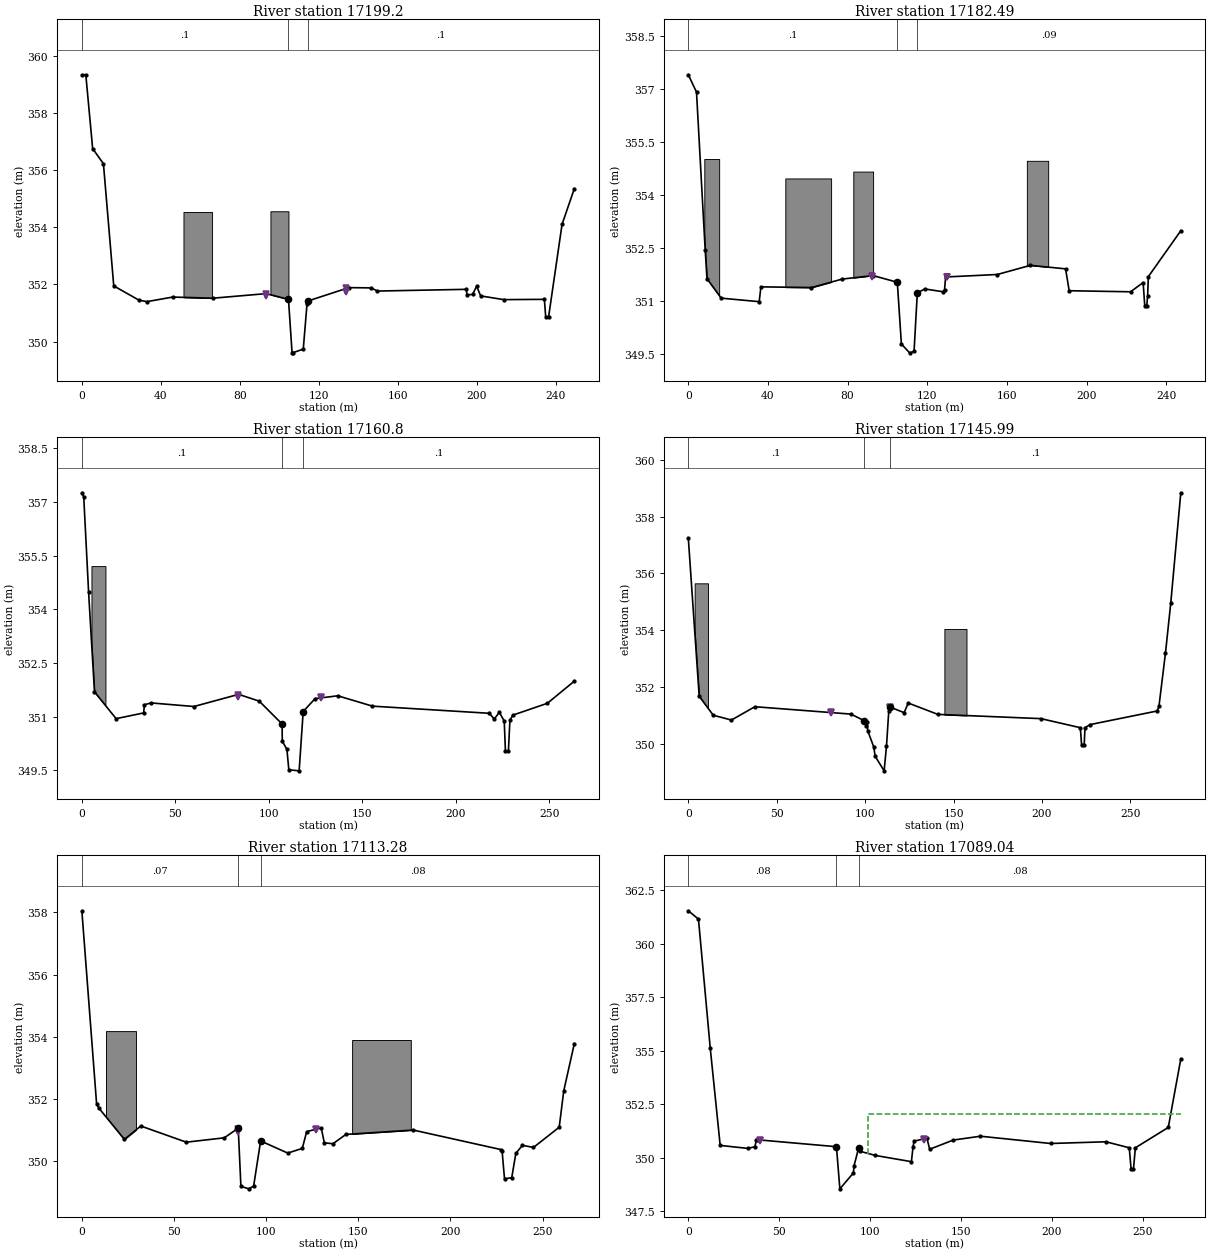
Type RM Length L Ch R = 1 ,17199.2 ,15.17,16.71,17.13
XS GIS Cut Line= 4
-609970.81529999   -1045391.2756-610024.34479999    -1045305.958
    -610027.6521   -1045292.7288-610079.25149999   -1045167.8199
#Sta/Elev= 30
       0  359.33    2.01  359.33    5.47  356.75   10.93  356.22   16.16  351.95
   28.98  351.45   32.98   351.4   46.06  351.56   66.39  351.52    93.4  351.68
  104.68  351.48  106.49  349.62  106.73  349.61  112.17  349.74  114.08  351.32
  114.43  351.42  135.27  351.89  146.56  351.88  149.72  351.77  194.77  351.83
  195.14  351.64  197.92  351.65  200.02  351.94  202.05   351.6  213.74  351.47
  234.32  351.48  235.01  350.86  236.43  350.85  243.28   354.1   249.5  355.35
#Mann= 3 , 0 , 0
       0      .1       0  104.68     .05       0  114.43      .1       0
Levee=-1,93.1,351.59,-1,133.95,351.75,,
#Block Obstruct= 2 ,-1
   51.48   65.97354.5328   95.54  104.67354.5594
Bank Sta=104.68,114.43
XS Rating Curve= 0 ,0
Exp/Cntr=0.3,0.1

Type RM Length L Ch R = 1 ,17182.49,12.56,21.69,26.56
XS GIS Cut Line= 4
-609984.94399999   -1045394.1508-610038.65459999   -1045311.8652
    -610045.5337   -1045293.3443    -610102.7465   -1045177.3449
#Sta/Elev= 30
       0  357.41    4.11  356.92    8.48  352.44    9.38  351.63   16.51  351.08
    35.6  350.98   36.46   351.4   61.86  351.38   77.25  351.62   92.75  351.72
  104.98  351.53  107.02  349.78  111.16  349.53  113.38  349.57  115.02  351.23
  118.76  351.34  128.15  351.26   128.7  351.32  129.24  351.68  155.18  351.75
  171.85  352.01  189.49  351.91   191.3  351.29  222.11  351.26  228.44  351.52
  229.27  350.86  230.26  350.86   230.7  351.14  231.06  351.69  247.36  352.99
#Mann= 3 , 0 , 0
       0      .1       0  104.98     .05       0  115.02     .09       0
Levee=-1,92.23,351.67,-1,129.91,351.68,,
#Block Obstruct= 4 ,-1
   82.86   92.82354.6667    8.03   15.49355.0234   48.72   71.72354.4726
  170.04  180.75354.9718
Bank Sta=104.98,115.02
XS Rating Curve= 0 ,0
Exp/Cntr=0.3,0.1

Type RM Length L Ch R = 1 ,17160.8 ,13.11,14.81,16.5
XS GIS Cut Line= 4
-609989.97109999   -1045394.1508    -610050.5608   -1045318.7444
-610069.46269999   -1045302.6894-610150.05409999   -1045185.9174
#Sta/Elev= 30
       0  357.26       1  357.15    3.62  354.47    6.75  351.69   18.33  350.94
   33.03   351.1    33.5  351.33   37.06  351.38   59.95  351.28   83.86  351.62
   94.89  351.43  107.11  350.79  107.21  350.31  109.69  350.08  110.71  349.51
  116.23  349.48  118.39  351.14  124.73   351.5  136.87  351.58  155.45  351.29
  217.95  351.09   220.6  350.93  223.32  351.12  225.93  350.87  226.57  350.03
  228.16  350.03  228.97   350.9  230.61  351.04  249.01  351.37  263.42  351.99
#Mann= 3 , 0 , 0
       0      .1       0  107.11     .05       0  118.39      .1       0
Levee=-1,83.49,351.54,-1,128.18,351.54,,
#Block Obstruct= 1 ,-1
    5.14   12.62355.2086
Bank Sta=107.11,118.39
XS Rating Curve= 0 ,0
Exp/Cntr=0.3,0.1

Type RM Length L Ch R = 1 ,17145.99,27.89,32.71,30.59
XS GIS Cut Line= 4
-609997.46979999   -1045397.9022-610062.86769999   -1045325.5206
    -610080.0049   -1045315.2094    -610182.7567   -1045191.3149
#Sta/Elev= 30
       0  357.24    6.15  351.67    14.1     351   24.39  350.83   37.64   351.3
   91.97  351.04   99.35  350.81  100.63  350.62   101.3  350.75  101.43  350.46
  104.81  349.89  105.71  349.55  110.73  349.04  112.06   349.9  113.36  351.14
  113.98  351.29  122.05  351.09  124.36  351.43  141.11  351.03  199.41  350.88
  221.71  350.56  222.39  349.96  223.87  349.96  224.34  350.56  227.21  350.67
  265.19  351.15  266.17  351.32  269.86   353.2  272.83  354.95  278.51  358.84
#Mann= 3 , 0 , 0
       0      .1       0   99.35     .05       0  113.98      .1       0
Levee=-1,80.54,351.1,-1,114.15,351.27,,
#Block Obstruct= 2 ,-1
    3.59   11.11355.6489  144.81  157.32 354.041
Bank Sta=99.35,113.98
XS Rating Curve= 0 ,0
Exp/Cntr=0.3,0.1

Type RM Length L Ch R = 1 ,17113.28,26.52,24.24,18.86
XS GIS Cut Line= 4
    -610014.2555   -1045411.1812    -610073.9543   -1045354.2445
-610088.49159999   -1045348.1167-610203.07669999   -1045224.0175
#Sta/Elev= 30
       0  358.05    7.99  351.85    9.17  351.71   23.07   350.7   31.98  351.13
   56.66  350.61   77.25  350.75   84.84  351.06   86.29  349.19    90.6  349.11
    93.2   349.2   96.99  350.65  111.69  350.26   119.6  350.41  121.97  350.95
  129.87  351.07  131.55  350.59  136.23  350.56  143.26  350.86  179.81     351
  227.56  350.37     228  350.32  229.31  349.43  233.23  349.47  235.45  350.25
  239.03  350.51  244.99  350.44  258.97  351.09  261.44  352.26  267.18  353.78
#Mann= 3 , 0 , 0
       0     .07       0   84.84     .05       0   96.99     .08       0
Levee=-1,84.53,350.93,-1,126.79,350.99,,
#Block Obstruct= 2 ,-1
   13.08   29.37354.1812  146.62  178.47353.8946
Bank Sta=84.84,96.99
XS Rating Curve= 0 ,0
Exp/Cntr=0.3,0.1

Type RM Length L Ch R = 1 ,17089.04,18.56,16.58,14.88
XS GIS Cut Line= 5
    -610034.9281   -1045435.6041    -610087.8449   -1045376.0727
    -610096.0157    -1045368.502-610100.21099999   -1045364.6088
-610208.84299999   -1045228.1631
#Sta/Elev= 30
       0  361.54    5.58  361.15   12.05  355.13   17.53  350.57   32.83  350.43
    36.6  350.51   37.39   350.8   38.56  350.83   81.49  350.51   83.36  348.54
   90.79  349.28   91.18  349.62   93.66  350.44   94.72  350.29  102.97   350.1
  122.72  349.81  123.62   350.5  124.19  350.77  131.28  350.91  132.76  350.39
  145.72  350.82   160.7     351  199.28  350.66  229.75  350.74  242.57  350.46
  243.59  349.45  244.87  349.45  245.93  350.46  264.03  351.41  270.92  354.61
#Mann= 3 , 0 , 0
       0     .08       0   81.49     .05       0   93.66     .08       0
Levee=-1,39.49,350.76,-1,129.56,350.81,,
#XS Ineff= 2 , 0
                           99.08          352.04
Permanent Ineff=
       F       F
Bank Sta=81.49,93.66
XS Rating Curve= 0 ,0
Exp/Cntr=0.3,0.1

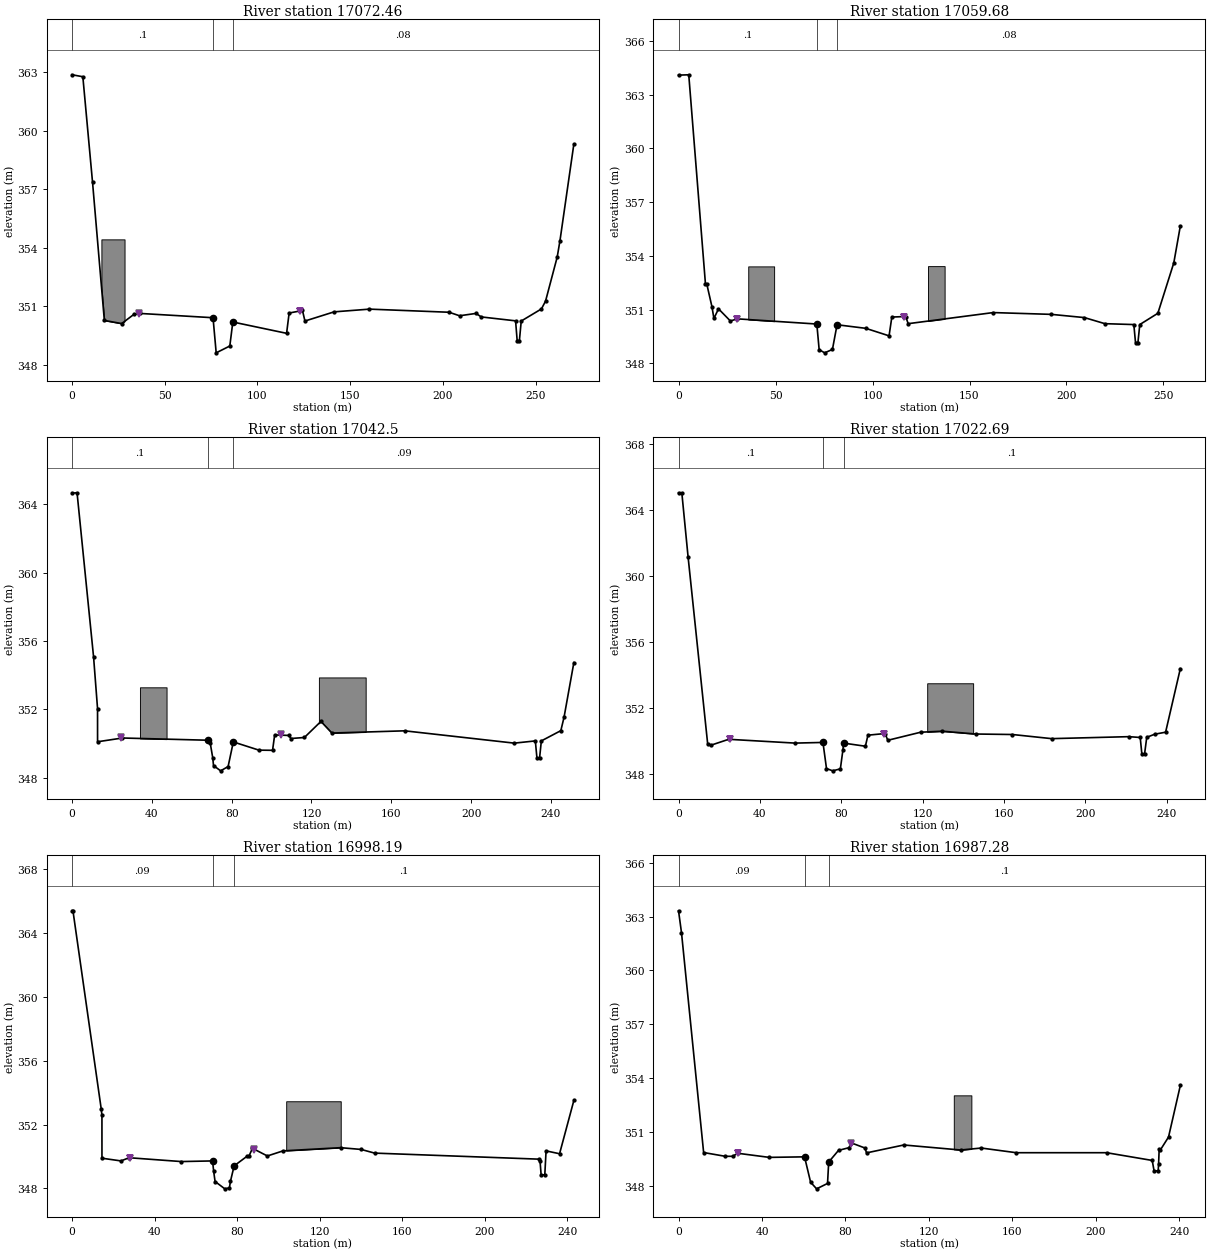
Type RM Length L Ch R = 1 ,17072.46,16.25,12.79,10.07
XS GIS Cut Line= 3
    -610056.4079   -1045446.8883    -610113.0288   -1045371.7464
-610223.62489999   -1045234.1628
#Sta/Elev= 30
       0  362.86    5.81  362.76   11.04  357.35   17.41  350.27   26.76  350.11
   33.33  350.58   36.49  350.63   76.02  350.41   77.72  348.61   85.07  348.96
   86.69  350.19  115.69  349.61  117.06  350.65  124.26  350.78  125.58  350.24
  141.31  350.71  160.37  350.85  203.33  350.69  208.96  350.51  217.84  350.63
  220.67  350.45  239.18  350.25  240.04  349.23  241.23  349.23  242.23  350.24
  253.12  350.86  255.34  351.26  261.63  353.52  263.12  354.36  270.61  359.31
#Mann= 3 , 0 , 0
       0      .1       0   76.02     .05       0   86.69     .08       0
Levee=-1,35.85,350.64,-1,122.98,350.74,,
#Block Obstruct= 1 ,-1
   15.82    28.3354.4257
Bank Sta=76.02,86.69
XS Rating Curve= 0 ,0
Exp/Cntr=0.3,0.1

Type RM Length L Ch R = 1 ,17059.68,16.46,17.17,17.44
XS GIS Cut Line= 4
    -610078.7967   -1045455.5811    -610112.3988   -1045397.9019
-610118.97659999   -1045380.2243-610226.18369999   -1045244.3693
#Sta/Elev= 30
       0   364.1    5.27  364.12   13.87  352.44   14.53  352.44   17.24  351.15
   18.24   350.5    20.6  351.04   26.73  350.36   30.28  350.48   71.29  350.19
   72.49  348.76   75.31  348.58   79.34  348.77   81.72  350.15   96.52  349.95
  108.53  349.53  109.96  350.58  117.11  350.61  118.38  350.21  162.22  350.83
  192.19  350.73  209.23  350.55   219.8  350.21  234.71  350.16  235.58  349.15
  236.82  349.15  237.78  350.16  247.09  350.79  255.32  353.61  258.68  355.67
#Mann= 3 , 0 , 0
       0      .1       0   71.29     .05       0   81.72     .08       0
Levee=-1,30.14,350.48,-1,116.4,350.57,,
#Block Obstruct= 2 ,-1
   35.93   49.28353.4114   128.6  137.17353.4269
Bank Sta=71.29,81.72
XS Rating Curve= 0 ,0
Exp/Cntr=0.3,0.1

Type RM Length L Ch R = 1 ,17042.5 ,17.28,19.81,21.31
XS GIS Cut Line= 3
    -610096.5238   -1045462.7249-610137.26969999   -1045384.9372
     -610236.767   -1045254.9526
#Sta/Elev= 30
       0  364.65     2.5  364.67   10.78  355.07   12.77  352.05   12.78  350.11
   25.22  350.33   68.07   350.2   69.25  350.03   70.53  349.16   70.89  348.72
   74.46  348.41   78.21  348.66   80.82   350.1   93.67  349.62  100.49  349.61
  101.55  350.51  108.74  350.48  109.63   350.3  116.44  350.36  124.74   351.3
  130.23  350.62  166.72  350.75  221.64  350.03   232.2  350.16  233.01  349.15
  234.32  349.15  235.21  350.16  244.98  350.76   246.6  351.55  251.51  354.74
#Mann= 3 , 0 , 0
       0      .1       0   68.07     .05       0   80.82     .09       0
Levee=-1,24.6,350.36,-1,104.97,350.57,,
#Block Obstruct= 2 ,-1
   34.02   47.36353.2942  123.72  147.16 353.872
Bank Sta=68.07,80.82
XS Rating Curve= 0 ,0
Exp/Cntr=0.3,0.1

Type RM Length L Ch R = 1 ,17022.69,20.34,24.51,26.46
XS GIS Cut Line= 4
    -610109.2238   -1045469.0749    -610141.5031   -1045415.0998
-610153.34319999   -1045398.6212    -610254.5471   -1045270.1927
#Sta/Elev= 30
       0  365.06    1.64  365.03     4.7  361.17   14.35  349.82   16.11  349.78
   24.66  350.13   57.31   349.9      71  349.94   72.74  348.36   75.78  348.22
   79.56  348.34   80.83   349.5   81.14   349.9   91.86  349.71   93.12  350.38
  101.55  350.48  102.88  350.07  119.07  350.56  129.71  350.62  146.22  350.45
  164.16  350.42  183.42  350.17   221.4  350.29  226.97  350.24  227.78  349.24
  229.12  349.25  230.18  350.25  234.14  350.44  239.45  350.56  246.69  354.41
#Mann= 3 , 0 , 0
       0      .1       0      71     .05       0   81.14      .1       0
Levee=-1,25.12,350.12,-1,100.89,350.46,,
#Block Obstruct= 1 ,-1
  122.25  144.83353.5231
Bank Sta=71,81.14
XS Rating Curve= 0 ,0
Exp/Cntr=0.3,0.1

Type RM Length L Ch R = 1 ,16998.19,9.12,10.9,11.96
XS GIS Cut Line= 4
    -610120.0189   -1045473.0437    -610164.7152   -1045421.6799
-610176.32229999   -1045412.7185    -610262.3082    -1045277.213
#Sta/Elev= 30
       0   365.4     .44  365.39   14.12  352.99   14.48  352.58   14.49  349.89
   23.72  349.72   27.63  349.92   52.97  349.68   68.09  349.72   68.65  349.06
   69.32  348.43   74.05  347.97   76.26  348.03   76.79  348.45   78.56  349.41
   84.79  350.01   85.77  350.03   87.46  350.51   94.67  350.03  102.27  350.35
  130.13  350.55  140.13  350.44  146.64  350.21  226.48  349.83  226.84  349.73
  227.37  348.85  229.15  348.85  229.77  350.35  236.31  350.17  243.24  353.51
#Mann= 3 , 0 , 0
       0     .09       0   68.09     .05       0   78.56      .1       0
Levee=-1,28.15,349.89,-1,88.19,350.4,,
#Block Obstruct= 1 ,-1
   103.8  130.23  353.46
Bank Sta=68.09,78.56
XS Rating Curve= 0 ,0
Exp/Cntr=0.3,0.1

Type RM Length L Ch R = 1 ,16987.28,5.21,6.05,5.46
XS GIS Cut Line= 4
    -610128.4855    -1045474.102    -610169.6448   -1045430.5961
     -610182.884   -1045422.4552    -610272.3271   -1045283.7394
#Sta/Elev= 30
       0  363.32    1.42   362.1   12.03  349.87   22.39  349.66   25.97  349.66
    28.3  349.83   43.49   349.6   60.39  349.63   63.29  348.22   66.17  347.85
   71.41  348.15   71.96  349.34   76.67  349.99   81.71  350.14    82.7  350.41
   89.37  350.12   90.09  349.85  107.96  350.29  135.21  350.01   145.1  350.12
  161.87  349.86  205.15  349.86  227.01  349.43   227.9  348.85  229.87  348.85
  230.06  349.22  230.34  350.05  230.95  350.02  234.82  350.73  240.48   353.6
#Mann= 3 , 0 , 0
       0     .09       0   60.39     .05       0   71.96      .1       0
Levee=-1,28.29,349.84,-1,82.85,350.32,,
#Block Obstruct= 1 ,-1
  131.91  140.34 353.052
Bank Sta=60.39,71.96
XS Rating Curve= 0 ,0
Exp/Cntr=0.3,0.1

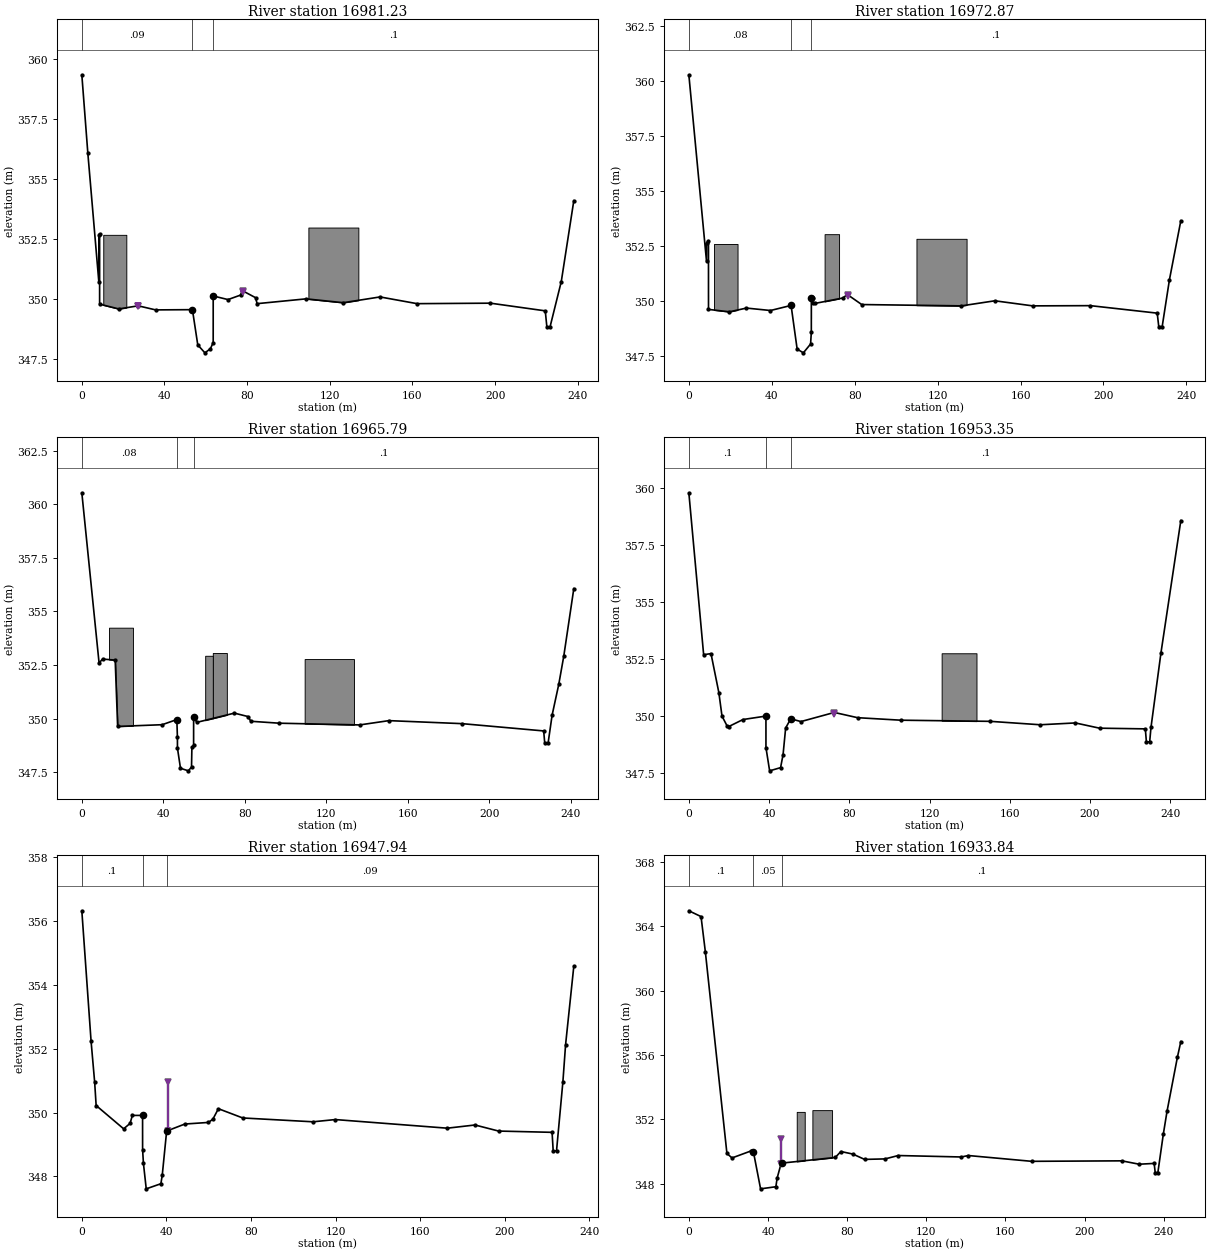
Type RM Length L Ch R = 1 ,16981.23,7.15,8.37,7.3
XS GIS Cut Line= 5
    -610135.9278   -1045473.8311-610172.04879999   -1045435.4654
    -610183.2412   -1045429.7737-610209.17089999   -1045395.1544
    -610278.8182   -1045285.8913
#Sta/Elev= 30
       0  359.36    2.91  356.09    8.22  350.74    8.34  352.68     8.6  352.72
    8.61   349.8   17.89   349.6   27.28  349.73   35.71  349.56   53.52  349.57
   56.11   348.1   59.56  347.77   62.22  347.94   63.57   348.2   63.58  350.14
   70.75  349.99   76.88  350.18   77.52  350.37   84.05  350.07   84.83  349.82
   108.5  350.02  126.53  349.86  144.31   350.1  162.23  349.82  197.73  349.84
  224.27  349.52  225.05  348.85  226.58  348.85  232.02  350.74  238.08  354.11
#Mann= 3 , 0 , 0
       0     .09       0   53.52    .045       0   63.58      .1       0
Levee=-1,27.14,349.71,-1,78.09,350.31,,
#Block Obstruct= 2 ,-1
   10.37   21.53352.6887  109.64  133.82352.9926
Bank Sta=53.52,63.58
XS Rating Curve= 0 ,0
Exp/Cntr=0.3,0.1

Type RM Length L Ch R = 1 ,16972.87,6.4,7.07,5.77
XS GIS Cut Line= 4
-610141.14319999    -1045476.769-610175.05779999   -1045443.1728
    -610187.6253   -1045437.0179    -610283.7571   -1045290.0894
#Sta/Elev= 30
       0  360.27    8.52  351.82    8.57  352.63    9.47  352.75    9.48  349.63
   19.56  349.52   27.77  349.69   39.38  349.58   49.32  349.81   52.24  347.83
   55.24  347.66   58.72  348.06   59.08  348.59   59.09  350.16    59.6  350.18
   59.65  350.16   59.72  349.93   60.78   349.9   74.43  350.15   76.38  350.31
   83.39  349.85  131.46  349.79   147.6  350.02  165.87  349.79  193.69   349.8
  225.93  349.46  226.67  348.85  228.32  348.85  231.83  350.98  237.31  353.65
#Mann= 3 , 0 , 0
       0     .08       0   49.32    .045       0   59.09      .1       0
Levee=0,,,-1,76.79,350.25,,
#Block Obstruct= 3 ,-1
   65.48   72.46353.0419  109.79  133.97352.8312   12.12   23.49 352.596
Bank Sta=49.32,59.09
XS Rating Curve= 0 ,0
Exp/Cntr=0.3,0.1

Type RM Length L Ch R = 1 ,16965.79,5.78,7.61,9.9
XS GIS Cut Line= 4
-610145.59389999   -1045478.8123-610178.31639999   -1045449.6994
-610190.07889999   -1045443.5069    -610290.9538   -1045289.2427
#Sta/Elev= 30
       0  360.53    8.46   352.6   10.21  352.78   16.37  352.73   17.57  349.64
    39.4  349.72   46.62  349.96   46.91  349.13   46.92  348.63   48.41  347.69
   52.27  347.57   53.83  347.75   54.01  348.66   54.85  348.77   54.86  350.09
   56.45  349.83   74.85  350.26   81.55   350.1   82.92  349.88   96.96  349.79
  136.34  349.71  150.68  349.91  186.51  349.77  226.63  349.43  227.16  348.85
  228.78  348.85  230.78  350.17  234.03   351.6   236.5  352.92  241.41  356.06
#Mann= 3 , 0 , 0
       0     .08       0   46.62     .04       0   54.86      .1       0
#Block Obstruct= 4 ,-1
   64.27   71.16353.0629   60.53   64.27352.9328  109.34  133.53352.7794
   13.35   25.08354.2424
Bank Sta=46.62,54.86
XS Rating Curve= 0 ,0
Exp/Cntr=0.3,0.1

Type RM Length L Ch R = 1 ,16953.35,6.05,5.41,5.58
XS GIS Cut Line= 6
    -610155.8555   -1045482.9451    -610161.7397   -1045476.4255
    -610181.9567   -1045461.5702    -610199.8667    -1045452.669
    -610213.6235   -1045434.9184-610300.69799999    -1045290.095
#Sta/Elev= 30
       0  359.77    7.38  352.67   11.04  352.72   14.96  351.01   16.53  349.98
      19  349.56   19.86  349.52   27.02  349.83   38.39  349.98   38.44  349.97
   38.45   348.6   40.28  347.58   45.74  347.72   46.98  348.29   48.27  349.46
   50.81  349.86    55.9  349.74   72.53  350.14   84.15  349.91   105.7   349.8
  150.23  349.75  175.23   349.6  192.72  349.68  204.79  349.45  227.61  349.42
  228.15  348.85  229.78  348.85  230.43  349.48  235.42  352.76  245.31  358.55
#Mann= 3 , 0 , 0
       0      .1       0   38.39    .035       0   50.81      .1       0
Levee=0,,,-1,72.32,350.06,,
#Block Obstruct= 1 ,-1
  126.05  143.43352.7345
Bank Sta=38.39,50.81
XS Rating Curve= 0 ,0
Exp/Cntr=0.5,0.3

Type RM Length L Ch R = 1 ,16947.94,14.61,14.1,13.66
XS GIS Cut Line= 6
    -610169.5517   -1045485.6161-610173.24989999    -1045477.427
    -610183.6554   -1045466.7471-610201.92269999   -1045457.7056
    -610218.8174   -1045438.1758    -610302.8072   -1045298.9794
#Sta/Elev= 30
       0  356.32    4.38  352.23    6.07  350.95    6.77  350.22   19.78  349.49
   22.82  349.66    23.9  349.91   28.73  349.91   28.74  348.84   29.13  348.41
   30.46  347.61   37.39  347.77   38.04  348.04   40.11  349.42   48.72  349.64
   59.87  349.69   61.96  349.79   64.59  350.12   76.11  349.83  109.33  349.71
  119.86  349.78  172.83  349.51  185.94  349.61  197.09  349.42   222.4  349.38
  222.92   348.8   224.5   348.8  227.52  350.97  228.79  352.13  232.67  354.58
#Mann= 3 , 0 , 0
       0      .1       0   28.73    .045       0   40.11     .09       0
Levee=0,,,-1,40.75,350.9502,,	2158
Bank Sta=28.73,40.11
XS Rating Curve= 0 ,0
Exp/Cntr=0.3,0.1

Type RM Length L Ch R = 1 ,16933.84,27.14,24.89,15.43
XS GIS Cut Line= 6
    -610172.8312   -1045503.2958    -610183.6262   -1045487.4208
    -610192.1378   -1045478.4949    -610208.3665   -1045469.9668
    -610228.7441   -1045448.1827    -610312.5439   -1045301.5194
#Sta/Elev= 30
       0  364.96    6.16   364.6    8.34  362.41   19.24  349.88   21.81   349.6
   31.53  350.04   32.63  349.98   36.25  347.68   43.98  347.81    44.6  348.34
    46.6  349.24   47.05  349.28      74  349.63   76.83     350   82.89  349.84
    88.8  349.51   99.14  349.54  105.83  349.75  137.71  349.66  141.24  349.75
  173.25  349.39  218.78  349.42  227.56  349.21  235.14  349.26  235.67  348.69
  237.01  348.69  239.77  351.08  241.66  352.51   246.9  355.87  248.61  356.83
#Mann= 3 , 0 , 0
       0      .1       0   32.63     .05       0   47.05      .1       0
Levee=0,,,-1,46.74,350.7523,,	2158
#Block Obstruct= 2 ,-1
   54.52   58.56352.4616   62.43   72.37352.5712
Bank Sta=32.63,47.05
XS Rating Curve= 0 ,0
Exp/Cntr=0.3,0.1

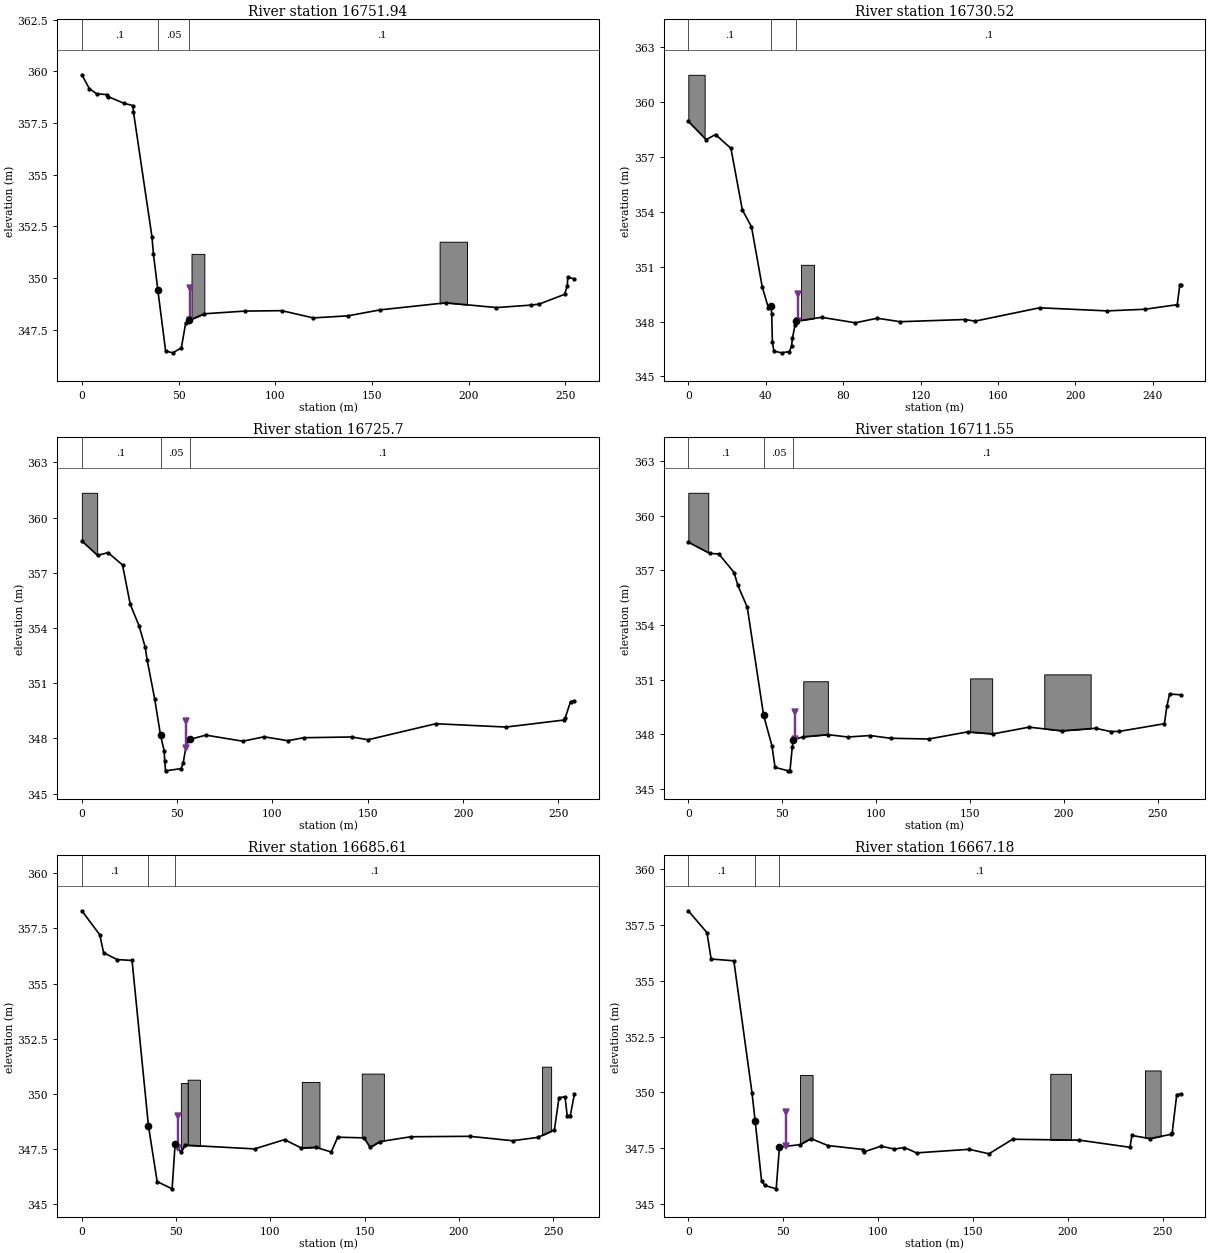
Type RM Length L Ch R = 1 ,16751.94,21.77,21.42,20.49
XS GIS Cut Line= 3
-610331.99179999   -1045606.3583     -610368.002   -1045538.7669
    -610450.4891    -1045381.048
#Sta/Elev= 30
       0  359.83    3.86  359.16    7.68  358.91    13.1  358.87   13.71  358.77
   21.76  358.45   26.44  358.34   26.69  358.03   36.22     352   37.03  351.14
    39.3   349.4    43.3  346.47   46.95  346.38   51.43  346.62   53.67  347.82
   55.59  347.96   63.34  348.27    84.5   348.4  103.36  348.42  119.61  348.07
  137.55  348.17  154.31  348.46  188.11   348.8   214.3  348.57  232.32  348.69
   236.5  348.74  249.53  349.21  250.98  349.63  251.15  350.05  254.57  349.95
#Mann= 3 , 0 , 0
       0      .1       0    39.3     .05       0   55.59      .1       0
Levee=0,,,-1,56,349.5115,,	2158
#Block Obstruct= 2 ,-1
  184.93  199.08351.7553   56.68   63.33351.1675
Bank Sta=39.3,55.59
XS Rating Curve= 0 ,0
Exp/Cntr=0.3,0.1

Type RM Length L Ch R = 1 ,16730.52,4.86,4.82,4.85
XS GIS Cut Line= 3
    -610352.6812   -1045617.9347-610388.15709999   -1045543.0952
    -610465.3939   -1045389.8634
#Sta/Elev= 30
       0  358.93    9.19  357.93   14.08  358.21   22.01  357.45   27.93  354.09
   32.64  353.17   38.18  349.89   41.39  348.74   42.75  348.86   43.07   348.4
   43.43   346.9   44.17  346.39   48.14  346.29   52.25  346.36   53.34  346.67
   53.78  347.08   55.17  347.83   55.83  348.02   68.85  348.23    86.3  347.93
   97.54  348.18  109.47  347.99  142.98  348.11   148.1  348.02  181.48  348.75
  216.45  348.58  235.97  348.67  252.59  348.92  253.94  350.02  254.42  350.01
#Mann= 3 , 0 , 0
       0      .1       0   42.75     .05       0   55.83      .1       0
Levee=0,,,-1,56.44,349.5195,,	2158
#Block Obstruct= 2 ,-1
       0    8.43361.4715   58.22   64.91351.0959
Bank Sta=42.75,55.83
XS Rating Curve= 0 ,0
Exp/Cntr=0.5,0.3

Type RM Length L Ch R = 1 ,16725.7 ,12.99,14.15,15.54
XS GIS Cut Line= 3
-610357.07759999   -1045619.9076    -610392.5535   -1045545.0681
    -610471.4441   -1045388.2447
#Sta/Elev= 30
       0  358.73    8.25  357.95   13.74   358.1   21.33  357.43   25.38  355.29
   29.98  354.13   33.21  352.97   34.21  352.29   38.23  350.14   41.28  348.17
   43.17  347.33   43.48  346.77    43.9  346.24   52.08  346.36   53.19  346.68
   55.07  347.84   56.99  347.96   65.11  348.18   84.43  347.85   95.58  348.09
  108.04  347.88  116.51  348.04   141.6  348.08  150.14  347.93  185.69   348.8
  222.57  348.62  252.83     349  253.56  349.11  256.38     350  258.37  350.05
#Mann= 3 , 0 , 0
       0      .1       0   41.28     .05       0   56.99      .1       0
Levee=0,,,-1,54.48,348.9688,,	2161
#Block Obstruct= 1 ,-1
       0    8.03361.3521
Bank Sta=41.28,56.99
XS Rating Curve= 0 ,0
Exp/Cntr=0.5,0.3

Type RM Length L Ch R = 1 ,16711.55,25.25,25.95,28.78
XS GIS Cut Line= 6
-610364.63259999   -1045627.0364    -610377.2875   -1045602.5042
-610393.99859999   -1045577.0942    -610395.3159   -1045574.2261
    -610401.3596   -1045562.6079    -610487.1075   -1045395.4414
#Sta/Elev= 30
       0  358.55   11.42  357.93   16.23   357.9   24.38  356.88   26.34  356.18
   31.38  354.97   40.08  349.03   44.53  347.35   46.16  346.17   53.25  345.98
   54.11  345.99   55.32  347.27   55.84  347.68   61.13  347.85   74.22  347.97
   84.94  347.84   96.79  347.92  107.67  347.77  127.94  347.73  148.62  348.12
  162.19  348.01  181.37  348.38  198.87  348.18  216.75  348.32  224.73  348.14
  229.48  348.15   253.4  348.57  254.72  349.52  256.17   350.2  262.14  350.16
#Mann= 3 , 0 , 0
       0      .1       0   40.08     .05       0   55.84      .1       0
Levee=0,,,-1,57.02,349.237,,	2161
#Block Obstruct= 4 ,-1
   61.17   74.27350.9031  150.01  161.74351.0612  189.46  214.16351.2825
       0    10.6361.2628
Bank Sta=40.08,55.84
XS Rating Curve= 0 ,0
Exp/Cntr=0.3,0.1

Type RM Length L Ch R = 1 ,16685.61,17.06,18.42,16.35
XS GIS Cut Line= 3
-610382.98559999   -1045633.4457-610424.52349999    -1045581.395
-610511.87249999   -1045407.5064
#Sta/Elev= 30
       0   358.3    9.52  357.21   11.52   356.4    18.7  356.09   26.62  356.05
   35.31  348.56   39.94  346.03   47.87   345.7   49.47  347.74   52.52  347.37
   54.79  347.68   91.59  347.51  107.49  347.93   116.4  347.55  124.24  347.58
  132.27  347.37  135.69  348.04  149.62  348.01  152.87  347.58   158.1  347.84
  174.46  348.06  205.73  348.08  228.44  347.88  241.77  348.03  250.63  348.37
  253.06  349.83  256.27  349.87   257.4  349.02  259.08  349.02  261.19  349.98
#Mann= 3 , 0 , 0
       0      .1       0   35.31     .05       0   49.47      .1       0
Levee=0,,,-1,50.97,348.9799,,	2161
#Block Obstruct= 5 ,-1
    56.1   62.64350.6454   52.52    56.1350.4926  148.46  160.19350.9218
  116.67  126.02350.5445  244.02  248.89351.2354
Bank Sta=35.31,49.47
XS Rating Curve= 0 ,0
Exp/Cntr=0.3,0.1

Type RM Length L Ch R = 1 ,16667.18,6.2,5.78,6.81
XS GIS Cut Line= 4
    -610393.8158    -1045643.949-610416.82609999   -1045617.2862
    -610427.9386   -1045608.2904-610522.61459999   -1045420.9473
#Sta/Elev= 30
       0  358.13    9.83  357.15   12.01  355.97   23.98  355.89   33.56  349.97
   35.22   348.7   38.62  346.02   40.35  345.83   46.29  345.68      48  347.55
   58.83  347.66   64.61  347.93   73.46  347.62   92.26  347.44   92.35  347.33
  101.51  347.59  108.59  347.46  113.83  347.53   120.2  347.29  147.91  347.45
  158.38  347.25   170.8   347.9  205.99  347.86  232.66  347.54  233.67  348.07
  243.08  347.93  254.22  348.12  254.91   348.2  257.28   349.9  259.42  349.93
#Mann= 3 , 0 , 0
       0      .1       0   35.22     .05       0      48      .1       0
Levee=0,,,-1,51.6,349.0984,,	2161
#Block Obstruct= 3 ,-1
   58.83   65.46350.7798  190.67  201.55350.8297  240.54   248.8 350.981
Bank Sta=35.22,48
XS Rating Curve= 0 ,0
Exp/Cntr=0.3,0.1