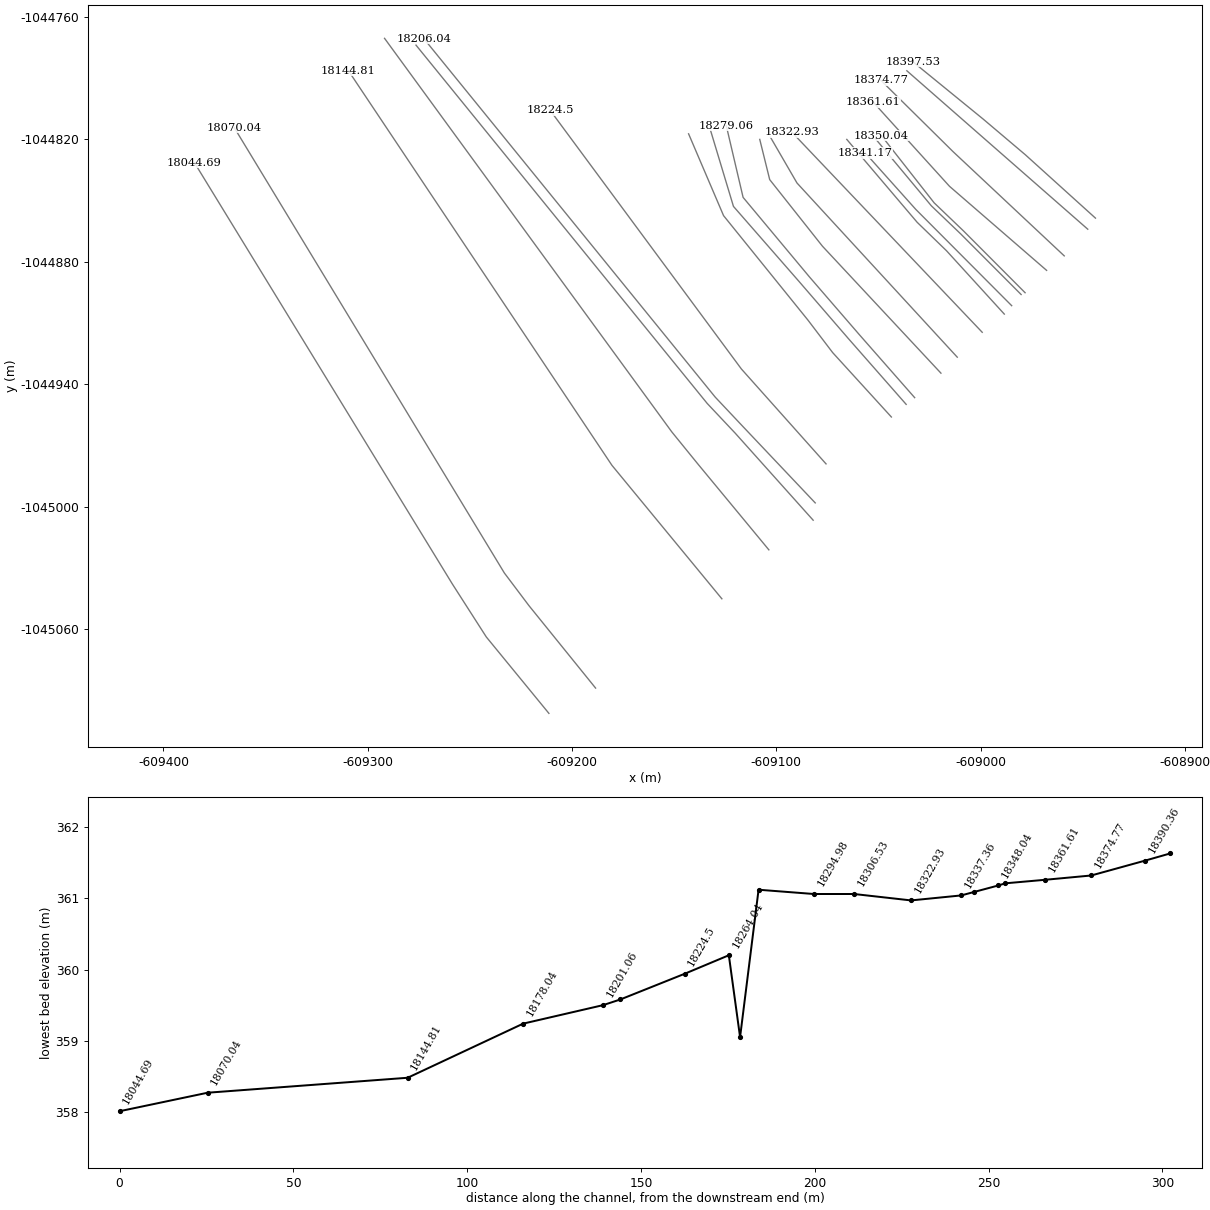
HEC-RAS study PPO_Kvasiny_efektiv.prj: PPO_Kvasiny_efektivita

--- PPO_Kvasiny_efektiv.g04 (geometry) --- (continued)

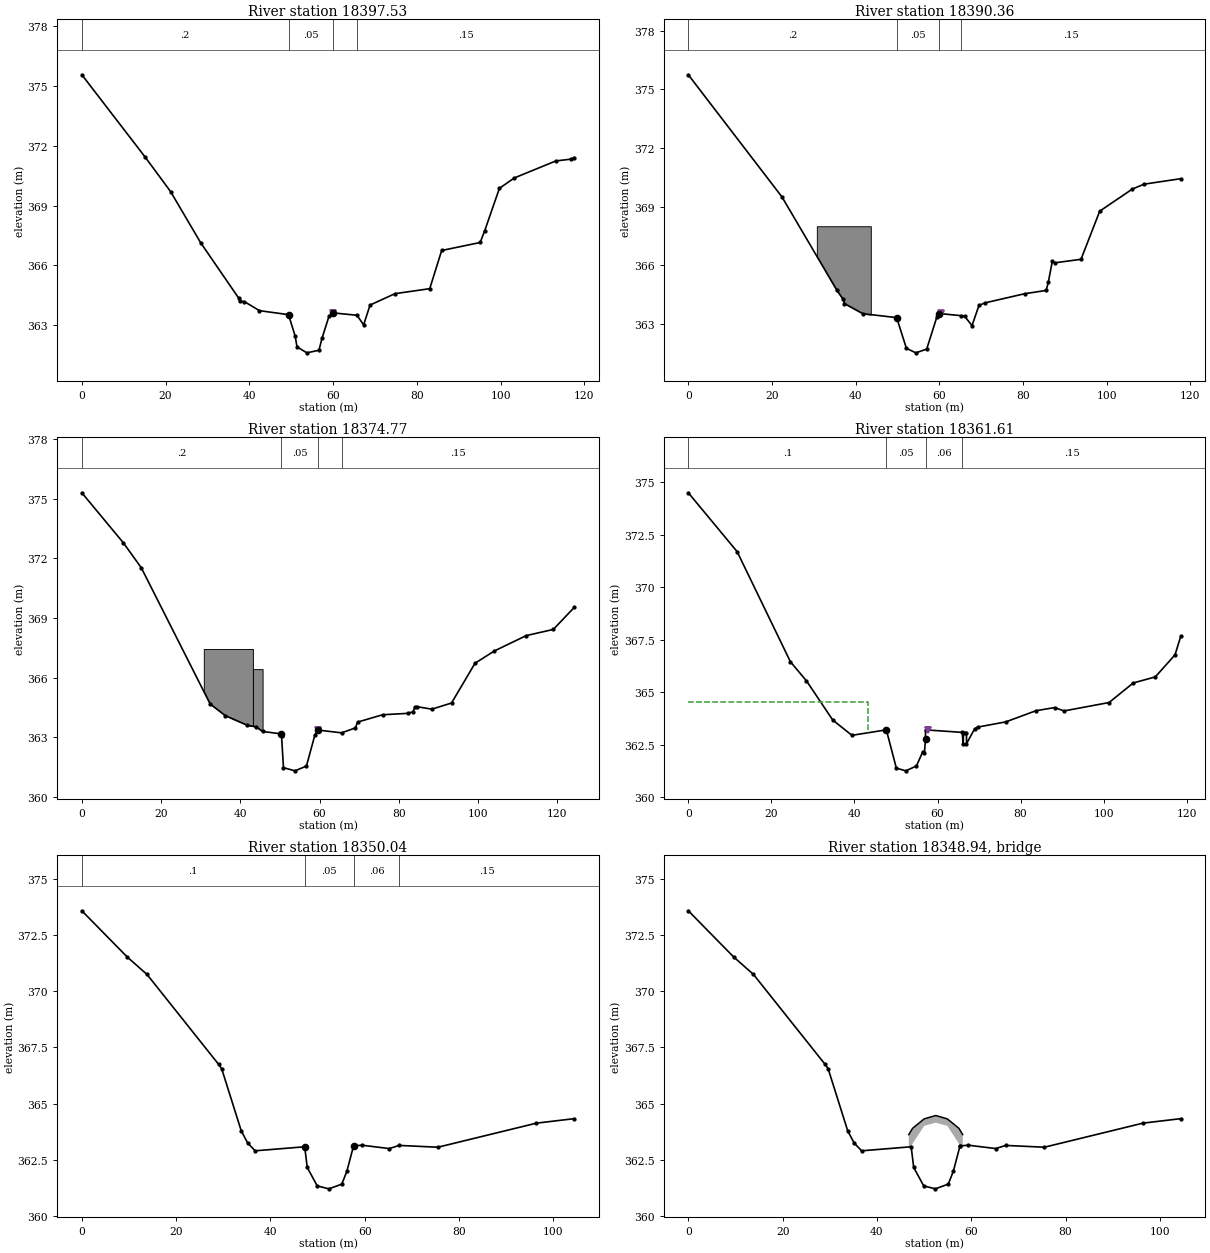
Type RM Length L Ch R = 1 ,18397.53,7.24,7.17,6.9
XS GIS Cut Line= 4
-608943.77299999   -1044858.6939-608978.04789999   -1044827.7227
    -608998.6854   -1044810.2602    -609033.0813   -1044782.2143
#Sta/Elev= 29
       0  375.54   15.13  371.42   21.18   369.7   28.37  367.14   37.48  364.36
   37.74   364.2   38.84  364.19   42.41  363.74   49.36  363.54   50.95  362.46
   51.38  361.93   53.74  361.63   56.63  361.76   57.34  362.35   59.02  363.46
   59.91  363.63    65.7  363.51    67.3  363.03   68.82  364.02   74.78  364.59
   83.08  364.84   85.93  366.75   95.12  367.15   96.23  367.75   99.72  369.86
  103.29  370.38   113.2  371.23  116.84  371.32  117.61   371.4
#Mann= 4 ,-1 , 0
       0      .2       0   49.36     .05       0   59.91     .05       0
    65.7     .15       0
Levee=0,,,-1,59.93,363.63,,
Bank Sta=49.36,59.91
XS Rating Curve= 0 ,0
Exp/Cntr=0.3,0.1

Type RM Length L Ch R = 1 ,18390.36,15.99,15.59,15.07
XS GIS Cut Line= 2
    -608947.5425   -1044864.1187-609036.10399999   -1044786.5639
#Sta/Elev= 27
       0  375.74   22.38   369.5    35.5  364.73   36.92  364.29   37.32  364.05
   41.73  363.53    49.8  363.33   52.13  361.76   54.39  361.53   56.98  361.72
   59.42  363.37   59.95  363.54   65.19  363.43   66.02  363.41   67.81  362.92
   69.47  363.95   70.84  364.08   80.38  364.55   85.55  364.72   86.08  365.17
      87   366.2   87.62  366.13   93.87  366.31   98.34  368.77  106.14   369.9
  108.95  370.15  117.72  370.43
#Mann= 4 ,-1 , 0
       0      .2       0    49.8     .05       0   59.95     .05       0
   65.19     .15       0
Levee=0,,,-1,60.42,363.55,,
#Block Obstruct= 1 ,-1
   30.72   43.62368.0001
Bank Sta=49.8,59.95
XS Rating Curve= 0 ,0
Exp/Cntr=0.3,0.1

Type RM Length L Ch R = 1 ,18374.77,12.72,13.16,13.09
XS GIS Cut Line= 3
-608959.05689999   -1044877.1776-609013.50209999   -1044826.1352
-609048.81949999   -1044791.2347
#Sta/Elev= 30
       0   375.3   10.49  372.78      15  371.53   32.38  364.68   36.18   364.1
   41.76  363.61   43.91  363.54   45.61   363.3   50.25  363.18    50.4  363.05
   50.88  361.48   53.79  361.32   56.67  361.56   58.83  363.14   59.59  363.37
   65.56  363.23   69.04  363.48   69.57  363.77   75.91  364.14   82.26  364.21
   83.54  364.29   84.04  364.51   84.48  364.55    88.3  364.42   93.29  364.73
   99.22  366.73  104.13  367.35  112.15  368.12  118.98  368.43  124.28  369.54
#Mann= 4 ,-1 , 0
       0      .2       0   50.25     .05       0   59.59     .05       0
   65.56     .15       0
Levee=0,,,-1,59.63,363.35,,
#Block Obstruct= 2 ,-1
   30.77   43.17367.4476   43.17   45.61366.4337
Bank Sta=50.25,59.59
XS Rating Curve= 0 ,0
Exp/Cntr=0.3,0.1

Type RM Length L Ch R = 1 ,18361.61,12.22,11.56,10.47
XS GIS Cut Line= 3
    -608967.6932   -1044884.2694     -609015.221   -1044843.1214
-609052.62759999   -1044801.8585
#Sta/Elev= 30
       0  374.49   11.75  371.69   24.58  366.45   28.45  365.54   34.76  363.68
   39.38  362.95   47.67  363.21   50.08  361.39   52.34  361.26   54.92  361.49
   56.46  362.18   56.84   362.1    57.1  362.77    57.1  363.21   65.93  363.09
   66.18  362.54   66.26  363.08   66.97  363.08   66.97  362.55   68.93  363.26
   69.65  363.34   76.43  363.59   83.69  364.12   88.17  364.27   90.45  364.11
  101.29  364.51  107.11  365.44  112.43  365.73  117.17  366.78  118.56  367.67
#Mann= 4 ,-1 , 0
       0      .1       0   47.67     .05       0    57.1     .06       0
   65.93     .15       0
Levee=0,,,-1,57.79,363.21,,
#XS Ineff= 2 , 0
           43.16  364.52
Permanent Ineff=
       F       F
Bank Sta=47.67,57.1
XS Rating Curve= 0 ,0
Exp/Cntr=0.3,0.1

Type RM Length L Ch R = 1 ,18350.04,2,2,2.21
XS GIS Cut Line= 4
    -608978.2241   -1044895.2065    -609008.2817   -1044865.0536
-609022.72899999   -1044851.2234-609048.56549999   -1044818.2857
#Sta/Elev= 22
       0  373.57     9.6  371.52   13.82  370.74   28.98  366.75   29.65  366.55
    33.8  363.79   35.16  363.25   36.75   362.9   47.26  363.08    47.8  362.16
   49.92  361.34   52.39  361.21   55.13  361.42    56.2  361.99   57.62  363.12
   57.71  363.12   59.38  363.15    65.2     363    67.3  363.14   75.51  363.06
   96.41  364.13  104.44  364.33
#Mann= 4 ,-1 , 0
       0      .1       0   47.26     .05       0   57.71     .06       0
    67.3     .15       0
Bank Sta=47.26,57.71
XS Rating Curve= 0 ,0
Exp/Cntr=0.5,0.3

Type RM Length L Ch R = 3 ,18348.94,,,
BEGIN DESCRIPTION:
18543.9  PF 241 DØEVÌNÁ LÁVKA PRO PÌŠÍ V
END DESCRIPTION:
Bridge Culvert--1,0,-1,-1, 0
Deck Dist Width WeirC Skew NumUp NumDn MinLoCord MaxHiCord MaxSubmerge Is_Ogee
0.2,1.5,1.4,0, 7, 7, , , 0.98, 0, 0,0,,
   46.75   47.56   50.02   52.47   54.93   57.38   58.19
  363.62   363.9  364.32  364.47  364.32   363.9  363.62
       0  363.22  364.01  364.15  364.01  363.22       0
    46.3   47.11   49.57   52.02   54.48   56.93   57.74
  363.62   363.9  364.32  364.47  364.32   363.9  363.62
       0  363.22  364.01  364.15  364.01  363.22       0
BR Coef=-1 , 0 , 0 ,, 0 ,,,0.8,-1,,0,
WSPro=,,,, 1 ,,,, 0 ,,,, 0 ,,,,-1 ,-1 ,-1 , 0 , 0 , 0 , 0 , 0
BC Design=,, 0 ,, 0 ,,,,,,
BC HTab HWMax=364.3
BC HTab TWMax=364.3
BC HTab MaxFlow=80
BC Use User HTab Curves=0
BC User HTab FreeFlow(D)= 51
              0.         363.053           0.305         363.709
           0.763         363.796           1.832         363.921
           3.053         364.022            4.58         364.119
           6.107         364.196           7.633         364.262
            9.16         364.333          10.687         364.401
          12.214         364.462           13.74         364.523
          15.267         364.579          16.794         364.634
           18.32         364.686          19.847         364.738
          21.374         364.787            22.9         364.837
          24.427         364.939          25.954         364.987
          27.481          365.09          29.007         365.136
          30.534         365.209          32.061         365.281
          33.587         365.352          35.114         365.423
          36.641         365.492          38.167         365.558
          39.694         365.613          41.221         365.673
          42.747         365.727          44.274         365.777
          45.801         365.838          47.328         365.889
          48.854         365.946          50.487         366.013
          52.175         366.075          53.919         366.151
          55.721         366.283          57.584         366.413
          59.508         366.545          61.497         366.686
          63.553         366.871          65.677         367.183
          67.873         367.443          70.141         367.667
          72.486         367.879          74.909         368.086
          77.412         368.292             80.         368.292
            80.8           368.5
BC User HTab Sub Curve(D)= 7
              0.         363.667           0.133         363.676
            0.19         363.684           0.247         363.695
            0.29         363.704           0.304         363.707
           0.304         363.707
BC User HTab Sub Curve(D)= 8
              0.         363.745           0.218          363.75
           0.392          363.76           0.435         363.764
           0.479         363.767           0.522         363.771
           0.566         363.775           0.677          363.78
BC User HTab Sub Curve(D)= 10
              0.         363.824            0.43         363.829
           0.688         363.837           0.774         363.841
            0.86         363.845           0.946          363.85
           1.032         363.855           1.118          363.86
           1.204         363.866           1.414         363.872
BC User HTab Sub Curve(D)= 10
              0.         363.902           0.689         363.907
           1.103         363.916           1.241          363.92
           1.379         363.924           1.517         363.929
           1.654         363.935           1.792         363.941
            1.93         363.947           2.241         363.954
BC User HTab Sub Curve(D)= 12
              0.          363.98           0.988         363.985
           1.581         363.993           1.778         363.997
           1.976         364.001           2.174         364.006
           2.371         364.012           2.569         364.018
           2.767         364.025           2.964         364.032
           3.053         364.034           3.252         364.034
BC User HTab Sub Curve(D)= 12
              0.         364.058           1.322         364.063
            2.38         364.073           2.645         364.077
           2.909         364.081           3.174         364.086
           3.438         364.092           3.702         364.098
           3.967         364.105           4.231         364.114
            4.58         364.121           4.625         364.121
BC User HTab Sub Curve(D)= 11
              0.         364.137           1.685         364.141
           3.033          364.15            3.37         364.153
           3.707         364.157           4.044         364.161
           4.381         364.166           4.718          364.17
           5.055         364.176           5.392         364.182
           5.976         364.189
BC User HTab Sub Curve(D)= 11
              0.         364.215           2.078         364.219
           3.741         364.227           4.988         364.238
           5.404         364.242            5.82         364.246
           6.235         364.252           6.651         364.257
           7.067         364.263           7.633         364.269
           7.765         364.269
BC User HTab Sub Curve(D)= 10
              0.         364.293           2.994         364.301
           3.993         364.302           4.991         364.307
           5.989         364.314           6.987         364.322
           7.985         364.332           8.983         364.344
            9.16         364.347           9.481         364.347
BC User HTab Sub Curve(D)= 8
              0.         364.371           4.708         364.379
           5.885         364.383           7.061         364.389
           8.238         364.397           9.415         364.405
          10.592         364.417          11.434         364.431
BC User HTab Sub Curve(D)= 8
              0.         364.449           5.458         364.456
           6.823          364.46           8.188         364.465
           9.552         364.471          10.917         364.479
          12.282         364.488          13.205         364.502
BC User HTab Sub Curve(D)= 6
              0.         364.528            6.24         364.533
          10.919         364.545          12.479         364.551
          14.039          364.56          15.042          364.57
BC User HTab Sub Curve(D)= 6
              0.         364.606           8.827         364.612
          14.123         364.624          15.888          364.63
          16.794         364.638          16.906         364.638
BC User HTab Sub Curve(D)= 5
              0.         364.684          11.871          364.69
          17.806           364.7           18.32         364.701
           18.75         364.701
BC User HTab Sub Curve(D)= 9
              0.         364.762          15.398         364.766
          19.798         364.773          21.998         364.831
          24.198         365.017          26.397         365.071
          28.597         365.142          30.534         365.212
          30.594         365.212
BC User HTab Sub Curve(D)= 10
              0.         364.841          21.856         364.844
          22.464         364.874          24.198         365.018
          24.284         365.022          26.713         365.135
          29.141         365.209           31.57         365.275
          32.061         365.294          32.352         365.294
BC User HTab Sub Curve(D)= 12
              0.         364.919          23.432         364.958
          23.979         365.003          24.041         365.008
          24.198          365.02          24.284         365.024
          26.713         365.136          29.141          365.21
           31.57         365.276          32.061         365.296
          32.352         365.297          32.417         365.297
BC User HTab Sub Curve(D)= 12
              0.         364.997          23.939         365.003
          24.041          365.01          24.198         365.021
           26.17         365.114          26.351         365.122
          26.713         365.138          29.141         365.212
           31.57         365.278          32.061         365.297
          32.417           365.3          32.482           365.3
BC User HTab Sub Curve(D)= 9
              0.         365.075          25.036         365.081
          26.844         365.145          27.913         365.177
          29.141         365.213           31.57         365.279
          32.061         365.299          32.482         365.303
          32.547         365.303
BC User HTab Sub Curve(D)= 7
              0.         365.153          27.176         365.159
          29.029         365.213          29.904         365.238
          32.061           365.3          32.547         365.306
          32.612         365.306
BC User HTab Sub Curve(D)= 7
              0.         365.232          29.781         365.238
          31.275         365.281          31.592          365.29
          32.061         365.302          32.612         365.309
          32.677         365.309
BC User HTab Sub Curve(D)= 2
              0.          365.31          32.751         365.313
BC User HTab Sub Curve(D)= 2
              0.         365.388          34.423         365.391
BC User HTab Sub Curve(D)= 2
              0.         365.466           36.14         365.469
BC User HTab Sub Curve(D)= 2
              0.         365.545          37.934         365.548
BC User HTab Sub Curve(D)= 3
              0.         365.623          39.694         365.626
          40.023         365.626
BC User HTab Sub Curve(D)= 2
              0.         365.701          42.102         365.704
BC User HTab Sub Curve(D)= 3
              0.         365.779          44.274         365.782
          44.399         365.782
BC User HTab Sub Curve(D)= 10
              0.         365.857          18.035         365.865
          24.047         365.867          30.058         365.874
           36.07         365.888          42.082         365.917
          48.094         365.988          54.105         366.194
          57.584         366.421          57.706         366.421
BC User HTab Sub Curve(D)= 12
              0.         365.936          12.413         365.945
          18.619          365.95          24.826         365.964
          31.032         365.986          37.239         366.025
          43.445         366.096          49.651         366.226
          55.858         366.451          62.064          366.77
          65.677         367.185          65.697         367.185
BC User HTab Sub Curve(D)= 18
              0.         366.014          12.758         366.023
          17.011         366.031          21.263         366.042
          25.516         366.057          29.768         366.078
          34.021         366.107          38.274         366.147
          42.526         366.205          46.779         366.289
          51.032         366.404          55.284          366.56
          59.537         366.762          63.789         367.147
          68.042         367.543          72.295         367.878
          72.486         367.893          72.651         367.893
BC User HTab Sub Curve(D)= 19
              0.         366.092           8.505           366.1
          12.758         366.104          17.011         366.114
          21.263         366.128          25.516         366.146
          29.768         366.172          34.021         366.206
          38.274         366.253          42.526         366.318
          46.779         366.407          51.032         366.525
          55.284         366.675          59.537         366.904
          63.789         367.282          68.042         367.632
          72.295         367.952          76.547         368.265
          77.121         368.268
BC User HTab Sub Curve(D)= 19
              0.          366.17           8.505         366.179
          12.758         366.184          17.011         366.196
          21.263         366.212          25.516         366.234
          29.768         366.263          34.021         366.302
          38.274         366.354          42.526         366.423
          46.779         366.514          51.032         366.633
          55.284         366.786          59.537         367.058
          63.789         367.395          68.042         367.713
          72.295         368.017          76.547          368.32
          80.119         368.323
BC User HTab Sub Curve(D)= 19
              0.         366.249           8.505         366.258
          12.758         366.264          17.011         366.278
          21.263         366.296          25.516          366.32
          29.768         366.353          34.021         366.395
          38.274          366.45          42.526         366.522
          46.779         366.615          51.032         366.735
          55.284         366.912          59.537         367.191
          63.789         367.495          68.042         367.789
          72.295         368.081          76.547         368.375
          80.331         368.378
BC User HTab Sub Curve(D)= 19
              0.         366.327           8.505         366.337
          12.758         366.344          17.011         366.359
          21.263         366.379          25.516         366.405
          29.768          366.44          34.021         366.485
          38.274         366.543          42.526         366.617
          46.779         366.712          51.032         366.839
          55.284         367.046          59.537         367.305
          63.789         367.584          68.042         367.863
          72.295         368.144          76.547          368.43
          80.543         368.433
BC User HTab Sub Curve(D)= 19
              0.         366.405           8.505         366.416
          12.758         366.424          17.011         366.439
          21.263         366.461          25.516         366.489
          29.768         366.526          34.021         366.572
          38.274         366.632          42.526         366.708
          46.779         366.806          51.032         366.953
          55.284         367.162          59.537         367.408
          63.789         367.668          68.042         367.933
          72.295         368.205          76.547         368.485
          80.753         368.488
BC User HTab Sub Curve(D)= 18
              0.         366.483           8.505         366.495
          12.758         366.503          17.011          366.52
          21.263         366.543          25.516         366.574
          29.768         366.612          34.021         366.661
          38.274         366.722          42.526           366.8
          46.779         366.909          51.032         367.067
          55.284         367.269          59.537           367.5
          63.789         367.746          68.042         368.002
          72.295         368.265          75.333           368.5
BC User HTab Sub Curve(D)= 19
              0.         366.561           8.058         366.572
          12.086          366.58          16.115         366.595
          20.144         366.615          24.173         366.642
          28.202         366.676           32.23          366.72
          36.259         366.775          40.288          366.85
          44.317         366.951          48.346         367.081
          52.375         367.243          56.403          367.43
          60.432         367.637          64.461         367.858
           68.49         368.092          72.519         368.338
          74.511           368.5
BC User HTab Sub Curve(D)= 19
              0.          366.64           8.058          366.65
          12.086         366.657          16.115          366.67
          20.144          366.69          24.173         366.715
          28.202         366.748           32.23         366.791
          36.259         366.849          40.288         366.928
          44.317          367.03          48.346         367.164
          52.375          367.33          56.403         367.529
          60.432         367.734          64.461         367.944
           68.49         368.165          72.519         368.395
           73.79           368.5
BC User HTab Sub Curve(D)= 19
              0.         366.718           8.058         366.727
          12.086         366.733          16.115         366.745
          20.144         366.762          24.173         366.785
          28.202         366.815           32.23         366.855
          36.259         366.908          40.288         366.979
          44.317         367.076          48.346         367.206
          52.375         367.373          56.403         367.569
          60.432         367.778          64.461          368.01
           68.49          368.24          72.519         368.474
          72.848           368.5
BC User HTab Sub Curve(D)= 20
              0.         366.796           8.058         366.805
          12.086         366.809          16.115         366.819
          20.144         366.834          24.173         366.854
          28.202         366.881           32.23         366.915
          36.259         366.963          40.288         367.027
          44.317         367.114          48.346         367.231
          52.375         367.377          53.333         367.423
          56.403         367.572          57.493         367.629
          60.432         367.781          64.461         368.016
           68.49         368.261          71.741           368.5
BC User HTab Sub Curve(D)= 24
              0.         366.874           11.45         366.883
          15.267         366.891          19.084         366.901
          22.901         366.916          26.717         366.935
          30.534          366.96          34.351         366.995
          38.168         367.041          41.984         367.105
          45.801         367.184          49.618         367.288
          52.743         367.398          53.435         367.431
          53.762         367.447          57.251         367.619
          57.528         367.634          61.068         367.821
          61.316         367.836          64.885         368.045
          66.277         368.129          68.702         368.279
          71.741         368.502          71.782         368.502
BC User HTab Sub Curve(D)= 26
              0.         366.953           11.45         366.959
          15.267         366.965          19.084         366.974
          22.901         366.985          26.717            367.
          30.534          367.02          34.351         367.046
          38.168         367.082          41.984          367.13
          45.801         367.196          49.547         367.289
          49.618         367.291          50.586         367.325
          53.435         367.434          53.652         367.445
          57.251         367.623          57.393          367.63
          61.068         367.824          61.186         367.831
          64.885         368.048          65.034         368.057
          68.702         368.282          71.741         368.503
          71.782         368.503          72.235         368.503
BC User HTab Sub Curve(D)= 28
              0.         367.031           11.45         367.039
          15.267          367.04          19.084         367.046
          22.901         367.054          26.717         367.065
          30.534         367.079          34.351         367.098
          38.168         367.124          41.984          367.16
          45.801          367.21          47.982         367.253
          49.618         367.294          49.854         367.303
          53.435         367.437          53.532         367.442
          57.251         367.626          57.328          367.63
          61.068         367.827          61.144         367.832
          64.885         368.051          64.958         368.055
          68.702         368.285          71.741         368.505
          71.782         368.505          72.235         368.505
          72.519         368.505          73.398         368.505
BC User HTab Sub Curve(D)= 24
              0.         367.109          12.758         367.116
          17.011         367.117          21.263         367.122
          25.516          367.13          29.768          367.14
          34.021         367.154          38.274         367.174
          42.526         367.202          46.779         367.244
          48.976         367.281          51.032          367.35
          51.136         367.354          55.284         367.531
          55.345         367.535          59.537         367.749
          59.594         367.753          63.789          367.99
          63.842         367.993          68.042         368.248
          68.102         368.252          71.741         368.506
          72.295         368.508          73.894         368.508
BC User HTab Sub Curve(D)= 22
              0.         367.187          16.115         367.192
          28.202         367.205           32.23         367.213
          36.259         367.223          40.288         367.238
          44.317         367.257          48.346         367.284
          50.201         367.325          52.375          367.41
          52.446         367.413          56.403         367.592
          56.462         367.595          60.432         367.803
          60.486         367.806          64.461         368.033
          64.511         368.036           68.49         368.282
          68.533         368.285          71.741         368.508
          72.519         368.511          75.823         368.511
BC User HTab Sub Curve(D)= 23
              0.         367.265          20.144          367.27
           32.23         367.281          36.259         367.288
          40.288         367.297          44.317         367.309
          48.346         367.326          50.881         367.355
          52.375         367.413          52.445         367.416
          56.403         367.595          56.462         367.598
          60.432         367.806          60.486         367.809
          64.461         368.036          64.511          368.04
           68.49         368.285          68.533         368.286
          71.741         368.509          72.519         368.512
          75.823         368.512            80.8         368.512
            80.8         368.512
BC User HTab Sub Curve(D)= 21
              0.         367.344          25.516         367.349
          38.274          367.36          42.526         367.367
          46.779         367.376          51.032         367.388
           51.81         367.394          55.284         367.547
          55.351          367.55          59.537         367.762
          59.595         367.765          63.789         368.001
          63.843         368.004          68.042          368.26
          68.091         368.263           68.49         368.286
          68.533         368.288          71.741         368.511
          72.519         368.514            80.8         368.515
            80.8         368.515
BC User HTab Sub Curve(D)= 19
              0.         367.422          29.768         367.426
          42.526         367.434          46.779          367.44
          51.032         367.447          53.105         367.454
          55.284          367.55          55.351         367.553
          59.537         367.765          59.595         367.768
          63.789         368.004          63.842         368.007
          68.042         368.263          68.091         368.266
           68.49         368.288          68.533         368.289
          71.741         368.512          72.519         368.515
            80.8         368.518
BC User HTab Sub Curve(D)= 17
              0.           367.5          38.274         367.504
          51.032          367.51           54.45         367.517
          55.284         367.553          55.351         367.557
          59.537         367.768          59.594         367.771
          63.789         368.007          63.842          368.01
          68.042         368.266           68.09         368.269
           68.49         368.289          68.533         368.291
          71.741         368.514          72.519         368.517
            80.8         368.522

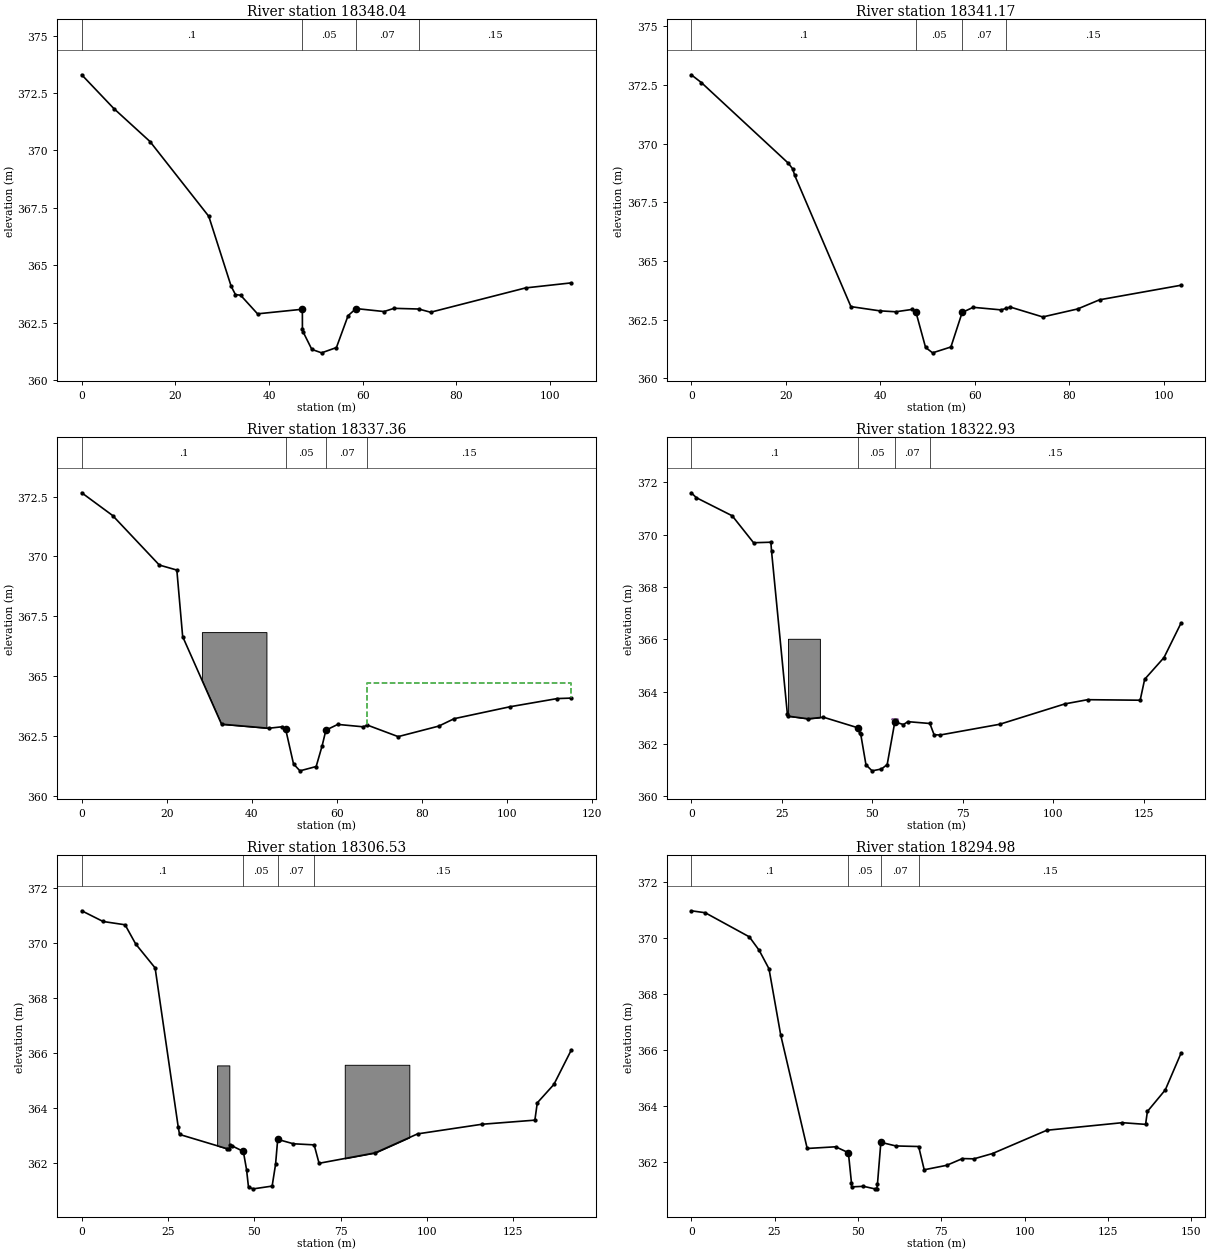
Type RM Length L Ch R = 1 ,18348.04,7.11,6.87,7.11
XS GIS Cut Line= 4
    -608980.1664   -1044896.0904     -609009.671   -1044866.4922
-609024.11829999    -1044852.662-609051.48649999   -1044819.8097
#Sta/Elev= 22
       0   373.3    6.85  371.83   14.58  370.39   27.13  367.13   31.91  364.08
   32.82  363.72   33.93  363.69   37.54  362.88   47.11  363.08   47.12  362.22
    47.3  362.08   49.13  361.33   51.22  361.18   54.38  361.41   56.87   362.8
   58.56  363.11   64.54  362.98   66.68  363.12   71.95  363.09   74.49  362.95
   94.77  364.01  104.55  364.23
#Mann= 4 ,-1 , 0
       0      .1       0   47.11     .05       0   58.56     .07       0
   71.95     .15       0
Bank Sta=47.11,58.56
XS Rating Curve= 0 ,0
Exp/Cntr=0.5,0.3

Type RM Length L Ch R = 1 ,18341.17,3.64,3.82,3.48
XS GIS Cut Line= 3
    -608984.7855   -1044901.5539    -609031.6963   -1044854.4518
    -609056.4353   -1044826.8159
#Sta/Elev= 22
       0  372.94    2.13  372.61   20.54  369.17   21.45  368.93   21.89  368.65
   33.77  363.06   39.86  362.88   43.25  362.84   46.71  362.94   47.49  362.85
   49.56  361.32   51.05  361.09   54.92  361.34    57.3  362.81   59.63  363.03
   65.57  362.92   66.48  362.98   67.49  363.04   74.34  362.62   81.72  362.96
   86.35  363.35  103.57  363.97
#Mann= 4 ,-1 , 0
       0      .1       0   47.49     .05       0    57.3     .07       0
   66.48     .15       0
Bank Sta=47.49,57.3
XS Rating Curve= 0 ,0
Exp/Cntr=0.3,0.1

Type RM Length L Ch R = 1 ,18337.36,14.84,14.42,14.55
XS GIS Cut Line= 4
     -608988.397   -1044905.6744    -609016.6957   -1044874.6581
-609031.05539999   -1044860.7368-609065.50409999   -1044820.1635
#Sta/Elev= 23
       0  372.66    7.27  371.71   18.26  369.64   22.38  369.43   23.75  366.65
   32.89  362.99   44.01  362.82   47.08  362.88   47.98  362.78   49.83  361.33
   51.34  361.04   55.16  361.22   56.57  362.09   57.45  362.74   60.24  362.98
   66.23  362.88   67.23  362.95   74.45  362.47   84.01  362.91   87.64  363.22
  100.82  363.72  111.88  364.06  115.21  364.08
#Mann= 4 ,-1 , 0
       0      .1       0   47.98     .05       0   57.45     .07       0
   67.23     .15       0
#XS Ineff= 2 , 0
                           67.21          364.72
Permanent Ineff=
       F       F
#Block Obstruct= 1 ,-1
   28.28   43.46366.8377
Bank Sta=47.98,57.45
XS Rating Curve= 0 ,0
Exp/Cntr=0.3,0.1

Type RM Length L Ch R = 1 ,18322.93,16.56,16.4,16.08
XS GIS Cut Line= 2
    -608999.2052   -1044914.5843-609092.44469999   -1044816.5633
#Sta/Elev= 30
       0   371.6    1.44  371.41   11.32  370.72   17.22  369.69      22  369.71
   22.18  369.37   26.56  363.14   26.79  363.06   32.25  362.96   36.52  363.02
   46.17  362.61   46.51  362.42    46.8  362.39   48.27   361.2   49.96  360.97
   52.55  361.04   54.13  361.21   56.24  362.84   58.62  362.74   59.86  362.85
   65.92  362.78   67.09  362.35   68.75  362.34    85.2  362.75  103.25  363.53
   109.5  363.69  124.02  363.67  125.26  364.47   130.6   365.3  135.28  366.61
#Mann= 4 ,-1 , 0
       0      .1       0   46.17     .05       0   56.24     .07       0
   65.92     .15       0
Levee=0,,,-1,56.28,362.83,,
#Block Obstruct= 1 ,-1
   26.73   35.54366.0181
Bank Sta=46.17,56.24
XS Rating Curve= 0 ,0
Exp/Cntr=0.3,0.1

Type RM Length L Ch R = 1 ,18306.53,11.47,11.55,11.69
XS GIS Cut Line= 3
-609011.42359999   -1044926.7722     -609089.892   -1044841.4859
-609102.89469999   -1044819.0525
#Sta/Elev= 28
       0  371.18    6.19  370.79   12.56  370.67   15.64  369.97   21.26   369.1
   27.95  363.31   28.33  363.04    42.1  362.52   42.75  362.52   42.97  362.64
   43.45  362.63   46.81  362.42   47.74  361.76   48.31  361.11   49.74  361.06
   55.15  361.16   56.14  361.95   56.76  362.86   61.31   362.7   67.32  362.66
   68.74  361.99   85.01  362.37   97.26  363.06  115.89  363.41  131.24  363.56
  131.94  364.19  136.75  364.86  141.82  366.12
#Mann= 4 ,-1 , 0
       0      .1       0   46.81     .05       0   56.76     .07       0
   67.32     .15       0
#Block Obstruct= 2 ,-1
   39.21   42.75365.5524   76.18   94.88 365.575
Bank Sta=46.81,56.76
XS Rating Curve= 0 ,0
Exp/Cntr=0.3,0.1

Type RM Length L Ch R = 1 ,18294.98,16.32,15.92,15.19
XS GIS Cut Line= 4
    -609019.4125   -1044934.5905    -609077.4164   -1044872.4435
    -609103.2397   -1044839.8467    -609108.1081   -1044820.1617
#Sta/Elev= 29
       0  370.98    4.19  370.91   17.42  370.05   20.37  369.57   23.32  368.91
   26.83  366.55   34.78   362.5    43.3  362.56   47.13  362.35   48.05  361.28
    48.1  361.13   51.66  361.15   55.02  361.06   55.67  361.07   55.85  361.23
   56.87  362.72   61.37  362.59   68.21  362.57   69.87  361.74   76.63   361.9
   81.35  362.14   84.78  362.13   90.37  362.32  106.65  363.15  129.28  363.42
  136.27  363.36  136.81  363.82  142.18  364.59  146.87  365.89
#Mann= 4 ,-1 , 0
       0      .1       0   47.13     .05       0   56.87     .07       0
   68.21     .15       0
Bank Sta=47.13,56.87
XS Rating Curve= 0 ,0
Exp/Cntr=0.3,0.1

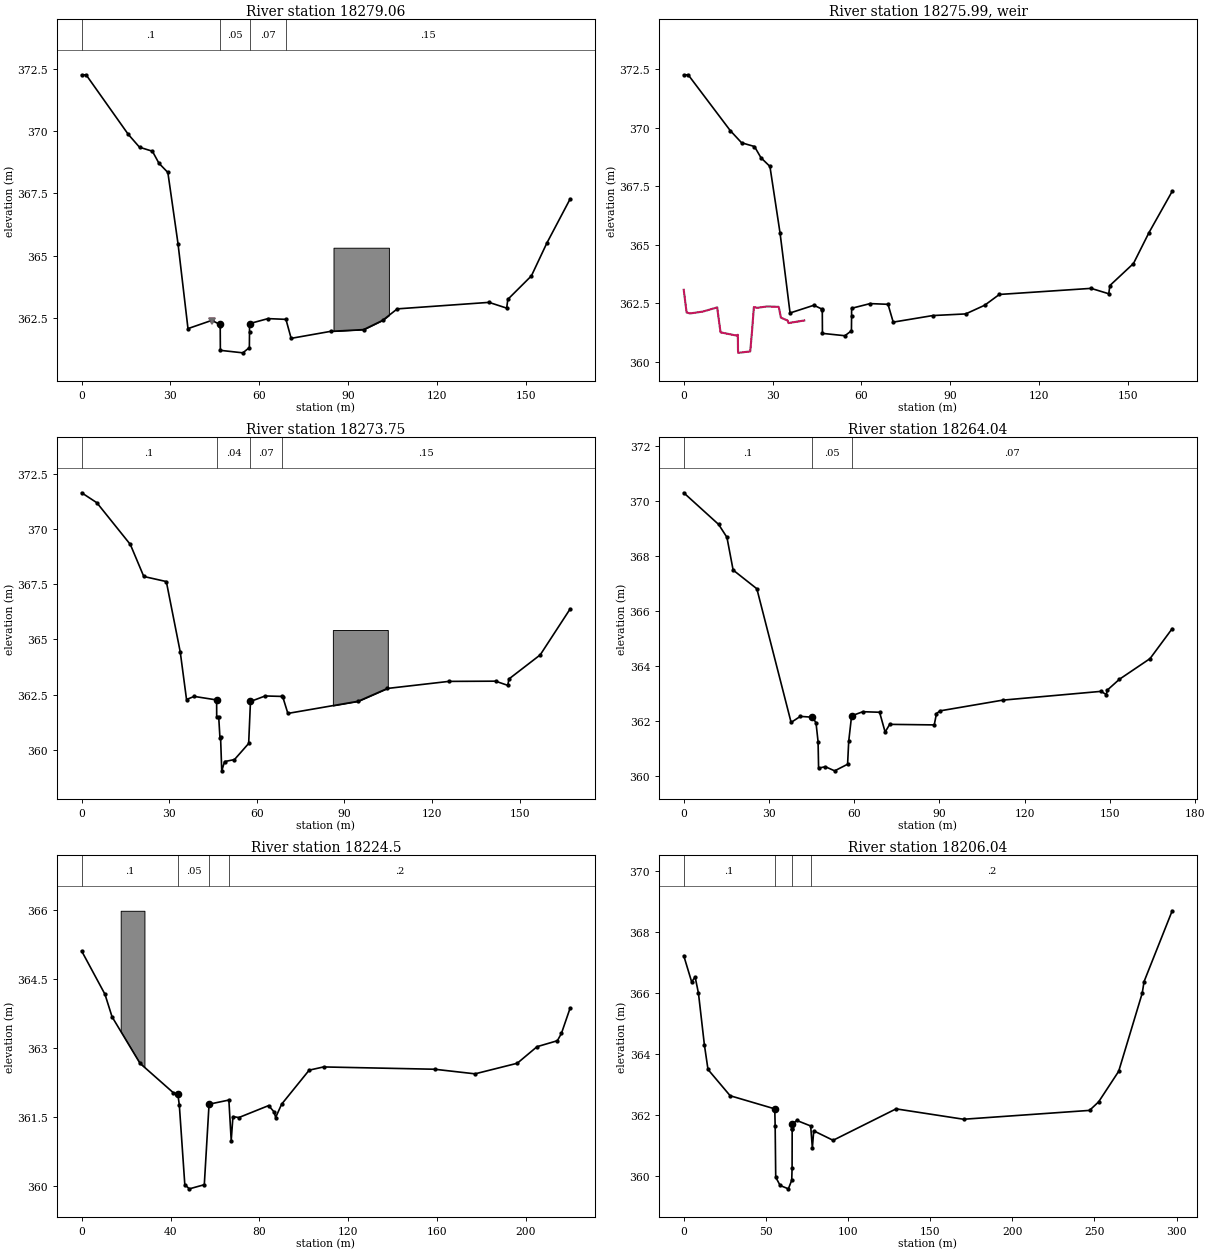
Type RM Length L Ch R = 1 ,18279.06,5.31,5.32,5.33
XS GIS Cut Line= 5
-609032.27279999   -1044946.5812    -609059.4153   -1044915.6818
     -609083.818   -1044887.4375-609116.26419999   -1044848.5425
-609124.47399999   -1044813.5362
#Sta/Elev= 30
       0  372.24     1.5  372.25   15.72  369.87   19.55  369.35   23.91  369.19
   26.11  368.71   29.13  368.34   32.56  365.49   35.93  362.09   43.99  362.42
   46.63  362.26   46.82   362.2   46.87  361.22   54.47  361.12   56.67  361.33
   56.72  361.94   56.73  362.29   62.98  362.49   69.03  362.46   70.79   361.7
   84.14  361.98   95.28  362.05  101.69  362.42  106.65  362.88  137.65  363.14
  143.62  362.91     144  363.26  151.97   364.2  157.22  365.52  165.06  367.28
#Mann= 4 ,-1 , 0
       0      .1       0   46.63     .05       0   56.73     .07       0
   69.03     .15       0
Levee=-1,44.17,362.38,0,,,,
#Block Obstruct= 1 ,-1
    85.1  103.82365.3277
Bank Sta=46.63,56.73
XS Rating Curve= 0 ,0
Exp/Cntr=0.3,0.1

Type RM Length L Ch R = 5 ,18275.99,,,
IW Pilot Flow=0
#Inline Weir SE= 26
       0  363.08     .97  362.11    2.14  362.07    6.45  362.15   11.12  362.32
   11.32  362.33   11.36  362.27   12.43  361.27   12.57  361.26   17.29  361.14
   17.49  361.14   17.77  361.13   18.29  361.16   18.34  360.51   18.39  360.39
   22.47  360.45   23.04  361.25    23.7  362.34    24.9  362.31   28.22  362.37
    32.1  362.35   32.84  361.89   35.08  361.77   35.43  361.66   35.89  361.67
   40.71  361.77
IW Dist,WD,Coef,Skew,MaxSub,Min_El,Is_Ogee,SpillHt,DesHd
0.5,0.5,1.1,0,0.98,, 0 ,,,0,0,
Inline Weir Flap Gates= 0

Type RM Length L Ch R = 1 ,18273.75,3.427,3.233,2.947
XS GIS Cut Line= 5
    -609036.4443   -1044949.8598-609064.65399999   -1044917.7456
-609089.05669999   -1044889.5013-609120.98169999   -1044852.9628
    -609132.1506   -1044815.9045
#Sta/Elev= 30
       0  371.64     5.2  371.19   16.67   369.3   21.28  367.85      29  367.62
   33.77  364.43   35.92  362.28   38.55  362.42   46.23  362.26   46.25  361.49
   46.94   361.5   47.36  360.55   47.57   360.6   47.98  359.05   48.96  359.47
   52.34  359.56    57.2  360.29   57.82  362.19   62.85  362.44    68.5  362.42
   68.85  362.41   70.63  361.65   94.71   362.2  104.69  362.78  125.75   363.1
  141.77  363.11  145.94  362.92  146.35  363.21  157.05   364.3   167.3  366.38
#Mann= 4 ,-1 , 0
       0      .1       0   46.23     .04       0   57.82     .07       0
    68.5     .15       0
#Block Obstruct= 1 ,-1
   86.04  104.85365.4245
Bank Sta=46.23,57.82
XS Rating Curve= 0 ,0
Exp/Cntr=0.3,0.1

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
Type RM Length L Ch R = 1 ,18264.04,12.48,12.71,12.7
XS GIS Cut Line= 5
    -609043.6799   -1044956.0504    -609072.4114   -1044924.5346
-609084.51969999   -1044908.6165    -609125.8273   -1044857.4816
-609142.94559999   -1044817.4285
#Sta/Elev= 30
       0  370.31   12.28  369.16   15.21  368.69   17.39   367.5   25.74  366.82
    37.8  361.96   41.05  362.18   45.27  362.15   46.56  361.95   47.29  361.26
   47.47   360.3   49.85  360.35   53.13   360.2   57.68  360.44   58.07  361.27
   59.09   362.2   63.06  362.35   68.94  362.33   70.89  361.61    72.5  361.89
   88.18  361.87   88.96  362.28   90.18  362.38  112.24  362.77  146.92  363.09
  148.75  362.97  149.04  363.13  153.37  363.53  164.13  364.28  171.94  365.37
#Mann= 3 , 0 , 0
       0      .1       0   45.27     .05       0   59.09     .07       0
Bank Sta=45.27,59.09
XS Rating Curve= 0 ,0
Exp/Cntr=0.3,0.1

Type RM Length L Ch R = 1 ,18224.5 ,18.07,18.46,18.77
XS GIS Cut Line= 3
    -609075.6612   -1044979.0075    -609117.0775    -1044932.579
-609210.79199999   -1044805.8233
#Sta/Elev= 28
       0  365.11   10.49  364.17   13.68  363.68   26.24  362.67   41.24  362.03
   43.28     362   43.96  361.76   46.43  360.03   48.49  359.94    55.2  360.03
   57.34  361.78   66.26  361.87   67.31  360.99   68.09  361.51   70.76  361.49
   84.16  361.75   86.64  361.61    87.3  361.49      90  361.78   102.4  362.52
  108.88  362.59  158.83  362.54  177.06  362.44  196.05  362.67  204.95  363.03
  214.11  363.16  215.94  363.32  219.85  363.87
#Mann= 4 ,-1 , 0
       0      .1       0   43.28     .05       0   57.34     .07       0
   66.26      .2       0
#Block Obstruct= 1 ,-1
   17.57   28.26365.9847
Bank Sta=43.28,57.34
XS Rating Curve= 0 ,0
Exp/Cntr=0.3,0.1

Type RM Length L Ch R = 1 ,18206.04,5.09,4.98,4.99
XS GIS Cut Line= 4
     -609080.951    -1044998.105    -609116.2027    -1044960.872
    -609129.9171   -1044946.3148-609272.49179999   -1044770.8857
#Sta/Elev= 30
       0  367.22    4.83  366.36    6.94  366.52    8.97  365.99   12.57   364.3
   14.78  363.49   28.27  362.63   55.41   362.2   55.65  361.65      56  359.96
    58.7  359.69   63.69  359.58   65.74  359.86   65.96  360.26   66.01  361.53
   66.11  361.55   66.12   361.7   68.84  361.82   77.27  361.64    78.3  360.92
   79.13  361.48   90.93  361.17  129.25   362.2  170.35  361.86     247  362.15
  252.55  362.43  264.74  363.43  279.08  365.99   280.2  366.37  297.33  368.69
#Mann= 4 ,-1 , 0
       0      .1       0   55.41     .05       0   66.12     .07       0
   77.27      .2       0
Bank Sta=55.41,66.12
XS Rating Curve= 0 ,0
Exp/Cntr=0.5,0.3

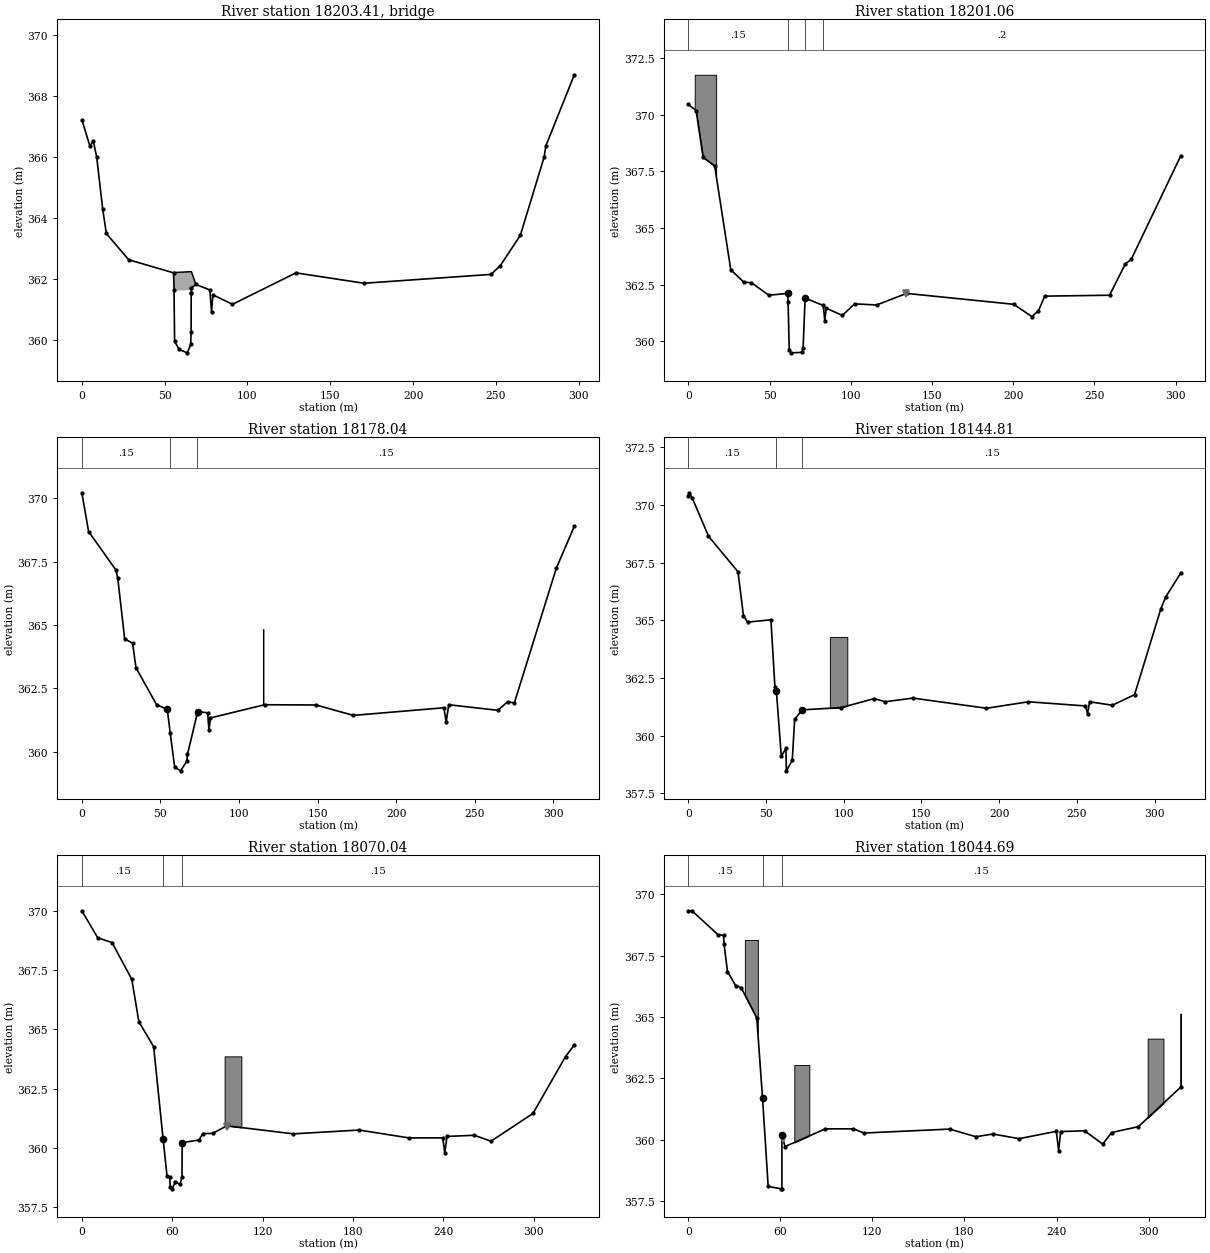
Type RM Length L Ch R = 3 ,18203.41,,,
BEGIN DESCRIPTION:
18399.9  PF 237 SILNIÈNÍ ŽLB MOSTEK V
END DESCRIPTION:
Bridge Culvert--1,0,-1,-1, 0
Deck Dist Width WeirC Skew NumUp NumDn MinLoCord MaxHiCord MaxSubmerge Is_Ogee
0.3,4.5,1.4,0, 5, 5, , , 0.98, 0, 0,0,,
   55.38   55.65   66.06   66.14   68.84
  362.21  362.21  362.24  362.24  361.82
  361.61  361.61  361.64  361.64  361.82
   61.21   61.48   71.89   71.97      74
  362.21  362.21  362.24  362.24  361.85
  361.61  361.61  361.64  361.64  361.85
BR Coef=-1 , 0 , 0 ,, 0 ,,,0.8,-1,,0,
WSPro=,,,, 1 ,,,, 0 ,,,, 0 ,,,,-1 ,-1 ,-1 , 0 , 0 , 0 , 0 , 0
BC Design=,, 0 ,, 0 ,,,,,,
BC HTab HWMax=362.9
BC HTab TWMax=362.8
BC HTab MaxFlow=80
BC Use User HTab Curves=0
BC User HTab FreeFlow(D)= 0

Type RM Length L Ch R = 1 ,18201.06,23.86,23.02,22.09
XS GIS Cut Line= 4
     -609081.967   -1045006.5717-609120.09479999    -1044964.001
    -609133.8092   -1044949.4436    -609276.3839   -1044774.0146
#Sta/Elev= 30
       0  370.45     4.8  370.18    9.09  368.12   16.22  367.74   26.16  363.16
    34.1  362.62   38.88  362.59   49.59  362.04   61.21  362.12   61.43  361.72
   62.15  359.61   63.21   359.5   70.02  359.52   70.68  359.73   71.92  361.91
   83.07  361.59   84.04  360.91   84.84  361.47   94.82  361.15  102.39  361.66
  115.93  361.61  134.35  362.12  200.36  361.64   211.5   361.1  215.58  361.35
  219.39     362  259.37  362.04  269.05  363.42  272.69  363.62  303.21  368.19
#Mann= 4 ,-1 , 0
       0     .15       0   61.21     .05       0   71.92     .07       0
   83.07      .2       0
Levee=0,,,-1,133.77,362.12,,
#Block Obstruct= 1 ,-1
    3.93   17.13371.7588
Bank Sta=61.21,71.92
XS Rating Curve= 0 ,0
Exp/Cntr=0.5,0.3

Type RM Length L Ch R = 1 ,18178.04,32.9,33.23,33.2
XS GIS Cut Line= 4
    -609103.6508   -1045021.0811-609138.55079999   -1044978.8772
    -609151.1605   -1044963.3531    -609291.7859   -1044770.6855
#Sta/Elev= 30
       0  370.22    4.28  368.69   21.67  367.17   22.82  366.86   27.24  364.45
   32.28  364.28    34.4  363.32   47.53  361.85   54.36  361.67   56.22360.7247
   59.04  359.39   62.85  359.24   66.74  359.62   67.19  359.89   73.29 361.474
   73.82  361.58   80.03  361.53   80.86  360.85   81.81  361.33  116.27  361.85
  148.98  361.84   172.7  361.43   230.3  361.73  231.77  361.18  233.41  361.85
   264.6  361.63  270.94  361.97  275.13  361.92  301.82  367.24  313.29   368.9
#Mann= 3 ,-1 , 0
       0     .15       0   56.22     .05       0   73.29     .15       0
#Block Obstruct= 1 ,-1
  115.17  115.55 364.834
Bank Sta=54.36,73.82
XS Rating Curve= 0 ,0
Exp/Cntr=0.3,0.1

Type RM Length L Ch R = 1 ,18144.81,57.17,57.54,57.11
XS GIS Cut Line= 3
    -609126.6578   -1045045.0457    -609180.4545    -1044979.726
-609309.43919999   -1044786.5799
#Sta/Elev= 30
       0   370.4     .58  370.52     2.5   370.3   12.98  368.64   31.96   367.1
   35.49  365.19   38.21  364.92   53.14  365.02   55.75  362.09   56.66  361.95
   59.82  359.11   62.82  359.45   63.07  358.48   66.88  358.93   68.42  360.71
   73.26  361.12   98.47  361.22  119.71  361.61  126.56  361.47  144.56  361.63
  191.84  361.19  218.85  361.47  255.53  361.29  256.86  360.96  258.24  361.47
  272.83  361.32  287.16  361.78  304.06   365.5   307.2  366.01  316.88  367.05
#Mann= 3 , 0 , 0
       0     .15       0   56.66     .05       0   73.26     .15       0
#Block Obstruct= 1 ,-1
   91.09   102.3364.2794
Bank Sta=56.66,73.26
XS Rating Curve= 0 ,0
Exp/Cntr=0.3,0.1

Type RM Length L Ch R = 1 ,18070.04,26.03,25.34,24.56
XS GIS Cut Line= 4
    -609188.4695   -1045088.7556-609221.08839999   -1045048.4074
    -609233.1209    -1045032.432    -609365.3255   -1044814.4483
#Sta/Elev= 30
       0     370   10.54  368.86   20.03  368.66   33.14  367.11   37.84  365.32
   47.64  364.27    53.9360.3909   56.53  358.81   58.19  358.78    58.7  358.34
   59.86  358.27   62.11  358.56   65.23  358.46   66.45  358.77   66.61  360.22
   77.76  360.33   80.25   360.6   86.85  360.61   96.19  360.93  140.38  360.59
  183.97  360.75  216.94  360.42  239.52  360.42  240.85  359.79  242.33  360.48
  260.41  360.53  271.53  360.28  299.39  361.45  320.98  363.85  326.83  364.34
#Mann= 3 ,-1 , 0
       0     .15       0    53.9     .05       0   66.61     .15       0
Levee=0,,,-1,96.59,360.86,,
#Block Obstruct= 1 ,-1
   94.75  105.86363.8593
Bank Sta=53.9,66.61
XS Rating Curve= 0 ,0
Exp/Cntr=0.3,0.1

Type RM Length L Ch R = 1 ,18044.69,39.68,37.85,34.98
XS GIS Cut Line= 4
    -609211.3246   -1045101.1375    -609241.9703   -1045063.7315
    -609258.5068   -1045037.9345    -609384.8456   -1044831.5591
#Sta/Elev= 30
       0  369.31    2.39  369.32   19.27  368.35   22.94  368.32   23.29  367.96
   25.53  366.85   30.81  366.28   34.45  366.19   44.62  364.96   48.36  361.71
   52.05  358.11   60.57  358.01   60.99  358.01      61  360.18   63.04  359.73
   89.32  360.45  107.65  360.45   114.4  360.28  170.26  360.44  187.43  360.13
  198.58  360.24  215.58  360.05  239.86  360.35  241.36  359.56  242.68  360.34
  258.25  360.37  270.11  359.83  275.91   360.3  293.32  360.54  320.97  362.15
#Mann= 3 , 0 , 0
       0     .15       0   48.36     .05       0      61     .15       0
Levee=0,,,-1,61.43,360.05,,
#Block Obstruct= 4 ,-1
   69.09   78.84363.0494   36.85   45.32 368.134  320.66  320.97365.1357
  299.39  309.67364.1195
Bank Sta=48.36,61
XS Rating Curve= 0 ,0
Exp/Cntr=0.3,0.1