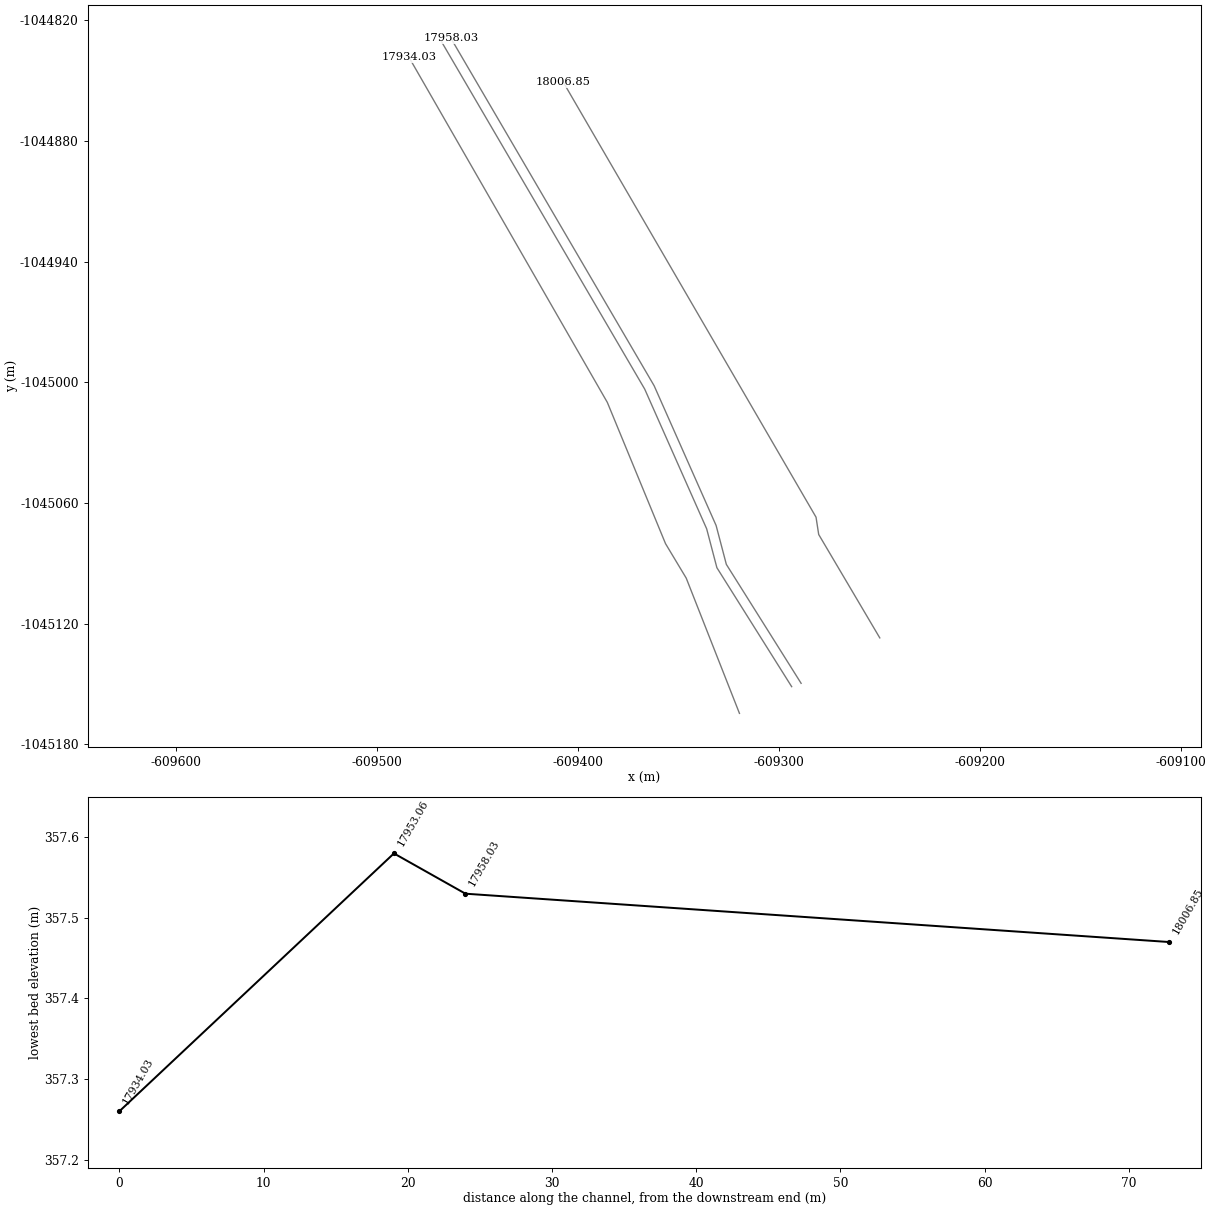
HEC-RAS study PPO_Kvasiny_efektiv.prj: PPO_Kvasiny_efektivita

--- PPO_Kvasiny_efektiv.g04 (geometry) --- (continued)

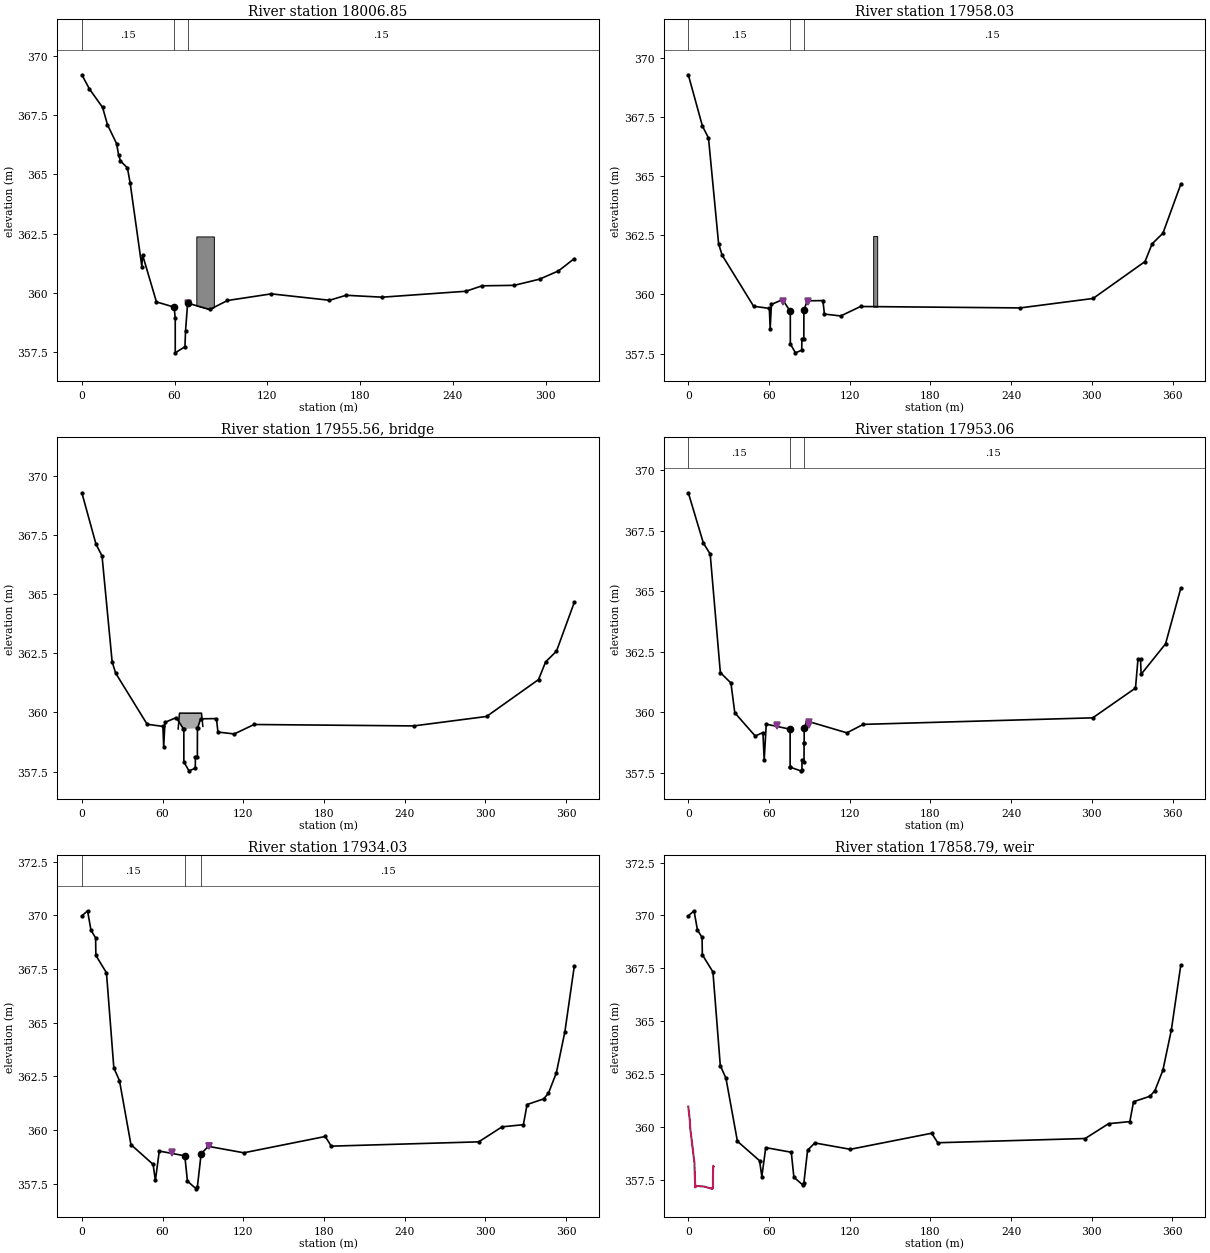
Type RM Length L Ch R = 1 ,18006.85,47.57,48.82,45.88
XS GIS Cut Line= 4
-609249.95389999   -1045127.0667-609280.33489999   -1045075.6377
    -609281.6579   -1045067.0388    -609407.3352   -1044850.7415
#Sta/Elev= 30
       0  369.21    4.91  368.61   13.43  367.83   16.58   367.1    22.5   366.3
   23.75  365.83      25  365.57   29.46  365.28   31.22  364.65   38.82  361.11
   39.25  361.61   48.26  359.62   59.73   359.4   60.41  358.92   60.42  357.47
    66.7  357.73   67.07  358.39   68.43  359.57   82.73   359.3   94.22  359.68
  122.56  359.96  160.18  359.69  170.96   359.9  194.24  359.82  248.41  360.07
  258.94   360.3  279.72  360.32  296.07  360.58  308.35  360.93  318.59  361.45
#Mann= 3 , 0 , 0
       0     .15       0   59.73     .05       0   68.43     .15       0
Levee=0,,,-1,68.68,359.54,,
#Block Obstruct= 1 ,-1
   74.05    85.4362.3846
Bank Sta=59.73,68.43
XS Rating Curve= 0 ,0
Exp/Cntr=0.3,0.1

Type RM Length L Ch R = 1 ,17958.03,4.98,4.96,5.01
XS GIS Cut Line= 5
-609289.07889999   -1045149.6626    -609326.2672   -1045090.5068
    -609331.3531   -1045071.1643-609362.16739999   -1045001.6811
     -609463.228   -1044828.8855
#Sta/Elev= 30
       0  369.29   10.49  367.12   14.99  366.62   22.52  362.14   25.14  361.66
   48.53   359.5   60.23  359.41   60.84  358.54   61.76  359.58   70.13  359.78
   75.55 359.302    75.8   359.3   75.82  357.91   79.63  357.53    84.3  357.64
   84.42  358.13   85.85  358.13   85.91  359.33   86.02359.3391   88.33  359.73
  100.05  359.74  101.16  359.17  113.29  359.09  128.04  359.49  246.69  359.43
  300.86  359.83  339.45  361.39  344.75  362.14  352.79  362.59  366.06  364.66
#Mann= 3 ,-1 , 0
       0     .15       0   75.55     .04       0   86.02     .15       0
Levee=-1,70.67,359.7,-1,88.68,359.7,,
#Block Obstruct= 1 ,-1
   137.4   140.4362.4691
Bank Sta=75.55,86.02
XS Rating Curve= 0 ,0
Exp/Cntr=0.5,0.3

Type RM Length L Ch R = 3 ,17955.56,,,
BEGIN DESCRIPTION:
18151.9  PF 234 NOVÝ SILNIÈNÍ ŽLB MOST 1999 V
END DESCRIPTION:
Bridge Culvert--1,0,-1,-1, 0
Deck Dist Width WeirC Skew NumUp NumDn MinLoCord MaxHiCord MaxSubmerge Is_Ogee
0.3,4.6,1.4,0, 6, 6, , , 0.98, 0, 0,0,,
   71.57   72.57   76.05   86.02   88.94   89.94
   359.3  359.97  359.97  359.97  359.97  359.41
   359.3   359.3   359.3  359.33  359.33  359.41
   71.57   72.57   76.05   86.02   88.94   89.94
   359.3  359.97  359.97  359.97  359.97  359.41
   359.3   359.3   359.3  359.33  359.33  359.41
BR Coef=-1 , 0 , 0 ,, 0 ,,,0.8,-1,,0,
WSPro=,,,, 1 ,,,, 0 ,,,, 0 ,,,,-1 ,-1 ,-1 , 0 , 0 , 0 , 0 , 0
BC Design=,, 0 ,, 0 ,,,,,,
BC HTab HWMax=360.5
BC HTab TWMax=360.4
BC HTab MaxFlow=80
BC Use User HTab Curves=0
BC User HTab FreeFlow(D)= 0

Type RM Length L Ch R = 1 ,17953.06,18.09,19.04,21.99
XS GIS Cut Line= 5
    -609293.7773   -1045151.3166    -609330.9657   -1045092.1607
    -609336.0515   -1045072.8183    -609366.8658   -1045003.3351
-609467.92639999   -1044830.5395
#Sta/Elev= 30
       0  369.07    11.2  366.99   16.25  366.54   23.81  361.64   31.67  361.21
   34.54  359.98   49.71  359.02   55.47  359.16   56.39  358.03   57.93  359.51
   75.67   359.3   75.68  357.75   75.77  357.73   83.46  357.58   84.45  357.61
   84.51  358.04   86.02  357.94   86.03  358.73   86.12  358.74   86.13  359.33
   88.09  359.64  117.88  359.15     130   359.5  300.62  359.77  332.39     361
  334.26  362.21  336.13  362.19  336.58  361.57  354.75  362.83  366.06  365.13
#Mann= 3 , 0 , 0
       0     .15       0   75.67     .04       0   86.13     .15       0
Levee=-1,66.05,359.48,-1,89.61,359.48,,
Bank Sta=75.67,86.13
XS Rating Curve= 0 ,0
Exp/Cntr=0.5,0.3

Type RM Length L Ch R = 1 ,17934.03,65.98,74.44,72.11
XS GIS Cut Line= 5
    -609319.7439   -1045164.6074-609346.21489999    -1045097.348
    -609356.5102   -1045080.2014-609385.44929999   -1045009.9555
    -609484.1037    -1044838.313
#Sta/Elev= 30
       0  369.98    4.24  370.22     6.8  369.31   10.23  368.96   10.42  368.14
    18.3  367.33   23.78   362.9   27.99   362.3   36.51  359.32   52.99   358.4
   54.67  357.65   57.58  359.02   76.56   358.8   78.51  357.62   84.98  357.26
   85.93  357.35    88.7358.8978   94.07  359.24  120.45  358.94  180.97   359.7
   185.5  359.25  295.12  359.45   312.5  360.15  328.34  360.25  331.09  361.19
  343.38  361.45  347.01  361.72  352.88  362.67   359.2  364.58  366.23  367.65
#Mann= 3 ,-1 , 0
       0     .15       0   76.56     .04       0    88.7     .15       0
Levee=-1,66.74,358.96,-1,94.23,359.25,,
Bank Sta=76.56,88.7
XS Rating Curve= 0 ,0
Exp/Cntr=0.3,0.1

Type RM Length L Ch R = 5 ,17858.79,,,
IW Pilot Flow=0
#Inline Weir SE= 20
       0  360.96    1.19  360.26    1.35  359.98    4.59  358.27    4.64  358.05
    5.14  357.18    5.17  357.16     5.2  357.21     5.2  357.22    5.22  357.14
    5.36  357.21    5.45  357.21   11.14  357.18   11.67  357.18   17.74  357.07
   18.05  357.11    18.3  357.09   18.37  357.88   18.52  358.16   18.68  358.13
IW Dist,WD,Coef,Skew,MaxSub,Min_El,Is_Ogee,SpillHt,DesHd
0.5,0.5,1.4,0,0.98,, 0 ,,,0,0,
Inline Weir Flap Gates= 0