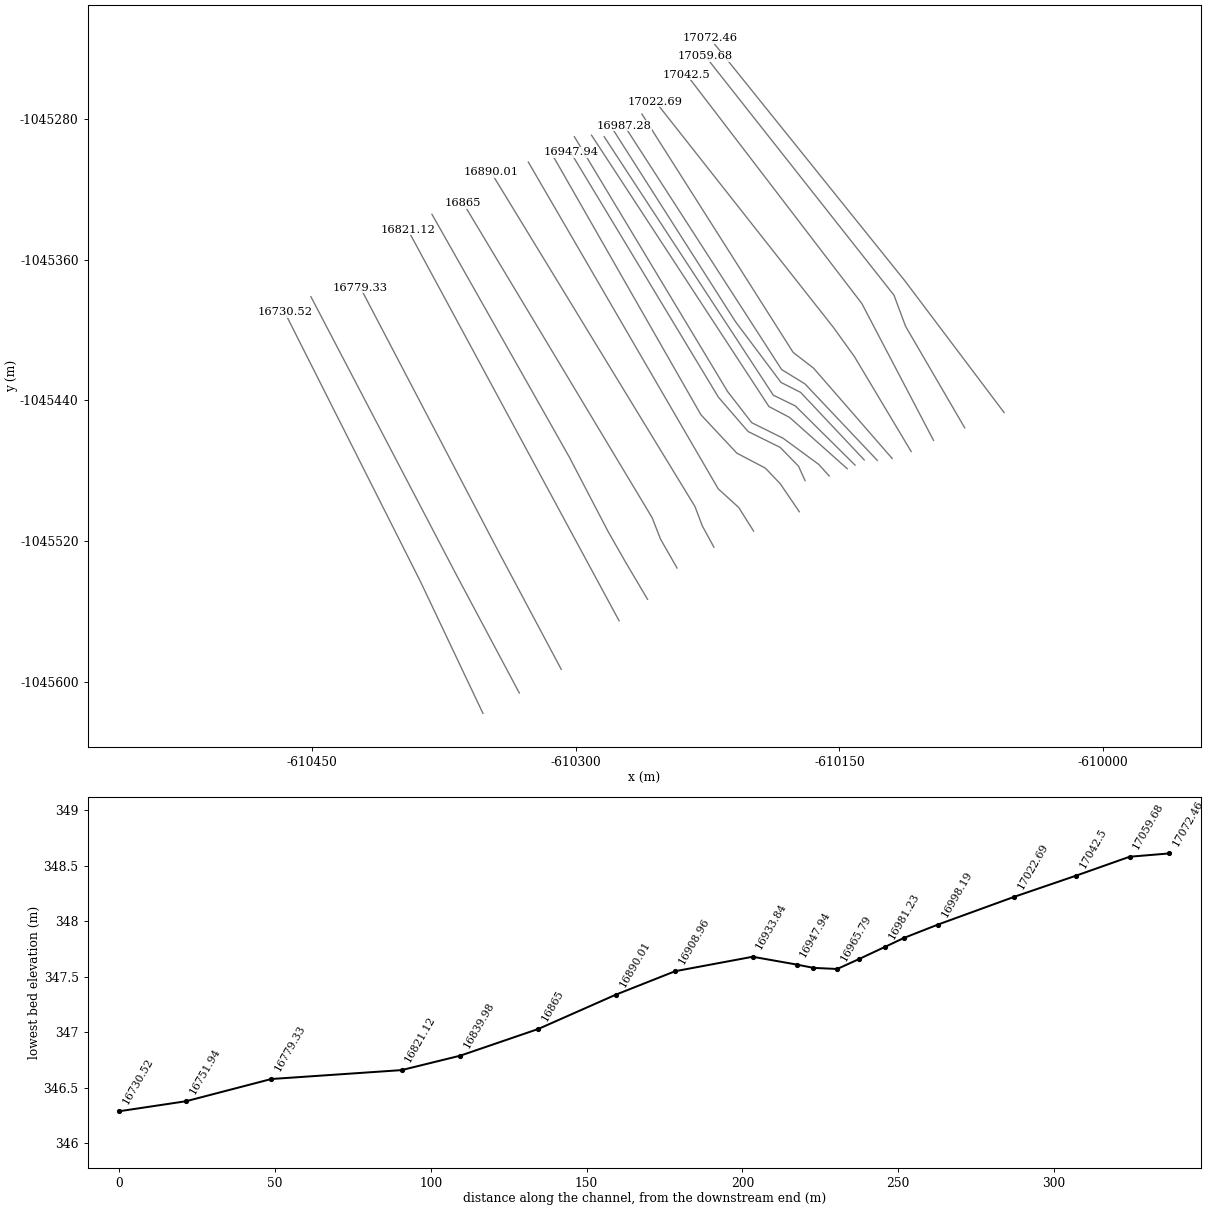
HEC-RAS study PPO_Kvasiny_efektiv.prj: PPO_Kvasiny_efektivita

--- PPO_Kvasiny_efektiv.g04 (geometry) --- (continued)

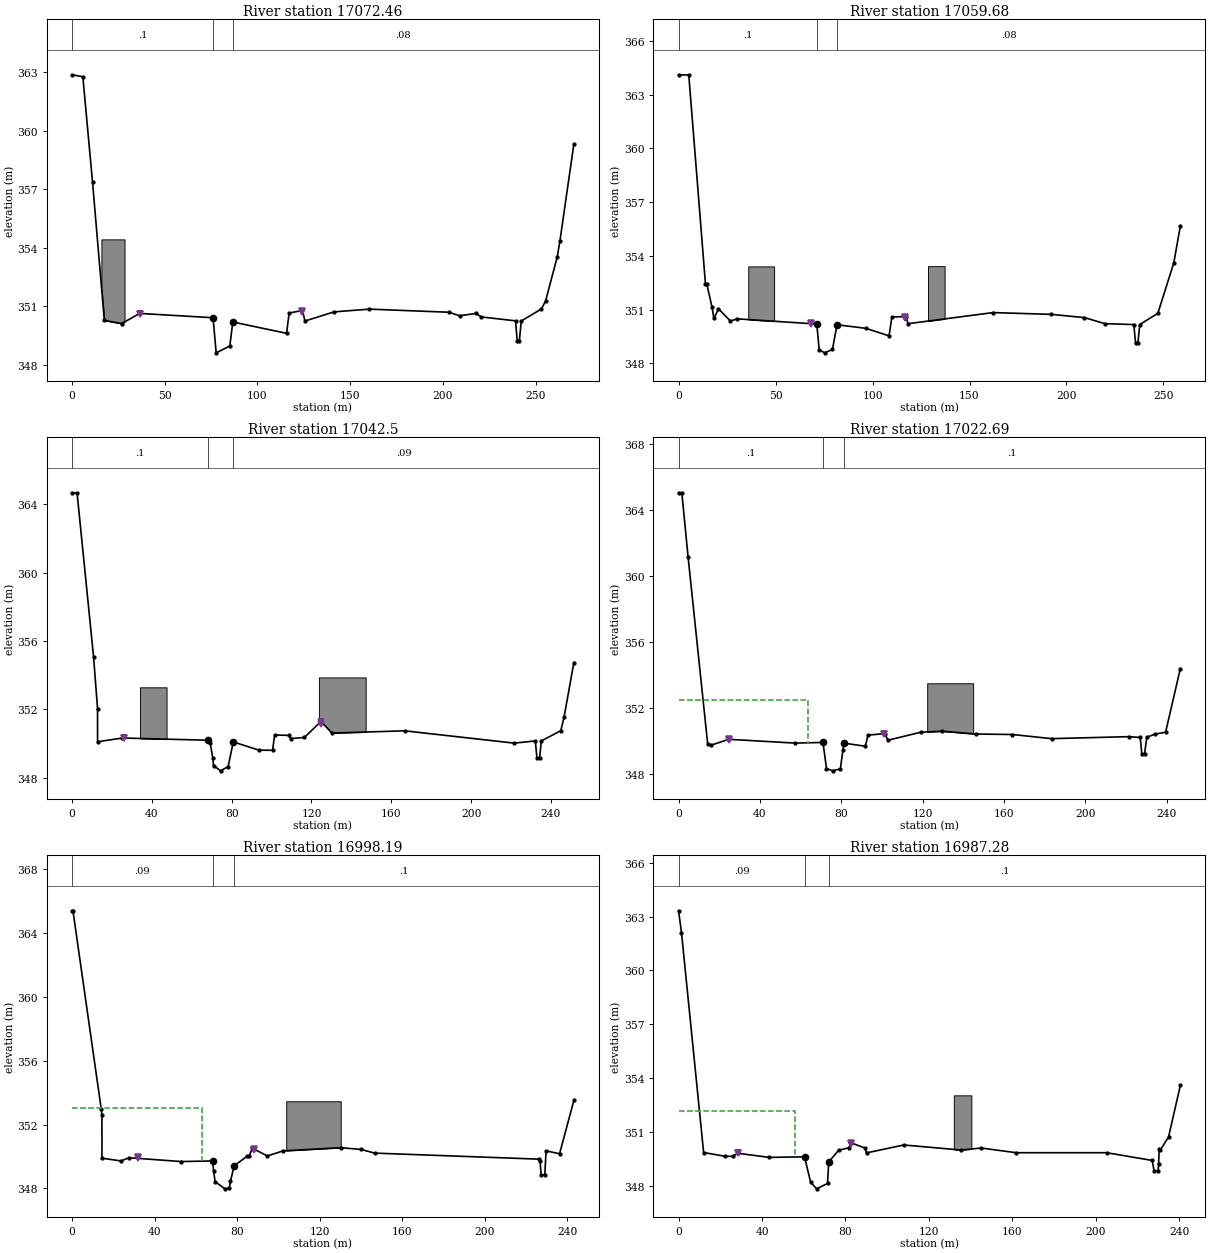
Type RM Length L Ch R = 1 ,17072.46,16.25,12.79,10.07
XS GIS Cut Line= 3
    -610056.4079   -1045446.8883    -610113.0288   -1045371.7464
-610223.62489999   -1045234.1628
#Sta/Elev= 30
       0  362.86    5.81  362.76   11.04  357.35   17.41  350.27   26.76  350.11
   36.49  350.63   75.89  350.41   76.02  350.41   77.72  348.61   85.07  348.96
   86.69  350.19  115.69  349.61  117.06  350.65  124.26  350.78  125.58  350.24
  141.31  350.71  160.37  350.85  203.33  350.69  208.96  350.51  217.84  350.63
  220.67  350.45  239.18  350.25  240.04  349.23  241.23  349.23  242.23  350.24
  253.12  350.86  255.34  351.26  261.63  353.52  263.12  354.36  270.61  359.31
#Mann= 3 , 0 , 0
       0      .1       0   75.89     .05       0   86.69     .08       0
Levee=-1,36.37,350.62,-1,123.85,350.7,,
#Block Obstruct= 1 ,-1
   15.82    28.3354.4257
Bank Sta=75.89,86.69
XS Rating Curve= 0 ,0
Exp/Cntr=0.3,0.1

Type RM Length L Ch R = 1 ,17059.68,16.46,17.17,17.44
XS GIS Cut Line= 4
    -610078.7967   -1045455.5811    -610112.3988   -1045397.9019
-610118.97659999   -1045380.2243-610226.18369999   -1045244.3693
#Sta/Elev= 30
       0   364.1    5.27  364.12   13.87  352.44   14.53  352.44   17.24  351.15
   18.24   350.5    20.6  351.04   26.73  350.36   30.28  350.48   71.29  350.19
   72.49  348.76   75.31  348.58   79.34  348.77   81.72  350.15   96.52  349.95
  108.53  349.53  109.96  350.58  117.11  350.61  118.38  350.21  162.22  350.83
  192.19  350.73  209.23  350.55   219.8  350.21  234.71  350.16  235.58  349.15
  236.82  349.15  237.78  350.16  247.09  350.79  255.32  353.61  258.68  355.67
#Mann= 3 , 0 , 0
       0      .1       0   71.29     .05       0   81.72     .08       0
Levee=-1,68.34,350.27,-1,116.74,350.5,,
#Block Obstruct= 2 ,-1
   35.93   49.28353.4114   128.6  137.17353.4269
Bank Sta=71.29,81.72
XS Rating Curve= 0 ,0
Exp/Cntr=0.3,0.1

Type RM Length L Ch R = 1 ,17042.5 ,17.28,19.81,21.31
XS GIS Cut Line= 3
    -610096.5238   -1045462.7249-610137.26969999   -1045384.9372
     -610236.767   -1045254.9526
#Sta/Elev= 30
       0  364.65     2.5  364.67   10.78  355.07   12.77  352.05   12.78  350.11
   25.22  350.33   68.07   350.2   69.25  350.03   70.53  349.16   70.89  348.72
   74.46  348.41   78.21  348.66   80.82   350.1   93.67  349.62  100.49  349.61
  101.55  350.51  108.74  350.48  109.63   350.3  116.44  350.36  124.74   351.3
  130.23  350.62  166.72  350.75  221.64  350.03   232.2  350.16  233.01  349.15
  234.32  349.15  235.21  350.16  244.98  350.76   246.6  351.55  251.51  354.74
#Mann= 3 , 0 , 0
       0      .1       0   68.07     .05       0   80.82     .09       0
Levee=-1,25.98,350.31,-1,124.88,351.14,,
#Block Obstruct= 2 ,-1
   34.02   47.36353.2942  123.72  147.16 353.872
Bank Sta=68.07,80.82
XS Rating Curve= 0 ,0
Exp/Cntr=0.3,0.1

Type RM Length L Ch R = 1 ,17022.69,20.34,24.51,26.46
XS GIS Cut Line= 4
    -610109.2238   -1045469.0749    -610141.5031   -1045415.0998
-610153.34319999   -1045398.6212    -610254.5471   -1045270.1927
#Sta/Elev= 30
       0  365.06    1.64  365.03     4.7  361.17   14.35  349.82   16.11  349.78
   24.66  350.13   57.31   349.9      71  349.94   72.74  348.36   75.78  348.22
   79.56  348.34   80.83   349.5   81.14   349.9   91.86  349.71   93.12  350.38
  101.55  350.48  102.88  350.07  119.07  350.56  129.71  350.62  146.22  350.45
  164.16  350.42  183.42  350.17   221.4  350.29  226.97  350.24  227.78  349.24
  229.12  349.25  230.18  350.25  234.14  350.44  239.45  350.56  246.69  354.41
#Mann= 3 , 0 , 0
       0      .1       0      71     .05       0   81.14      .1       0
Levee=-1,24.83,350.1,-1,100.89,350.46,,
#XS Ineff= 2 , 0
           63.51  352.54
Permanent Ineff=
       F       F
#Block Obstruct= 1 ,-1
  122.25  144.83353.5231
Bank Sta=71,81.14
XS Rating Curve= 0 ,0
Exp/Cntr=0.3,0.1

Type RM Length L Ch R = 1 ,16998.19,9.12,10.9,11.96
XS GIS Cut Line= 4
    -610120.0189   -1045473.0437    -610164.7152   -1045421.6799
-610176.32229999   -1045412.7185    -610262.3082    -1045277.213
#Sta/Elev= 30
       0   365.4     .44  365.39   14.12  352.99   14.48  352.58   14.49  349.89
   23.72  349.72   27.63  349.92   52.97  349.68   68.09  349.72   68.65  349.06
   69.32  348.43   74.05  347.97   76.26  348.03   76.79  348.45   78.56  349.41
   84.79  350.01   85.77  350.03   87.46  350.51   94.67  350.03  102.27  350.35
  130.13  350.55  140.13  350.44  146.64  350.21  226.48  349.83  226.84  349.73
  227.37  348.85  229.15  348.85  229.77  350.35  236.31  350.17  243.24  353.51
#Mann= 3 , 0 , 0
       0     .09       0   68.09     .05       0   78.56      .1       0
Levee=-1,32.04,349.94,-1,88.19,350.4,,
#XS Ineff= 2 , 0
           63.08  353.05
Permanent Ineff=
       F       F
#Block Obstruct= 1 ,-1
   103.8  130.23  353.46
Bank Sta=68.09,78.56
XS Rating Curve= 0 ,0
Exp/Cntr=0.3,0.1

Type RM Length L Ch R = 1 ,16987.28,5.21,6.05,5.46
XS GIS Cut Line= 4
    -610128.4855    -1045474.102    -610169.6448   -1045430.5961
     -610182.884   -1045422.4552    -610272.3271   -1045283.7394
#Sta/Elev= 30
       0  363.32    1.42   362.1   12.03  349.87   22.39  349.66   25.97  349.66
    28.3  349.83   43.49   349.6   60.39  349.63   63.29  348.22   66.17  347.85
   71.41  348.15   71.96  349.34   76.67  349.99   81.71  350.14    82.7  350.41
   89.37  350.12   90.09  349.85  107.96  350.29  135.21  350.01   145.1  350.12
  161.87  349.86  205.15  349.86  227.01  349.43   227.9  348.85  229.87  348.85
  230.06  349.22  230.34  350.05  230.95  350.02  234.82  350.73  240.48   353.6
#Mann= 3 , 0 , 0
       0     .09       0   60.39     .05       0   71.96      .1       0
Levee=-1,28.72,349.82,-1,82.85,350.32,,
#XS Ineff= 2 , 0
              56  352.16
Permanent Ineff=
       F       F
#Block Obstruct= 1 ,-1
  131.91  140.34 353.052
Bank Sta=60.39,71.96
XS Rating Curve= 0 ,0
Exp/Cntr=0.3,0.1

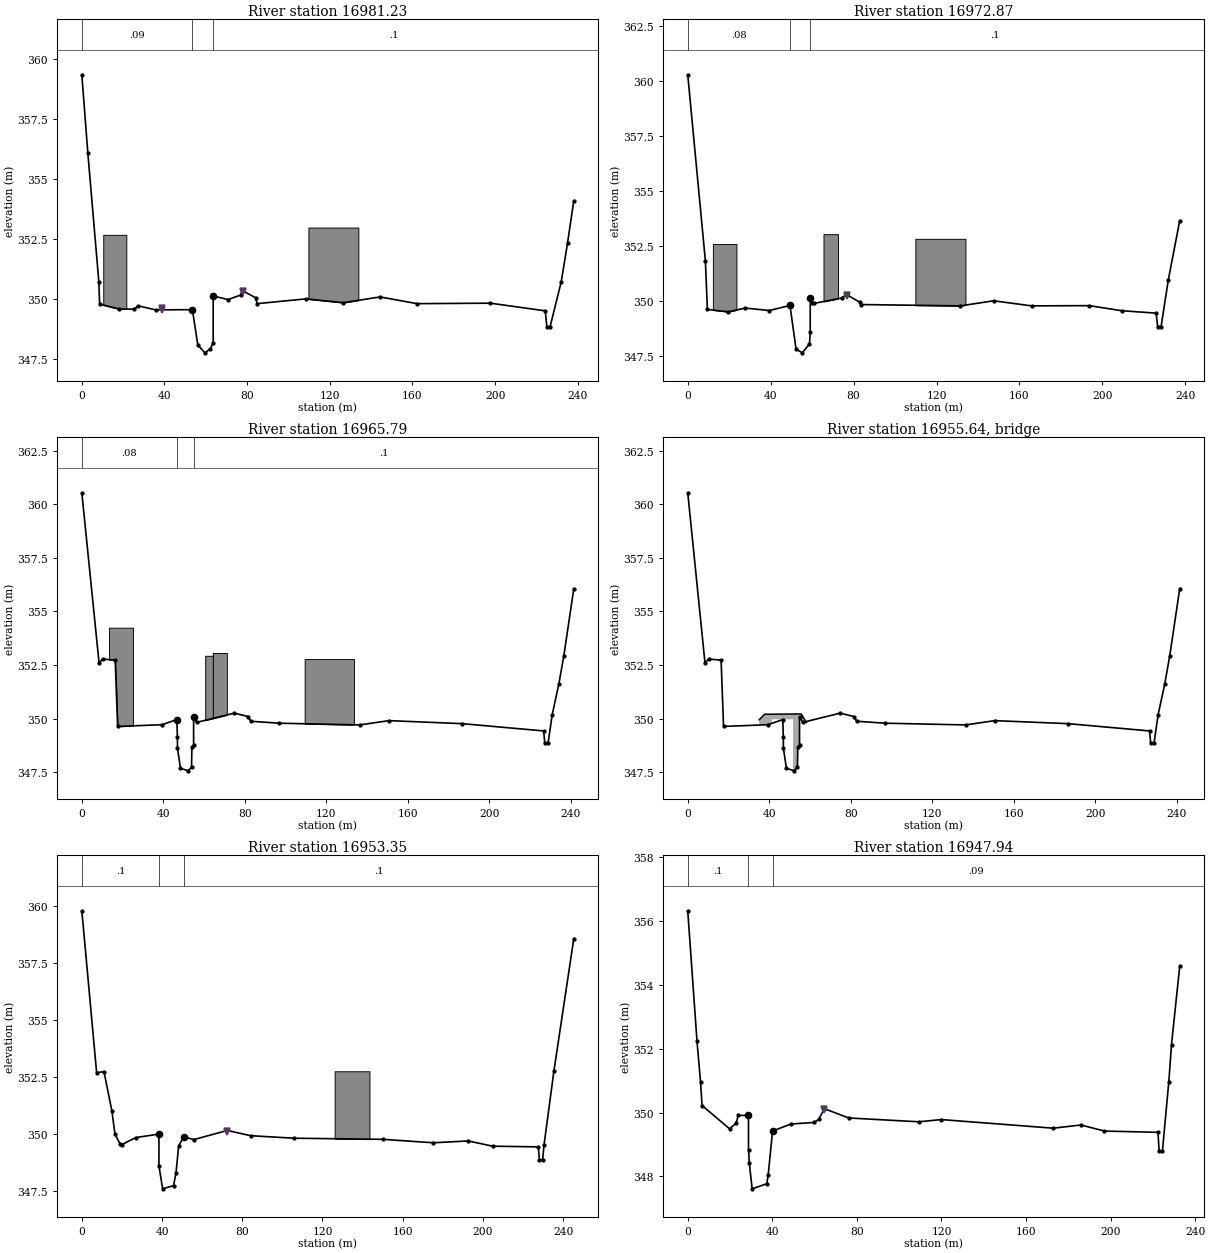
Type RM Length L Ch R = 1 ,16981.23,7.15,8.37,7.3
XS GIS Cut Line= 5
    -610135.9278   -1045473.8311-610172.04879999   -1045435.4654
    -610183.2412   -1045429.7737-610209.17089999   -1045395.1544
    -610278.8182   -1045285.8913
#Sta/Elev= 30
       0  359.36    2.91  356.09    8.22  350.74    8.61   349.8   17.89   349.6
   25.37  349.59   27.28  349.73   35.71  349.56   53.52  349.57   56.11   348.1
   59.56  347.77   62.22  347.94   63.57   348.2   63.58  350.14   70.75  349.99
   76.88  350.18   77.52  350.37   84.05  350.07   84.83  349.82   108.5  350.02
  126.53  349.86  144.31   350.1  162.23  349.82  197.73  349.84  224.27  349.52
  225.05  348.85  226.58  348.85  232.02  350.74  235.04  352.34  238.08  354.11
#Mann= 3 , 0 , 0
       0     .09       0   53.52    .045       0   63.58      .1       0
Levee=-1,38.83,349.62,-1,78.09,350.31,,
#Block Obstruct= 2 ,-1
  109.64  133.82352.9926   10.37   21.53352.6887
Bank Sta=53.52,63.58
XS Rating Curve= 0 ,0
Exp/Cntr=0.3,0.1

Type RM Length L Ch R = 1 ,16972.87,6.4,7.07,5.77
XS GIS Cut Line= 4
-610141.14319999    -1045476.769-610175.05779999   -1045443.1728
    -610187.6253   -1045437.0179    -610283.7571   -1045290.0894
#Sta/Elev= 30
       0  360.27    8.52  351.82    9.48  349.63   19.56  349.52   27.77  349.69
   39.38  349.58   49.32  349.81   52.24  347.83   55.24  347.66   58.72  348.06
   59.08  348.59   59.09  350.16    59.6  350.18   59.65  350.16   59.72  349.93
   60.78   349.9   74.43  350.15   76.38  350.31   83.13  349.95   83.39  349.85
  131.46  349.79   147.6  350.02  165.87  349.79  193.69   349.8  209.31  349.57
  225.93  349.46  226.67  348.85  228.32  348.85  231.83  350.98  237.31  353.65
#Mann= 3 , 0 , 0
       0     .08       0   49.32    .045       0   59.09      .1       0
Levee=0,,,-1,76.79,350.25,,
#Block Obstruct= 3 ,-1
   65.48   72.46353.0419  109.79  133.97352.8312   12.12   23.49 352.596
Bank Sta=49.32,59.09
XS Rating Curve= 0 ,0
Exp/Cntr=0.3,0.1

Type RM Length L Ch R = 1 ,16965.79,5.78,7.61,9.9
XS GIS Cut Line= 4
-610145.59389999   -1045478.8123-610178.31639999   -1045449.6994
-610190.07889999   -1045443.5069    -610290.9538   -1045289.2427
#Sta/Elev= 30
       0  360.53    8.46   352.6   10.21  352.78   16.37  352.73   17.57  349.64
    39.4  349.72   46.62  349.96   46.91  349.13   46.92  348.63   48.41  347.69
   52.27  347.57   53.83  347.75   54.01  348.66   54.85  348.77   54.86  350.09
   56.45  349.83   74.85  350.26   81.55   350.1   82.92  349.88   96.96  349.79
  136.34  349.71  150.68  349.91  186.51  349.77  226.63  349.43  227.16  348.85
  228.78  348.85  230.78  350.17  234.03   351.6   236.5  352.92  241.41  356.06
#Mann= 3 , 0 , 0
       0     .08       0   46.62     .04       0   54.86      .1       0
#Block Obstruct= 4 ,-1
   64.27   71.16353.0629   60.53   64.27352.9328  109.34  133.53352.7794
   13.35   25.08354.2424
Bank Sta=46.62,54.86
XS Rating Curve= 0 ,0
Exp/Cntr=0.3,0.1

Type RM Length L Ch R = 3 ,16955.64,,,
BEGIN DESCRIPTION:
17149.9  PF 220 ŽELEZNÝ MOSTEK PRO PÌŠÍ V KVASINÁCH (F37)
END DESCRIPTION:
Bridge Culvert--1,0,-1,-1, 0
Deck Dist Width WeirC Skew NumUp NumDn MinLoCord MaxHiCord MaxSubmerge Is_Ogee
0.5,1.6,1.4,0, 6, 6, , , 0.98, 0, 0,0,,
   35.06   37.76   41.26   51.67   55.67   58.27
  349.95  350.21  350.21  350.22  350.22  349.82
                  349.97  349.97
   32.19   34.89   38.39    48.8    52.8    55.4
  349.95  350.21  350.21  350.22  350.22  349.82
                  349.97  349.97
BR Coef= 1 , 0 , 0 ,, 0 ,,,0.8,0,2,0,
WSPro=,,,, 1 ,,,, 0 ,,,, 0 ,,,,-1 ,-1 ,-1 , 0 , 0 , 0 , 0 , 0
BC Design=,, 0 ,, 0 ,,,,,,
BC HTab HWMax=350.7
BC HTab TWMax=350.6
BC HTab MaxFlow=80
BC Use User HTab Curves=0
BC User HTab FreeFlow(D)= 0

Type RM Length L Ch R = 1 ,16953.35,6.05,5.41,5.58
XS GIS Cut Line= 6
    -610155.8555   -1045482.9451    -610161.7397   -1045476.4255
    -610181.9567   -1045461.5702    -610199.8667    -1045452.669
    -610213.6235   -1045434.9184-610300.69799999    -1045290.095
#Sta/Elev= 30
       0  359.77    7.38  352.67   11.04  352.72   14.96  351.01   16.53  349.98
      19  349.56   19.86  349.52   27.02  349.83   38.39  349.98   38.44  349.97
   38.45   348.6   40.28  347.58   45.74  347.72   46.98  348.29   48.27  349.46
   50.81  349.86    55.9  349.74   72.53  350.14   84.15  349.91   105.7   349.8
  150.23  349.75  175.23   349.6  192.72  349.68  204.79  349.45  227.61  349.42
  228.15  348.85  229.78  348.85  230.43  349.48  235.42  352.76  245.31  358.55
#Mann= 3 , 0 , 0
       0      .1       0   38.39    .035       0   50.81      .1       0
Levee=0,,,-1,72.32,350.06,,
#Block Obstruct= 1 ,-1
  126.05  143.43352.7345
Bank Sta=38.39,50.81
XS Rating Curve= 0 ,0
Exp/Cntr=0.5,0.3

Type RM Length L Ch R = 1 ,16947.94,14.61,14.1,13.66
XS GIS Cut Line= 6
    -610169.5517   -1045485.6161-610173.24989999    -1045477.427
    -610183.6554   -1045466.7471-610201.92269999   -1045457.7056
    -610218.8174   -1045438.1758    -610302.8072   -1045298.9794
#Sta/Elev= 30
       0  356.32    4.38  352.23    6.07  350.95    6.77  350.22   19.78  349.49
   22.82  349.66    23.9  349.91   28.73  349.91   28.74  348.84   29.13  348.41
   30.46  347.61   37.39  347.77   38.04  348.04   40.11  349.42   48.72  349.64
   59.87  349.69   61.96  349.79   64.59  350.12   76.11  349.83  109.33  349.71
  119.86  349.78  172.83  349.51  185.94  349.61  197.09  349.42   222.4  349.38
  222.92   348.8   224.5   348.8  227.52  350.97  228.79  352.13  232.67  354.58
#Mann= 3 , 0 , 0
       0      .1       0   28.73    .045       0   40.11     .09       0
Levee=0,,,-1,64.52,350.09,,
Bank Sta=28.73,40.11
XS Rating Curve= 0 ,0
Exp/Cntr=0.3,0.1

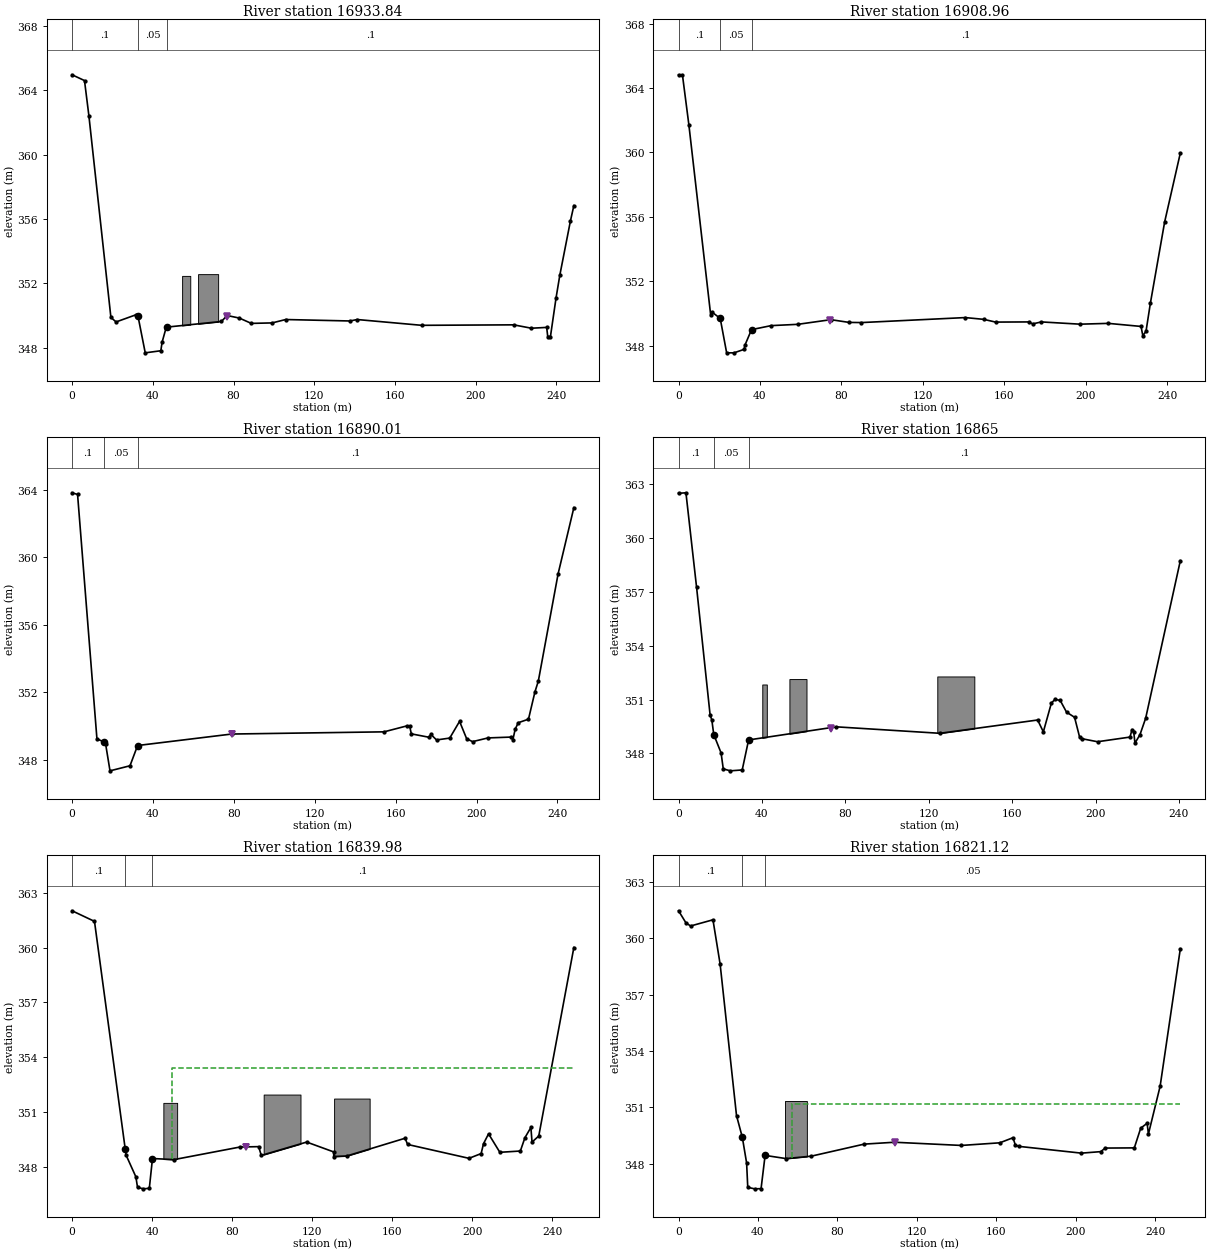
Type RM Length L Ch R = 1 ,16933.84,27.14,24.89,15.43
XS GIS Cut Line= 6
    -610172.8312   -1045503.2958    -610183.6262   -1045487.4208
    -610192.1378   -1045478.4949    -610208.3665   -1045469.9668
    -610228.7441   -1045448.1827    -610312.5439   -1045301.5194
#Sta/Elev= 30
       0  364.96    6.16   364.6    8.34  362.41   19.24  349.88   21.81   349.6
   31.53  350.04   32.63  349.98   36.25  347.68   43.98  347.81    44.6  348.34
    46.6  349.24   47.05  349.28      74  349.63   76.83     350   82.89  349.84
    88.8  349.51   99.14  349.54  105.83  349.75  137.71  349.66  141.24  349.75
  173.25  349.39  218.78  349.42  227.56  349.21  235.14  349.26  235.67  348.69
  237.01  348.69  239.77  351.08  241.66  352.51   246.9  355.87  248.61  356.83
#Mann= 3 , 0 , 0
       0      .1       0   32.63     .05       0   47.05      .1       0
Levee=0,,,-1,76.79,349.93,,
#Block Obstruct= 2 ,-1
   54.52   58.56352.4616   62.43   72.37352.5712
Bank Sta=32.63,47.05
XS Rating Curve= 0 ,0
Exp/Cntr=0.3,0.1

Type RM Length L Ch R = 1 ,16908.96,23.54,18.95,17.48
XS GIS Cut Line= 4
    -610198.8204   -1045514.3025-610207.27569999   -1045500.8694
-610218.91739999    -1045490.286-610326.86769999   -1045304.5481
#Sta/Elev= 30
       0  364.82    1.92  364.81    5.06  361.73   15.76  349.93   16.33  350.09
   20.47  349.69   23.63  347.55   27.25  347.55   32.28  347.77   32.56  348.01
   35.84  348.99   45.46  349.24   58.51  349.32   74.81  349.61   83.76  349.44
   89.85  349.43  140.81  349.74  149.89  349.63   155.7  349.46  171.89  349.47
  173.96  349.35  178.22  349.47  197.19  349.33  211.07  349.38  227.15  349.19
  228.01  348.62  229.58  348.88  231.73  350.63  238.74  355.68  246.44  359.96
#Mann= 3 , 0 , 0
       0      .1       0   20.47     .05       0   35.84      .1       0
Levee=0,,,-1,74.62,349.53,,
Bank Sta=20.47,35.84
XS Rating Curve= 0 ,0
Exp/Cntr=0.3,0.1

Type RM Length L Ch R = 1 ,16890.01,24.27,25.01,24.32
XS GIS Cut Line= 4
-610221.34499999   -1045523.4945-610227.91319999   -1045511.4527
    -610232.1466   -1045500.3402-610348.03429999    -1045310.369
#Sta/Elev= 30
       0  363.81    2.72  363.71    12.3  349.23   15.89  349.05   16.62  348.91
   18.76  347.34   28.64  347.64   32.41  348.84   78.95  349.52  154.27  349.65
  165.49     350  166.92     350  167.77  349.53  176.48  349.33  177.43   349.5
  180.22  349.17  186.76  349.28  191.62  350.27  195.13  349.24  198.05  349.07
   205.7  349.29  217.16  349.34     218  349.19  219.11   349.8  220.63  350.19
   225.7   350.4  228.92  352.03  230.56  352.65  240.37  359.02  248.14  362.93
#Mann= 3 , 0 , 0
       0      .1       0   15.89     .05       0   32.41      .1       0
Levee=0,,,-1,79.1,349.54,,
Bank Sta=15.89,32.41
XS Rating Curve= 0 ,0
Exp/Cntr=0.3,0.1

Type RM Length L Ch R = 1 ,16865   ,23.67,25.02,24.87
XS GIS Cut Line= 4
    -610242.3339   -1045535.2969-610251.72569999   -1045518.8611
-610256.48829999   -1045506.6902-610363.90929999   -1045327.8315
#Sta/Elev= 30
       0  362.48    3.55  362.51    8.65  357.25   15.13  350.15   15.97  349.86
   16.89  349.05    20.4  348.03   21.45  347.14   24.84  347.03   30.54  347.08
    33.6  348.75   75.61  349.48  125.31  349.12  172.22  349.86  174.95   349.2
  178.82  350.81  180.57  351.01  183.03  350.95  186.06   350.3  189.92  350.01
  192.38  348.89  193.39  348.82  200.93  348.65  216.51  348.91  217.48  349.33
  218.28  349.22  218.88  348.57  221.31  349.05  224.02  349.96  240.64  358.73
#Mann= 3 , 0 , 0
       0      .1       0   16.89     .05       0    33.6      .1       0
Levee=0,,,-1,73.04,349.36,,
#Block Obstruct= 3 ,-1
   40.16   42.34351.8377   53.17   61.37352.1396  124.09  141.85352.2846
Bank Sta=16.89,33.6
XS Rating Curve= 0 ,0
Exp/Cntr=0.3,0.1

Type RM Length L Ch R = 1 ,16839.98,20.16,18.86,18.8
XS GIS Cut Line= 5
    -610259.1032   -1045553.0799-610271.81769999   -1045531.5794
    -610281.7151      -1045514.2-610303.42729999   -1045472.5025
-610381.65659999   -1045334.2117
#Sta/Elev= 30
       0  362.01   11.21  361.43    26.6  348.95   27.07  348.62   31.89  347.45
   32.73  346.87   35.66  346.79   38.62  346.82    40.2  348.45   50.96  348.39
   83.99  349.08   93.27   349.1    94.6  348.62  117.31  349.35  130.81  348.81
  130.81  348.56  137.38  348.59   166.5  349.56  167.74  349.22  198.45  348.46
  204.51  348.72   205.7  349.26  208.22   349.8  213.87  348.79  224.12  348.86
  226.41  349.59  229.39  350.15  229.96  349.35  233.32  349.68  250.87     360
#Mann= 3 , 0 , 0
       0      .1       0    26.6     .05       0    40.2      .1       0
Levee=0,,,-1,87.12,349.06,,
#XS Ineff= 2 , 0
                           49.88          353.39
Permanent Ineff=
       F       F
#Block Obstruct= 3 ,-1
   45.64   52.53351.4954     131  148.77351.7318   95.79   114.2 351.951
Bank Sta=26.6,40.2
XS Rating Curve= 0 ,0
Exp/Cntr=0.3,0.1

Type RM Length L Ch R = 1 ,16821.12,43.01,41.79,41.65
XS GIS Cut Line= 2
-610275.27459999   -1045565.3143    -610395.3498   -1045343.0538
#Sta/Elev= 30
       0  361.46    3.71  360.82    6.05  360.65   17.33  360.98   20.94  358.62
   29.19  350.56   32.12   349.4   34.27  348.04   34.85  346.74   38.31  346.66
   41.55  346.67   43.58  348.44   54.15  348.27   66.86   348.4   93.44  349.04
  108.69  349.14  142.41  348.97  161.72  349.11  168.37  349.38   169.6  348.98
  171.36  348.92  202.82  348.56  212.54  348.64  214.81  348.83  229.46  348.84
  232.68  349.89   235.9  350.15  236.56  349.58  242.45  352.12  252.62  359.44
#Mann= 3 , 0 , 0
       0      .1       0   32.12     .05       0   43.58     .05       0
Levee=0,,,-1,108.95,349.09,,
#XS Ineff= 2 , 0
                           56.99          351.15
Permanent Ineff=
       F       F
#Block Obstruct= 1 ,-1
   53.58   64.61351.3344
Bank Sta=32.12,43.58
XS Rating Curve= 0 ,0
Exp/Cntr=0.3,0.1

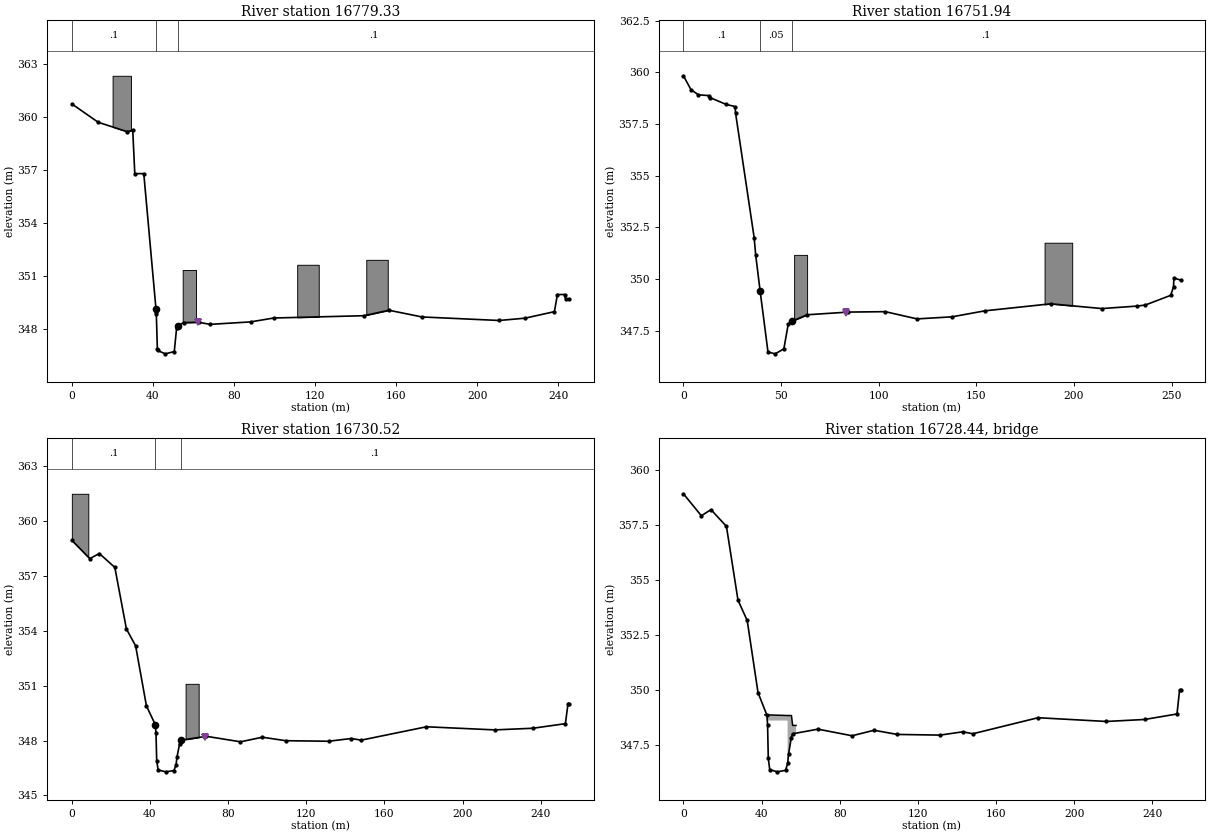
Type RM Length L Ch R = 1 ,16779.33,27.37,27.39,27.36
XS GIS Cut Line= 3
-610308.17929999   -1045592.8645    -610344.1895   -1045525.2731
    -610422.3832   -1045375.8722
#Sta/Elev= 30
       0  360.74   13.01   359.7   27.24  359.17   30.05  359.24   31.05  356.79
   35.49  356.79   41.52   349.1   41.67  348.96   41.68  348.82   42.18  346.88
   42.35  346.77    46.1  346.58   50.53  346.71   51.68  348.04   52.23  348.16
   55.08  348.35   62.56  348.37   68.18  348.25   88.19  348.39   99.57  348.61
  144.02  348.74  156.41  349.05   172.7  348.67  210.75  348.47  223.51   348.6
  238.02  348.97  239.52  349.94  243.06  349.94  243.51  349.69  245.21   349.7
#Mann= 3 , 0 , 0
       0      .1       0   41.52     .05       0   52.23      .1       0
Levee=0,,,-1,62.36,348.38,,
#Block Obstruct= 4 ,-1
    20.1   29.15362.3344   54.68   61.27351.3319  111.15  121.79351.6265
  145.23  155.83351.9062
Bank Sta=41.52,52.23
XS Rating Curve= 0 ,0
Exp/Cntr=0.3,0.1

Type RM Length L Ch R = 1 ,16751.94,21.77,21.42,20.49
XS GIS Cut Line= 3
-610331.99179999   -1045606.3583     -610368.002   -1045538.7669
    -610450.4891    -1045381.048
#Sta/Elev= 30
       0  359.83    3.86  359.16    7.68  358.91    13.1  358.87   13.71  358.77
   21.76  358.45   26.44  358.34   26.69  358.03   36.22     352   37.03  351.14
    39.3   349.4    43.3  346.47   46.95  346.38   51.43  346.62   53.67  347.82
   55.59  347.96   63.34  348.27    84.5   348.4  103.36  348.42  119.61  348.07
  137.55  348.17  154.31  348.46  188.11   348.8   214.3  348.57  232.32  348.69
   236.5  348.74  249.53  349.21  250.98  349.63  251.15  350.05  254.57  349.95
#Mann= 3 , 0 , 0
       0      .1       0    39.3     .05       0   55.59      .1       0
Levee=0,,,-1,83.25,348.35,,
#Block Obstruct= 2 ,-1
  184.93  199.08351.7553   56.68   63.33351.1675
Bank Sta=39.3,55.59
XS Rating Curve= 0 ,0
Exp/Cntr=0.3,0.1

Type RM Length L Ch R = 1 ,16730.52,4.86,4.82,4.85
XS GIS Cut Line= 3
    -610352.6812   -1045617.9347-610388.15709999   -1045543.0952
    -610465.3939   -1045389.8634
#Sta/Elev= 30
       0  358.93    9.19  357.93   14.08  358.21   22.01  357.45   27.93  354.09
   32.64  353.17   38.18  349.89   42.75  348.86   43.07   348.4   43.43   346.9
   44.17  346.39   48.14  346.29   52.25  346.36   53.34  346.67   53.78  347.08
   55.17  347.83   55.91  348.02   68.85  348.23    86.3  347.93   97.54  348.18
  109.47  347.99  131.38  347.96  142.98  348.11   148.1  348.02  181.48  348.75
  216.45  348.58  235.97  348.67  252.59  348.92  253.94  350.02  254.42  350.01
#Mann= 3 , 0 , 0
       0      .1       0   42.75     .05       0   55.91      .1       0
Levee=0,,,-1,67.9,348.17,,
#Block Obstruct= 2 ,-1
       0    8.43361.4715   58.22   64.91351.0959
Bank Sta=42.75,55.91
XS Rating Curve= 0 ,0
Exp/Cntr=0.5,0.3

Type RM Length L Ch R = 3 ,16728.44,,,
Bridge Culvert--1,0,-1,-1, 0
Deck Dist Width WeirC Skew NumUp NumDn MinLoCord MaxHiCord MaxSubmerge Is_Ogee
1,1.6,1.4,0, 6, 6, , , 0.98, 0, 0,0,,
   41.62   43.12   53.32   55.29    55.9   57.62
  348.88  348.88  348.85  348.85   348.4   348.4
          348.62  348.62
   41.45   42.95   53.15   55.12   55.73   57.45
  348.88  348.88  348.85  348.85   348.4   348.4
          348.62  348.62
BR Coef=-1 , 0 , 0 ,, 0 ,,,0.8,-1,,0,
WSPro=,,,, 1 ,,,, 0 ,,,, 0 ,,,,-1 ,-1 ,-1 , 0 , 0 , 0 , 0 , 0
BC Design=,, 0 ,, 0 ,,,,,,
BC HTab HWMax=350
BC HTab TWMax=349.9
BC HTab MaxFlow=80
BC Use User HTab Curves=0
BC User HTab FreeFlow(D)= 0