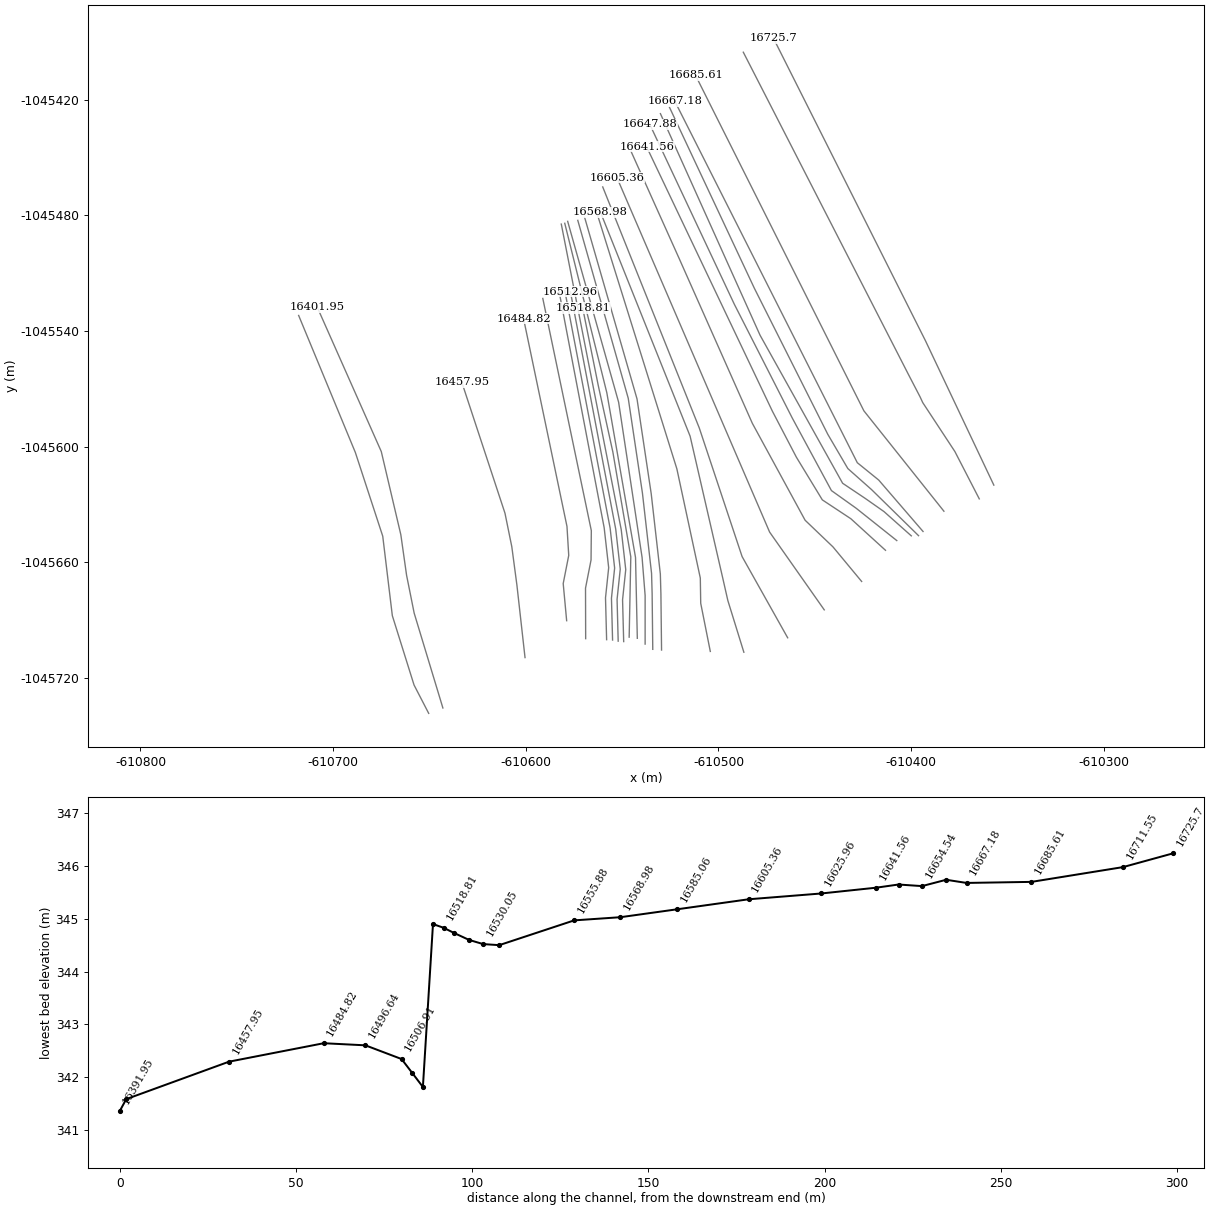
HEC-RAS study PPO_Kvasiny_efektiv.prj: PPO_Kvasiny_efektivita

--- PPO_Kvasiny_efektiv.g04 (geometry) --- (continued)

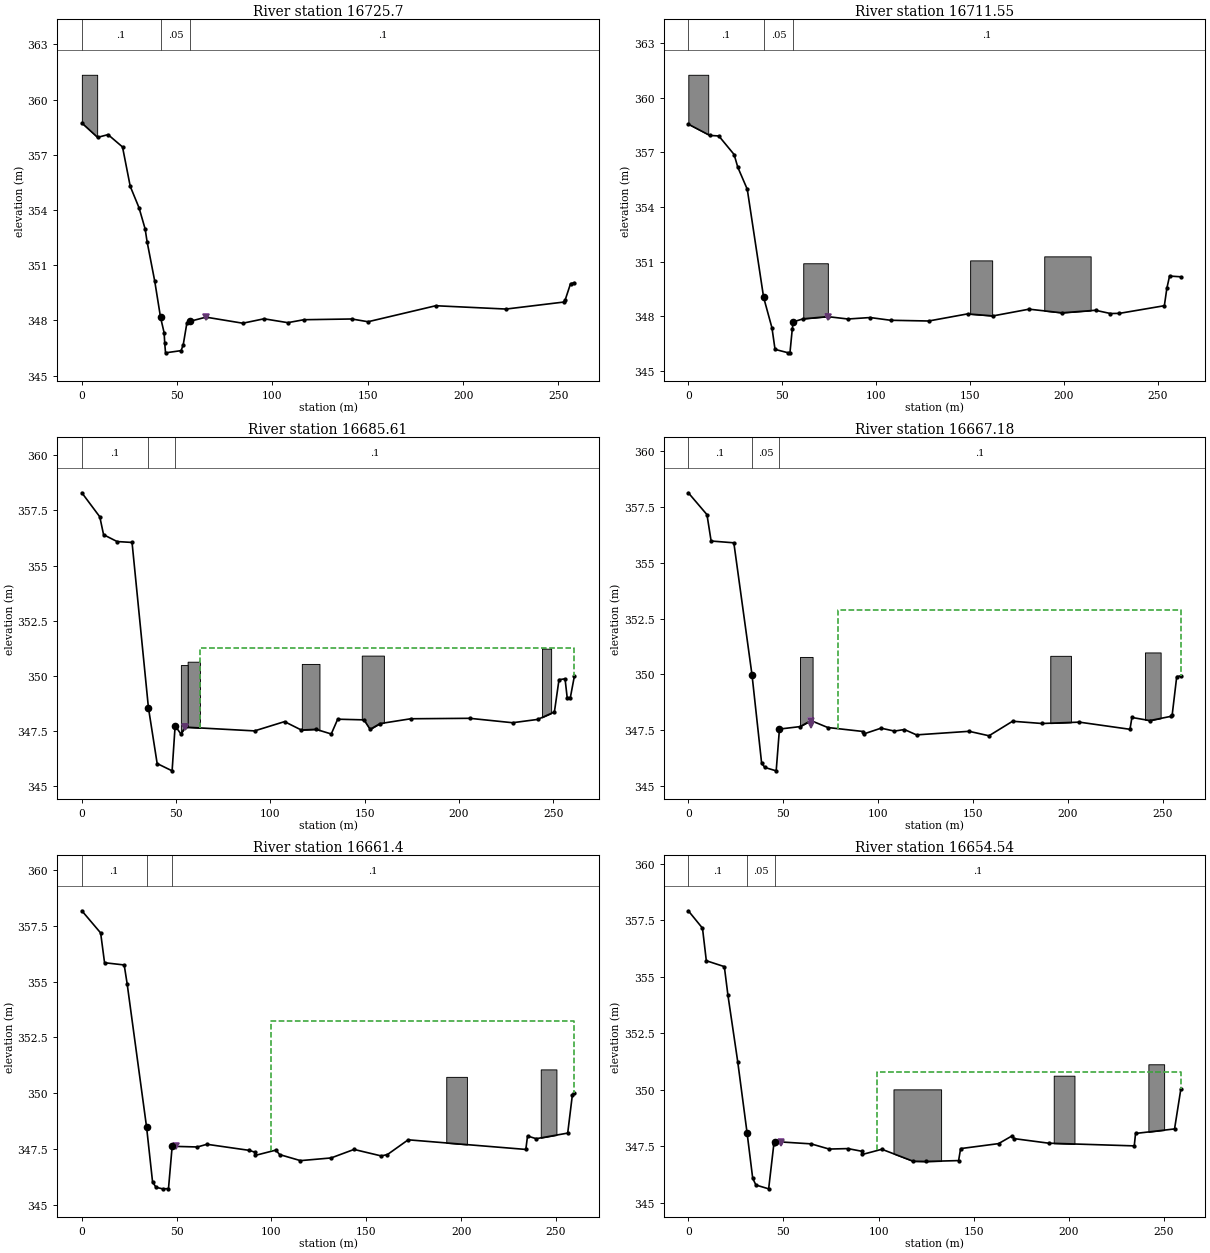
Type RM Length L Ch R = 1 ,16725.7 ,12.99,14.15,15.54
XS GIS Cut Line= 3
-610357.07759999   -1045619.9076    -610392.5535   -1045545.0681
    -610471.4441   -1045388.2447
#Sta/Elev= 30
       0  358.73    8.25  357.95   13.74   358.1   21.33  357.43   25.38  355.29
   29.98  354.13   33.21  352.97   34.21  352.29   38.23  350.14   41.28  348.17
   43.17  347.33   43.48  346.77    43.9  346.24   52.08  346.36   53.19  346.68
   55.07  347.84   56.99  347.96   65.11  348.18   84.43  347.85   95.58  348.09
  108.04  347.88  116.51  348.04   141.6  348.08  150.14  347.93  185.69   348.8
  222.57  348.62  252.83     349  253.56  349.11  256.38     350  258.37  350.05
#Mann= 3 , 0 , 0
       0      .1       0   41.28     .05       0   56.99      .1       0
Levee=0,,,-1,64.95,348.17,,
#Block Obstruct= 1 ,-1
       0    8.03361.3521
Bank Sta=41.28,56.99
XS Rating Curve= 0 ,0
Exp/Cntr=0.5,0.3

Type RM Length L Ch R = 1 ,16711.55,25.25,25.95,28.78
XS GIS Cut Line= 6
-610364.63259999   -1045627.0364    -610377.2875   -1045602.5042
-610393.99859999   -1045577.0942    -610395.3159   -1045574.2261
    -610401.3596   -1045562.6079    -610487.1075   -1045395.4414
#Sta/Elev= 30
       0  358.55   11.42  357.93   16.23   357.9   24.38  356.88   26.34  356.18
   31.38  354.97   40.08  349.03   44.53  347.35   46.16  346.17   53.25  345.98
   54.11  345.99   55.32  347.27   55.84  347.68   61.13  347.85   74.22  347.97
   84.94  347.84   96.79  347.92  107.67  347.77  127.94  347.73  148.62  348.12
  162.19  348.01  181.37  348.38  198.87  348.18  216.75  348.32  224.73  348.14
  229.48  348.15   253.4  348.57  254.72  349.52  256.17   350.2  262.15  350.16
#Mann= 3 , 0 , 0
       0      .1       0   40.08     .05       0   55.84      .1       0
Levee=0,,,-1,74.13,347.97,,
#Block Obstruct= 4 ,-1
   61.17   74.27350.9031  150.01  161.74351.0612  189.46  214.16351.2825
       0    10.6361.2628
Bank Sta=40.08,55.84
XS Rating Curve= 0 ,0
Exp/Cntr=0.3,0.1

Type RM Length L Ch R = 1 ,16685.61,17.06,18.42,16.35
XS GIS Cut Line= 3
-610382.98559999   -1045633.4457-610424.52349999    -1045581.395
-610511.87249999   -1045407.5064
#Sta/Elev= 30
       0   358.3    9.52  357.21   11.52   356.4    18.7  356.09   26.62  356.05
   35.31  348.56   39.94  346.03   47.87   345.7   49.47  347.74   52.52  347.37
   54.79  347.68   91.59  347.51  107.49  347.93   116.4  347.55  124.24  347.58
  132.27  347.37  135.69  348.04  149.62  348.01  152.87  347.58   158.1  347.84
  174.46  348.06  205.73  348.08  228.44  347.88  241.77  348.03  250.63  348.37
  253.06  349.83  256.27  349.87   257.4  349.02  259.08  349.02  261.19  349.98
#Mann= 3 , 0 , 0
       0      .1       0   35.31     .05       0   49.47      .1       0
Levee=0,,,-1,54.77,347.68,,
#XS Ineff= 2 , 0
                           62.53          351.26
Permanent Ineff=
       F       F
#Block Obstruct= 5 ,-1
    56.1   62.64350.6454   52.52    56.1350.4926  148.46  160.19350.9218
  116.67  126.02350.5445  244.02  248.89351.2354
Bank Sta=35.31,49.47
XS Rating Curve= 0 ,0
Exp/Cntr=0.3,0.1

Type RM Length L Ch R = 1 ,16667.18,6.2,5.78,6.81
XS GIS Cut Line= 4
    -610393.8158    -1045643.949-610416.82609999   -1045617.2862
    -610427.9386   -1045608.2904-610522.61459999   -1045420.9473
#Sta/Elev= 30
       0  358.13    9.83  357.15   12.01  355.97   23.98  355.89   33.56  349.97
   38.62  346.02   40.35  345.83   46.29  345.68      48  347.55   58.83  347.66
   64.61  347.93   73.46  347.62   92.26  347.44   92.35  347.33  101.51  347.59
  108.59  347.46  113.83  347.53   120.2  347.29  147.91  347.45  158.38  347.25
   170.8   347.9  186.29   347.8  205.99  347.86  232.66  347.54  233.67  348.07
  243.08  347.93  254.22  348.12  254.91   348.2  257.28   349.9  259.42  349.93
#Mann= 3 , 0 , 0
       0      .1       0   33.56     .05       0      48      .1       0
Levee=0,,,-1,64.79,347.75,,
#XS Ineff= 2 , 0
                           78.98          352.89
Permanent Ineff=
       F       F
#Block Obstruct= 3 ,-1
  240.54   248.8 350.981   58.83   65.46350.7798  190.67  201.55350.8297
Bank Sta=33.56,48
XS Rating Curve= 0 ,0
Exp/Cntr=0.3,0.1

Type RM Length L Ch R = 1 ,16661.4 ,5.64,6.86,5.9
XS GIS Cut Line= 6
    -610396.1494   -1045646.1225-610420.53339999   -1045622.2464
-610432.85249999   -1045611.3244    -610443.2665   -1045593.5444
-610481.36659999   -1045517.8522    -610525.4721   -1045423.9106
#Sta/Elev= 30
       0  358.16    9.91  357.17   11.97  355.84   22.33  355.74   23.87  354.91
   34.13   348.5   37.29  346.05   39.09  345.81   42.58  345.74   45.69  345.75
   47.63  347.64   60.93  347.61   65.96  347.73   88.16  347.46   91.18  347.38
    91.3  347.23  102.31  347.47  104.31  347.27  115.28     347  131.44  347.12
  143.54   347.5  157.87  347.21  161.14  347.27   172.1  347.93  234.14   347.5
  235.04   348.1  239.62  347.98  256.23  348.23  258.71  349.95  259.72  350.01
#Mann= 3 , 0 , 0
       0      .1       0   34.13     .05       0   47.63      .1       0
Levee=0,,,-1,49.48,347.64,,
#XS Ineff= 2 , 0
                            99.6          353.25
Permanent Ineff=
       F       F
#Block Obstruct= 2 ,-1
  242.01  250.28351.0749  192.18  203.07350.7415
Bank Sta=34.13,47.63
XS Rating Curve= 0 ,0
Exp/Cntr=0.3,0.1

Type RM Length L Ch R = 1 ,16654.54,6.93,6.66,6.8
XS GIS Cut Line= 6
     -610399.919   -1045646.2163-610414.10069999   -1045633.6221
    -610423.8823   -1045626.7642    -610435.5652   -1045618.9463
    -610478.4107   -1045542.1985    -610530.1288   -1045427.2973
#Sta/Elev= 30
       0  357.92    7.45  357.15    9.46  355.71   18.93  355.45   20.83  354.18
   25.96  351.25   30.91  348.08   33.84  346.09   35.52  345.79   42.23  345.62
   44.97  347.61   45.65  347.71    64.5  347.61   74.01  347.38   83.87   347.4
   91.33  347.28   91.45  347.14  101.75  347.37  118.19  346.84  124.78  346.83
  142.08  346.87  143.13   347.4  163.07  347.62  170.12  347.96  171.35  347.84
  189.38  347.64  234.41  347.52  235.09  348.07  255.59  348.27  258.87  350.02
#Mann= 3 , 0 , 0
       0      .1       0   30.91     .05       0   45.65      .1       0
Levee=0,,,-1,48.69,347.66,,
#XS Ineff= 2 , 0
                           99.42          350.79
Permanent Ineff=
       F       F
#Block Obstruct= 3 ,-1
  241.83  250.11351.1296  192.08  202.98 350.625  107.84  132.87350.0207
Bank Sta=30.91,45.65
XS Rating Curve= 0 ,0
Exp/Cntr=0.3,0.1

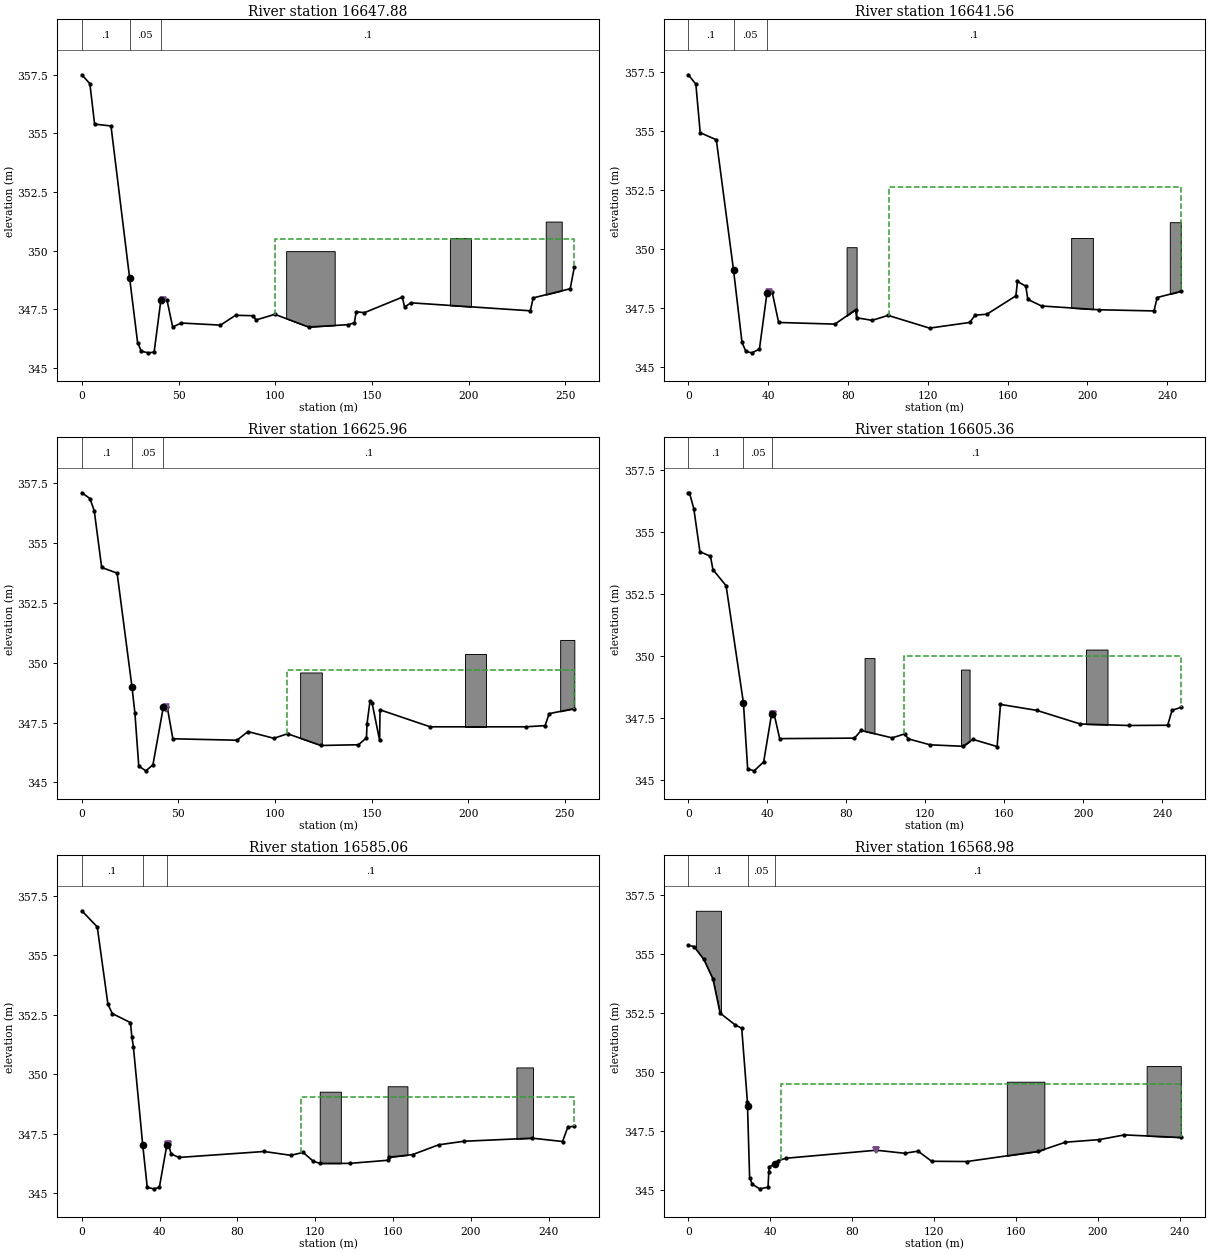
Type RM Length L Ch R = 1 ,16647.88,5.99,6.32,7.53
XS GIS Cut Line= 6
-610407.45239999   -1045648.6625    -610428.5344   -1045631.8985
-610441.36149999   -1045622.7545-610461.68149999   -1045585.1624
    -610491.7806   -1045526.1073-610535.63219999   -1045432.9065
#Sta/Elev= 30
       0  357.49    4.15  357.11    6.59  355.39   15.07  355.31    24.7  348.84
   28.84  346.08   30.75  345.72   34.39  345.65   37.38  345.68   40.85  347.88
   44.05  347.89   46.97  346.75   51.41  346.92   71.69  346.83   79.54  347.25
   88.55  347.23   90.11  347.05   99.78  347.29  117.27  346.75  137.81  346.85
  140.96  346.93  141.89   347.4  146.14  347.36  165.71  348.02  166.93   347.6
  170.19  347.78  231.94  347.44  233.44  347.99  252.59  348.38   254.7  349.31
#Mann= 3 , 0 , 0
       0      .1       0    24.7     .05       0   40.85      .1       0
Levee=0,,,-1,42.02,347.86,,
#XS Ineff= 2 , 0
                          100.12          350.49
Permanent Ineff=
       F       F
#Block Obstruct= 3 ,-1
  239.91  248.18351.2398  190.35  201.24350.5325  105.66  130.77  349.98
Bank Sta=24.7,40.85
XS Rating Curve= 0 ,0
Exp/Cntr=0.3,0.1

Type RM Length L Ch R = 1 ,16641.56,17.07,15.6,12.26
XS GIS Cut Line= 6
-610413.30689999   -1045653.7066-610431.29479999   -1045637.3368
-610446.09189999    -1045627.568    -610459.5562   -1045605.4465
    -610472.0445   -1045581.5282    -610537.3255   -1045444.4423
#Sta/Elev= 30
       0   357.4    3.78     357    5.96  354.94   14.03  354.64   22.68  349.09
    26.9  346.03   28.84  345.65   31.89  345.59   35.63  345.75   39.44  348.15
   42.05  348.16   45.25  346.88   73.49  346.81   83.79  347.42   84.32  347.08
   92.09  346.97   100.1  347.18  120.88  346.64  140.97  346.88  143.73  347.19
  149.61  347.23  164.14  348.01  164.93  348.62  169.11  348.42  170.12  347.86
  176.98  347.58  205.67  347.42  233.34  347.37  234.95  347.94  246.77   348.2
#Mann= 3 , 0 , 0
       0      .1       0   22.68     .05       0   39.44      .1       0
Levee=0,,,-1,40.58,348.11,,
#XS Ineff= 2 , 0
                          100.32          352.63
Permanent Ineff=
       F       F
#Block Obstruct= 3 ,-1
  241.25  246.77351.1385   79.31   84.32350.0773  191.83  202.72350.4694
Bank Sta=22.68,39.44
XS Rating Curve= 0 ,0
Exp/Cntr=0.3,0.1

Type RM Length L Ch R = 1 ,16625.96,21.61,20.6,17.48
XS GIS Cut Line= 6
-610425.68789999   -1045669.8678     -610440.574   -1045651.9392
-610455.03269999   -1045638.1208     -610482.421   -1045587.8698
    -610520.3187      -1045502.6-610545.36879999   -1045446.8765
#Sta/Elev= 30
       0   357.1    4.18  356.86    6.41  356.35   10.26  353.98   18.26  353.74
   25.94  348.99   27.45  347.91   29.46  345.68   33.12  345.48   36.79  345.73
   42.22  348.16   44.24  348.13   47.11  346.82   80.33  346.76   85.96  347.12
   99.43  346.84  106.46  347.03   123.8  346.54   143.2  346.57  147.34  346.86
  147.63  347.45  149.17  348.39  150.21  348.33  154.14  346.76  154.35  348.03
  180.32  347.32  229.76  347.32  239.84  347.37  241.88  347.87  254.94  348.08
#Mann= 3 , 0 , 0
       0      .1       0   25.94     .05       0   42.22      .1       0
Levee=0,,,-1,43.59,348.08,,
#XS Ineff= 2 , 0
                          106.18           349.7
Permanent Ineff=
       F       F
#Block Obstruct= 3 ,-1
  247.62  254.94350.9503  198.32  209.22350.3801     113  124.22349.5901
Bank Sta=25.94,42.22
XS Rating Curve= 0 ,0
Exp/Cntr=0.3,0.1

Type RM Length L Ch R = 1 ,16605.36,21.02,20.3,16.27
XS GIS Cut Line= 3
-610445.09629999   -1045684.5852-610473.44709999   -1045644.2738
-610552.67139999    -1045460.529
#Sta/Elev= 30
       0  356.58     .55  356.59    2.78  355.95    5.88  354.21   11.21  354.03
   12.46  353.49   19.13  352.84   27.91  348.11   30.05  345.45   33.32  345.37
   38.15  345.73   42.18  347.67   43.48  347.65   46.26  346.67   84.14  346.69
   87.53     347  103.21   346.7  109.51  346.86  111.41  346.66  122.47  346.42
  139.16  346.36   144.1  346.64  156.37  346.35  158.08  348.05  176.45  347.81
  198.52  347.26  222.94   347.2  242.73  347.21  244.96  347.81  249.38  347.93
#Mann= 3 , 0 , 0
       0      .1       0   27.91     .05       0   42.18      .1       0
Levee=0,,,-1,42.87,347.61,,
#XS Ineff= 2 , 0
                          108.98          349.99
Permanent Ineff=
       F       F
#Block Obstruct= 3 ,-1
  138.07  142.43349.4565   89.25   94.26349.9202  201.36  212.27350.2634
Bank Sta=27.91,42.18
XS Rating Curve= 0 ,0
Exp/Cntr=0.3,0.1

Type RM Length L Ch R = 1 ,16585.06,17.86,16.08,10.48
XS GIS Cut Line= 4
    -610464.0819   -1045699.0756    -610487.7346   -1045656.9739
    -610509.9596   -1045590.2987    -610560.0797   -1045465.2915
#Sta/Elev= 30
       0  356.87    7.92  356.19   13.39  352.95   15.62  352.55   24.98  352.17
   25.73  351.56   26.49  351.16    31.3  347.03   33.63  345.24   36.97  345.18
   39.85  345.24   43.72  347.03   44.65  347.06   45.84  346.65   49.93   346.5
   93.75  346.75  107.37  346.59  113.82  346.71  118.99  346.34  122.48  346.25
  137.76  346.25  157.18  346.38  158.11  346.51  170.11  346.62  183.44  347.03
  196.43  347.18  231.58  347.31  247.21  347.17  249.92  347.78  253.25  347.81
#Mann= 3 , 0 , 0
       0      .1       0    31.3     .05       0   43.72      .1       0
Levee=0,,,-1,44.45,347.03,,
#XS Ineff= 2 , 0
                          112.59          349.04
Permanent Ineff=
       F       F
#Block Obstruct= 3 ,-1
  122.33  133.19349.2643  157.26  167.42349.4925  223.47  232.02350.2849
Bank Sta=31.3,43.72
XS Rating Curve= 0 ,0
Exp/Cntr=0.3,0.1

Type RM Length L Ch R = 1 ,16568.98,14.3,13.1,11.02
XS GIS Cut Line= 5
    -610486.8255   -1045706.5634-610495.14299999   -1045679.7281
    -610497.7888   -1045668.0863    -610514.7221    -1045594.532
    -610561.2439   -1045478.4149
#Sta/Elev= 28
       0  355.37    2.76  355.32    7.58  354.77   12.03  353.94   15.54  352.49
   22.92  351.99   26.09  351.85   28.89   348.7   28.92  348.54   29.95  345.51
   31.19  345.23   34.85  345.03   38.95   345.1   39.31  345.75   39.49  345.96
   42.33  346.09   43.66  346.22   47.79  346.33   91.89  346.67  105.62  346.54
  112.26  346.63  118.88   346.2  136.17  346.19     171  346.62  184.22  347.01
  200.78  347.12  212.99  347.32   240.6  347.21
#Mann= 3 , 0 , 0
       0      .1       0   28.92     .05       0   42.33      .1       0
Levee=0,,,-1,91.8,346.68,,
#XS Ineff= 2 , 0
                           45.47          349.48
Permanent Ineff=
       F       F
#Block Obstruct= 3 ,-1
    3.69   15.95356.8368  155.62  173.94 349.579  223.92   240.6350.2427
Bank Sta=28.92,42.33
XS Rating Curve= 0 ,0
Exp/Cntr=0.3,0.1

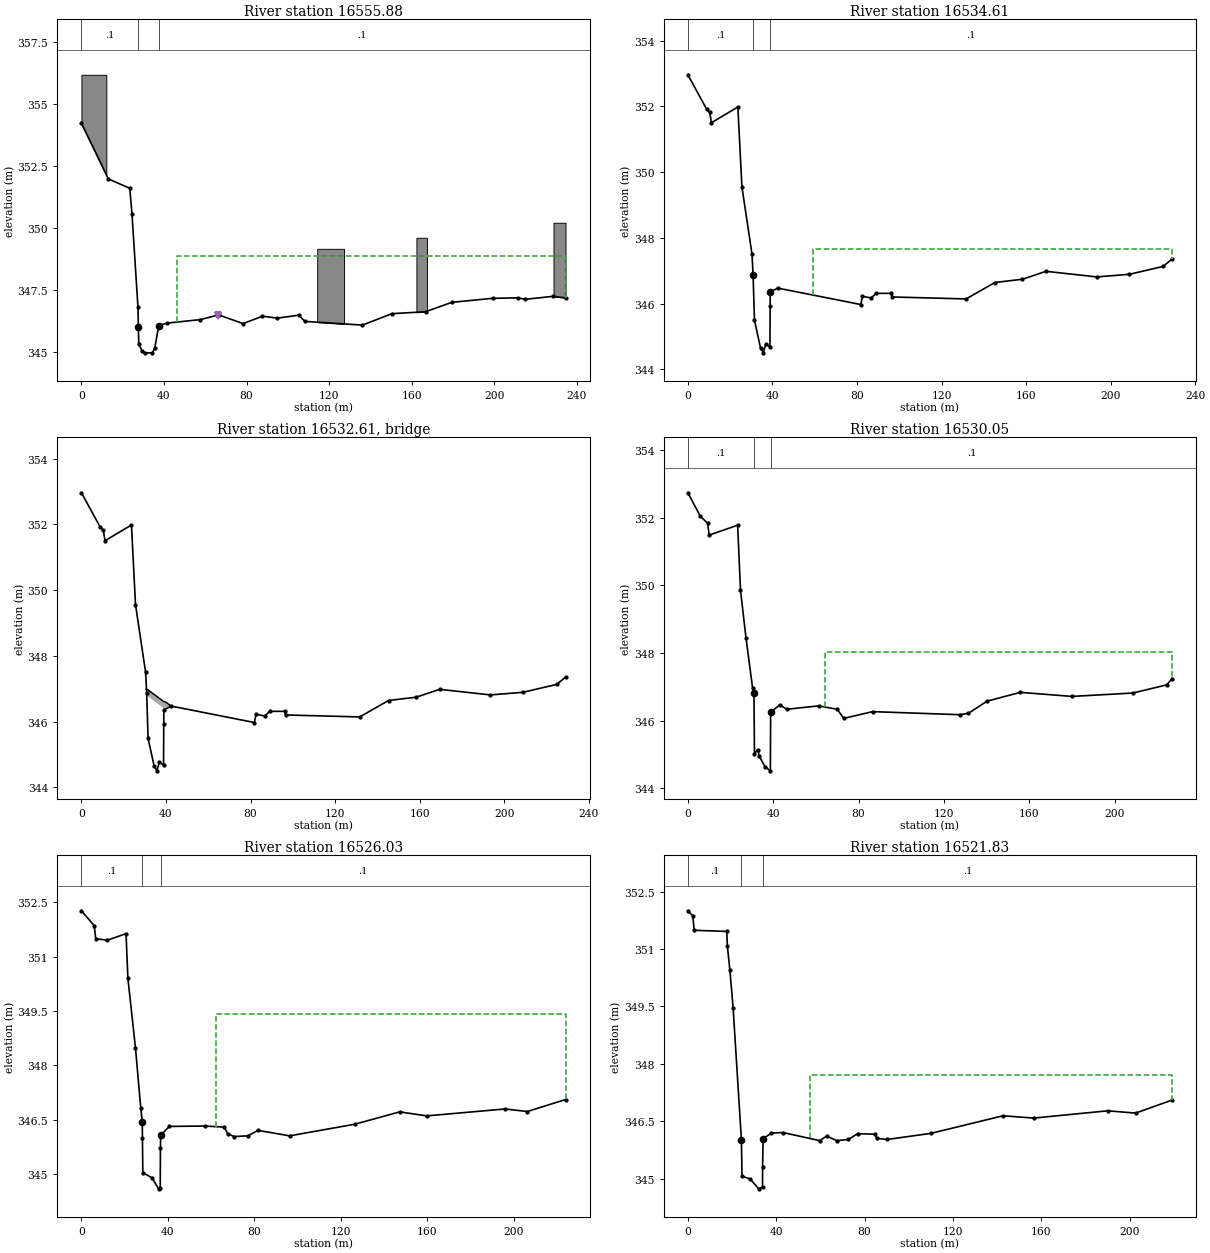
Type RM Length L Ch R = 1 ,16555.88,20.77,21.27,17.9
XS GIS Cut Line= 5
    -610504.2404   -1045706.1507    -610509.2146    -1045681.174
    -610509.4305   -1045668.0863-610521.60139999   -1045611.4654
    -610562.8314   -1045479.6849
#Sta/Elev= 29
       0  354.23   13.02  351.99   23.42  351.61   24.51  350.56   27.39  346.81
    27.6  346.01   27.78  345.31   29.57  345.03   30.58  344.97   34.36  344.97
    35.5  345.15   37.44  346.06   41.43  346.17   57.54  346.31    66.5   346.5
   78.34  346.15   87.71  346.45    94.9  346.37   105.3  346.49  108.23  346.24
  136.11  346.09  150.44  346.55  166.72  346.63  179.56  347.01  199.26  347.17
  211.42  347.19  215.11  347.13  228.36  347.25  234.55  347.19
#Mann= 3 , 0 , 0
       0      .1       0    27.6     .05       0   37.44      .1       0
Levee=0,,,-1,66.11,346.47,,
#XS Ineff= 2 , 0
                           46.19          348.89
Permanent Ineff=
       F       F
#Block Obstruct= 4 ,-1
       0   12.06356.1919  114.23   127.2349.1687  162.31  167.39349.6144
  228.72  234.55350.2217
Bank Sta=27.6,37.44
XS Rating Curve= 0 ,0
Exp/Cntr=0.3,0.1

Type RM Length L Ch R = 1 ,16534.61,4.61,4.56,4.51
XS GIS Cut Line= 6
-610529.54529999   -1045705.4184    -610529.8783    -1045676.323
-610530.17399999   -1045665.9981-610534.91189999   -1045624.3717
-610542.27789999   -1045575.2226-610569.46539999   -1045481.1129
#Sta/Elev= 30
       0  352.96    8.93  351.91   10.36  351.82   11.14   351.5   23.66  351.98
   25.57  349.56   30.35   347.5   30.86  346.87   31.52  345.49   34.38  344.65
   35.72   344.5    36.8  344.76   38.83  344.68   38.94  345.92   38.97  346.35
   42.49  346.47   81.81  345.97    82.6  346.22   86.73  346.17   89.08  346.31
    96.1  346.31   96.62   346.2  131.61  346.14  145.25  346.64  158.29  346.74
  169.44  346.98  193.45  346.81   208.9  346.89  224.82  347.13  228.98  347.35
#Mann= 3 , 0 , 0
       0      .1       0   30.86     .04       0   38.97      .1       0
#XS Ineff= 2 , 0
                           59.32          347.66
Permanent Ineff=
       F       F
Bank Sta=30.86,38.97
XS Rating Curve= 0 ,0
Exp/Cntr=0.5,0.3

Type RM Length L Ch R = 3 ,16532.61,,,
Bridge Culvert--1,0,-1,-1, 0
Deck Dist Width WeirC Skew NumUp NumDn MinLoCord MaxHiCord MaxSubmerge Is_Ogee
1,1.6,1.4,0, 7, 7, , , 0.98, 0, 0,0,,
   30.63   31.33   31.33   38.83   38.83   39.63   42.49
  346.98  346.97  346.97  346.61  346.61   346.6  346.47
  346.78          346.77  346.41
   30.48   31.18   31.18   38.68   38.68   39.48   43.12
  346.98  346.97  346.97  346.61  346.61   346.6  346.47
  346.78          346.77  346.41
BR Coef=-1 , 0 , 0 ,, 0 ,,,0.8,-1,,0,
WSPro=,,,, 1 ,,,, 0 ,,,, 0 ,,,,-1 ,-1 ,-1 , 0 , 0 , 0 , 0 , 0
BC Design=,, 0 ,, 0 ,,,,,,
BC HTab HWMax=347.5
BC HTab TWMax=347.5
BC HTab MaxFlow=80
BC Use User HTab Curves=0
BC User HTab FreeFlow(D)= 0

Type RM Length L Ch R = 1 ,16530.05,3.73,4.02,4.32
XS GIS Cut Line= 6
    -610534.1055   -1045705.0639-610534.43849999   -1045675.9685
    -610534.7342   -1045665.6436    -610539.4721   -1045624.0172
    -610546.8381   -1045574.8681    -610573.0214   -1045482.6369
#Sta/Elev= 30
       0  352.74    5.83  352.05    9.26  351.84   10.02  351.49   23.34  351.78
   24.68  349.86   27.24  348.46   30.35  346.97   30.99  346.81   31.23  345.02
   32.79  345.15   33.46  344.95    36.2  344.64   38.68  344.52   38.82  346.25
   38.85  346.26   43.12  346.47   46.35  346.34   61.25  346.44   70.06  346.34
   73.04  346.07   86.57  346.27  127.43  346.18   131.5  346.22  140.23  346.58
  155.85  346.84  180.01  346.72  208.55  346.82  224.39  347.06   226.9  347.24
#Mann= 3 , 0 , 0
       0      .1       0   30.99     .04       0   38.85      .1       0
#XS Ineff= 2 , 0
                           64.23          348.04
Permanent Ineff=
       F       F
Bank Sta=30.99,38.85
XS Rating Curve= 0 ,0
Exp/Cntr=0.5,0.3

Type RM Length L Ch R = 1 ,16526.03,4.58,4.2,3.62
XS GIS Cut Line= 5
    -610538.0693   -1045702.3362-610538.07229999    -1045677.112
    -610539.6568   -1045657.3569-610551.82759999   -1045576.9234
    -610578.2707   -1045483.1449
#Sta/Elev= 30
       0  352.26     5.9  351.85    6.62  351.49   12.02  351.45   20.62  351.63
   21.48   350.4   24.99  348.48   27.42  346.83   28.14  346.44    28.2     346
   28.39  345.05   32.67   344.9   35.66   344.6   36.43  344.62   36.53  345.72
   36.63  346.08   40.68  346.32   57.07  346.33   66.05   346.3   67.64  346.12
   70.55  346.04   76.88  346.06   81.67  346.21   96.26  346.06  126.39  346.38
  147.15  346.72  159.66  346.61   195.9   346.8  206.17  346.73  223.83  347.06
#Mann= 3 , 0 , 0
       0      .1       0   28.14     .04       0   36.63      .1       0
#XS Ineff= 2 , 0
                           62.36          349.41
Permanent Ineff=
       F       F
Bank Sta=28.14,36.63
XS Rating Curve= 0 ,0
Exp/Cntr=0.3,0.1

Type RM Length L Ch R = 1 ,16521.83,3.27,3.02,2.37
XS GIS Cut Line= 4
    -610542.1235   -1045699.3356    -610543.0548   -1045657.4255
    -610557.9562   -1045571.9967    -610579.7877   -1045484.1398
#Sta/Elev= 30
       0     352    2.23  351.87    2.87  351.49   17.63  351.46   17.91  351.07
   19.03  350.45    20.5  349.46   24.26  346.01   24.53  345.06   28.17  344.99
    32.1  344.73   33.81  344.78   33.85   345.3   34.06  346.04   37.87  346.19
   43.23   346.2    59.7  345.99   62.86  346.11   67.39  345.99   72.66  346.02
   76.82  346.17   84.53  346.16   85.58  346.05   90.13  346.02  110.02  346.18
   142.7  346.64  156.61  346.58   190.1  346.77  202.73  346.71  219.17  347.05
#Mann= 3 , 0 , 0
       0      .1       0   24.26     .04       0   34.06      .1       0
#XS Ineff= 2 , 0
                           55.28           347.7
Permanent Ineff=
       F       F
Bank Sta=24.26,34.06
XS Rating Curve= 0 ,0
Exp/Cntr=0.3,0.1

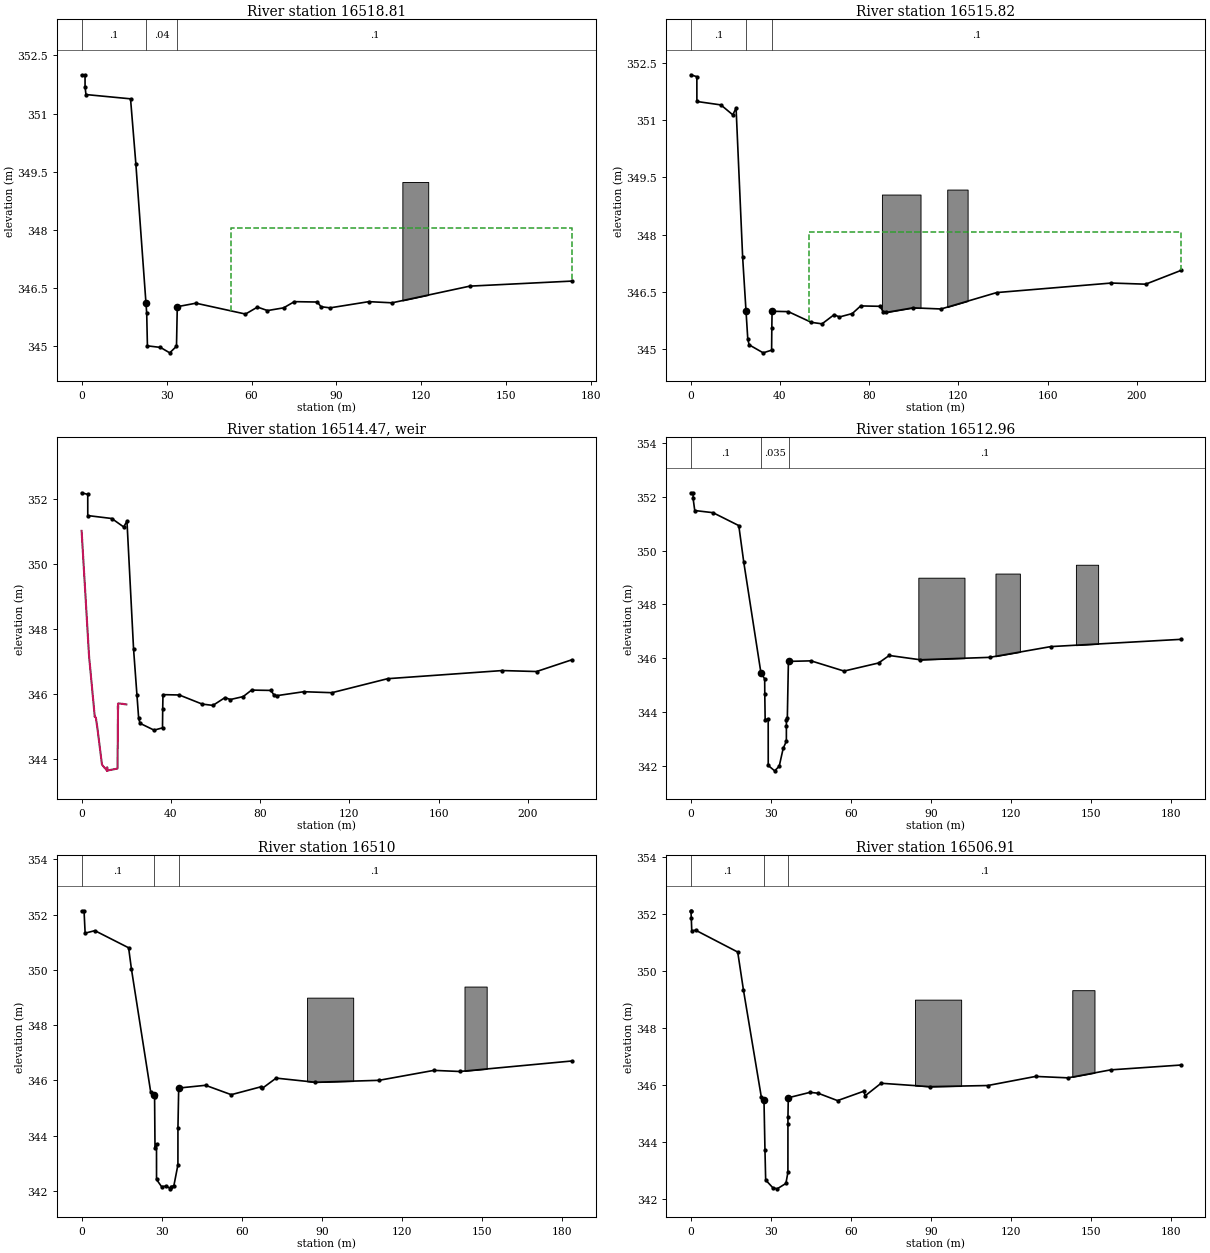
Type RM Length L Ch R = 1 ,16518.81,3.46,2.99,2.85
XS GIS Cut Line= 5
    -610546.3568   -1045698.7429    -610545.5101   -1045657.0869
    -610554.8235   -1045602.7307    -610562.3588   -1045568.4407
    -610570.4869   -1045528.0546
#Sta/Elev= 26
       0  351.99    1.21     352    1.22  351.69    1.53  351.49   17.28  351.38
   19.15  349.71   22.73346.1114   22.99  345.85   23.24  345.01   27.84  344.97
   31.12  344.83   33.51     345   33.79  346.02   40.37  346.11   57.88  345.83
   62.11  346.01   65.65  345.92   71.34  345.99   75.14  346.15   83.28  346.14
   84.52  346.02   87.74  345.99  101.44  346.15  109.64  346.12   137.1  346.55
  173.12  346.68
#Mann= 3 , 0 , 0
       0      .1       0   22.73     .04       0   33.79      .1       0
#XS Ineff= 2 , 0
                           52.69          348.06
Permanent Ineff=
       F       F
#Block Obstruct= 1 ,-1
  113.28  122.41349.2358
Bank Sta=22.73,33.79
XS Rating Curve= 0 ,0
Exp/Cntr=0.3,0.1

Type RM Length L Ch R = 1 ,16515.82,2.86,2.86,2.83
XS GIS Cut Line= 5
    -610549.2021   -1045701.0436    -610549.7798   -1045679.3474
    -610548.1328   -1045663.7179    -610550.4721   -1045643.0045
    -610581.5868   -1045484.5631
#Sta/Elev= 30
       0  352.19    2.75  352.14    2.76  351.49   13.52   351.4   18.86  351.14
   20.33  351.32   23.28   347.4   24.79  345.99   25.58  345.26   26.18  345.11
   32.48   344.9   36.26  344.97   36.35  345.55   36.47  345.99   43.76  345.98
   54.05   345.7   58.86  345.66   64.28   345.9   66.66  345.84   72.41  345.93
   76.19  346.13   84.83  346.12   86.33  345.97   87.61  345.96   99.59  346.08
  112.21  346.05  137.16  346.48  188.56  346.73  203.93   346.7  219.73  347.06
#Mann= 3 , 0 , 0
       0      .1       0   24.79    .035       0   36.47      .1       0
#XS Ineff= 2 , 0
                           52.83          348.06
Permanent Ineff=
       F       F
#Block Obstruct= 2 ,-1
  114.98  124.12349.1804   85.71  103.01  349.05
Bank Sta=24.79,36.47
XS Rating Curve= 0 ,0
Exp/Cntr=0.3,0.1

Type RM Length L Ch R = 5 ,16514.47,,,
IW Pilot Flow=0
#Inline Weir SE= 24
       0  351.02    3.33  347.18    5.83  345.36    5.84  345.34    5.85  345.33
    5.88  345.31     5.9  345.31    5.91  345.31    5.92  345.32    6.39  345.28
     7.1  344.95    9.13  343.84   11.46  343.65   11.47  343.76   11.48  343.65
   11.55  343.66   16.09  343.72   16.23  344.83   16.31  345.64   16.31  345.66
   16.31  345.53   16.32  345.72   18.08  345.71   20.06  345.69
IW Dist,WD,Coef,Skew,MaxSub,Min_El,Is_Ogee,SpillHt,DesHd
0.5,0.5,1.4,0,0.98,, 0 ,,,0,0,
Inline Weir Flap Gates= 0

Type RM Length L Ch R = 1 ,16512.96,2.96,2.96,2.85
XS GIS Cut Line= 5
    -610552.0539   -1045700.8215    -610552.6316   -1045679.1253
    -610550.9846   -1045663.4958-610553.32389999   -1045642.7824
    -610576.8487   -1045519.6843
#Sta/Elev= 30
       0  352.15     .88  352.14     .89  351.94    1.51  351.49    8.34  351.41
      18  350.93   19.85  349.58    26.3  345.45    27.7  345.23   27.74  344.65
   27.88   343.7   29.02  343.75   29.03  342.01   31.43  341.81   33.14  341.98
   34.64  342.65   35.82  342.91   35.83  343.49   35.84   343.7   36.18  343.77
   36.59  345.89   36.64  345.88   45.06   345.9   57.42  345.52   70.34  345.82
   74.35   346.1   85.98  345.94  111.96  346.03  134.86  346.43  183.59   346.7
#Mann= 3 , 0 , 0
       0      .1       0    26.3    .035       0   36.64      .1       0
#Block Obstruct= 3 ,-1
  114.14  123.28349.1454   85.25  102.53348.9921  144.27  152.58349.4734
Bank Sta=26.3,36.64
XS Rating Curve= 0 ,0
Exp/Cntr=0.3,0.1

Type RM Length L Ch R = 1 ,16510   ,3.1,3.09,3.07
XS GIS Cut Line= 5
    -610554.9674   -1045700.2362    -610555.5451     -1045678.54
    -610553.8981   -1045662.9105-610556.23739999   -1045642.1971
    -610579.7622    -1045519.099
#Sta/Elev= 30
       0  352.13     .91  352.14    1.32  351.33    4.96  351.42    17.6   350.8
   18.66  350.03   25.87  345.58   27.05  345.46   27.33  345.41   27.49  343.54
   28.05   343.7   28.06  342.41   29.93  342.15   31.79  342.17   33.22  342.07
   33.41  342.15   34.55  342.18   36.07  342.94   36.08  344.27   36.36  345.72
   46.41  345.82   56.04  345.48   67.35  345.77   67.67  345.71   72.86  346.08
   87.49  345.93   111.4     346  131.93  346.36  141.61  346.32  183.59   346.7
#Mann= 3 , 0 , 0
       0      .1       0   27.05    .035       0   36.36      .1       0
#Block Obstruct= 2 ,-1
   84.43  101.71348.9938   143.4  151.71349.3952
Bank Sta=27.05,36.36
XS Rating Curve= 0 ,0
Exp/Cntr=0.3,0.1

Type RM Length L Ch R = 1 ,16506.91,10.74,10.26,7.39
XS GIS Cut Line= 5
    -610558.0583   -1045700.0491     -610558.636   -1045678.3529
     -610556.989   -1045662.7234-610559.32829999     -1045642.01
    -610582.8531   -1045518.9119
#Sta/Elev= 30
       0  352.11     .08  352.11     .22  351.84     .39   351.4    1.79  351.43
    17.6  350.66   19.74  349.33   26.45  345.56   27.44  345.45   27.81  343.69
   28.07  342.65   30.74  342.38   32.37  342.34   35.65  342.53    36.4  342.92
   36.41  344.61   36.42  344.87   36.54  345.54   44.67  345.73    47.7   345.7
   54.99  345.44   64.81  345.77   65.35  345.61    71.3  346.05    89.6  345.93
  111.25  345.97  129.19  346.29   141.3  346.24  157.27  346.52  183.59  346.69
#Mann= 3 , 0 , 0
       0      .1       0   27.44    .035       0   36.54      .1       0
#Block Obstruct= 2 ,-1
      84  101.28348.9877  142.91  151.22349.3203
Bank Sta=27.44,36.54
XS Rating Curve= 0 ,0
Exp/Cntr=0.3,0.1

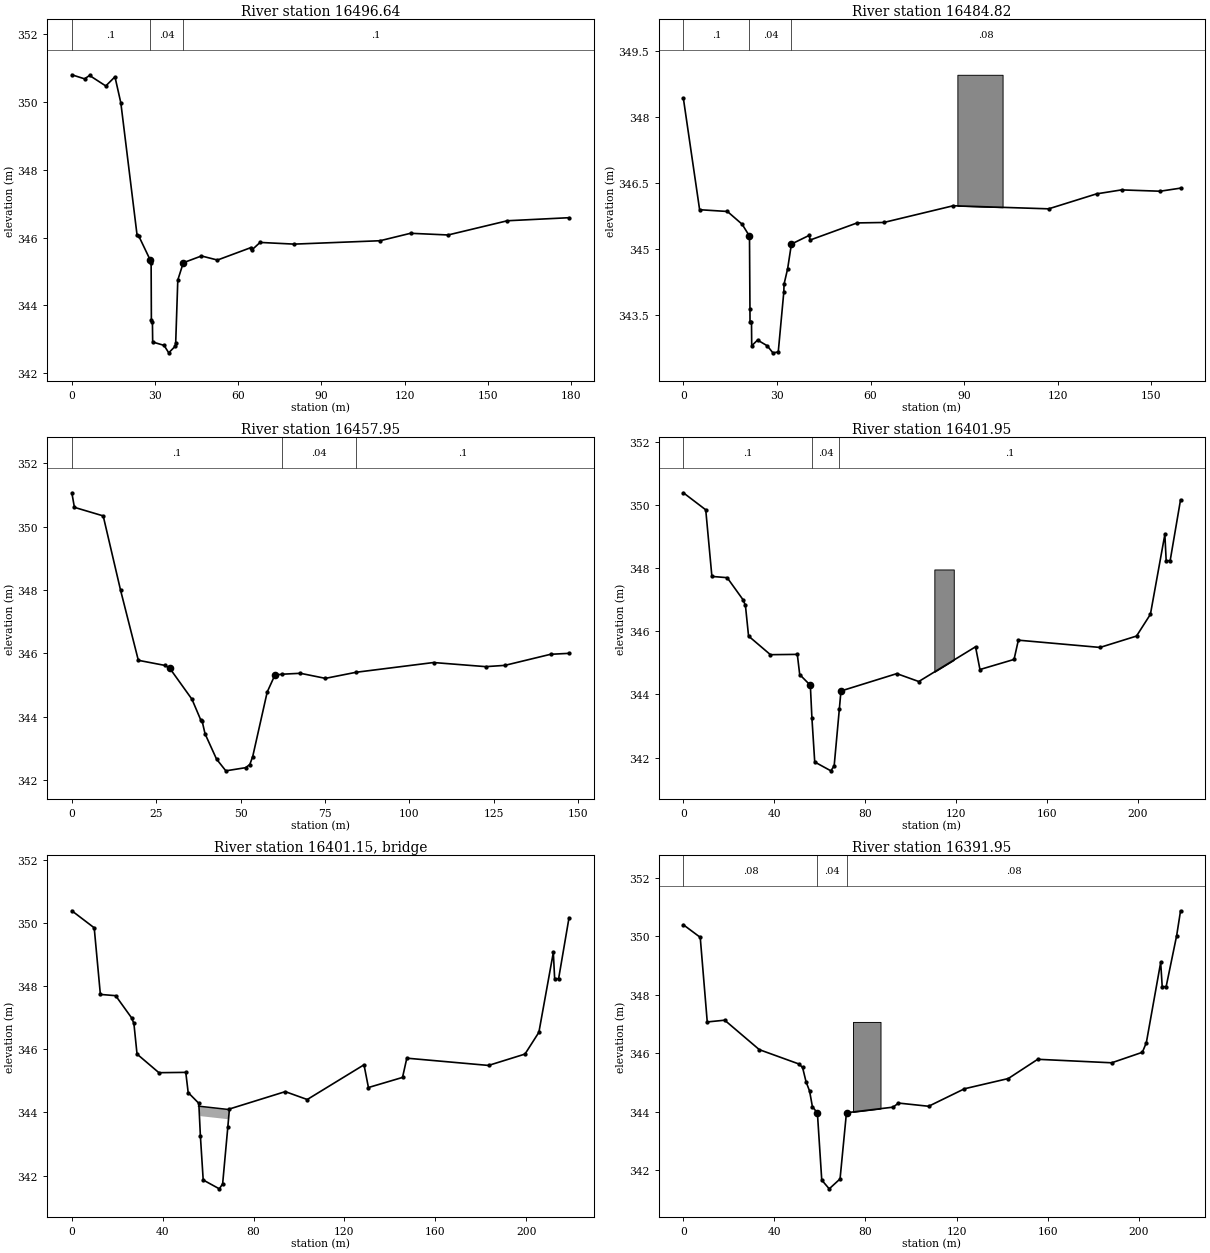
Type RM Length L Ch R = 1 ,16496.64,11.84,11.82,12.2
XS GIS Cut Line= 5
-610568.93389999   -1045699.5274-610569.01029999   -1045673.3139
    -610566.1424   -1045658.7355    -610566.0002   -1045643.5141
    -610591.1844   -1045523.1212
#Sta/Elev= 30
       0  350.81    4.59  350.69    6.39  350.79   12.24  350.48   15.55  350.75
   17.67  349.98   23.53  346.07   24.13  346.05   28.27  345.34   28.59  345.26
   28.68  343.56   29.06  343.51   29.15  342.92   33.26  342.82   34.94   342.6
   37.33   342.8   37.45  342.89   38.21  344.75   40.19  345.26   46.74  345.46
   52.51  345.34   64.67  345.71   64.94  345.64   67.88  345.86   80.18  345.81
  111.15  345.91  122.14  346.13  135.67  346.08  157.06   346.5  179.29  346.59
#Mann= 3 , 0 , 0
       0      .1       0   28.27     .04       0   40.19      .1       0
Bank Sta=28.27,40.19
XS Rating Curve= 0 ,0
Exp/Cntr=0.3,0.1

Type RM Length L Ch R = 1 ,16484.82,24.61,26.87,29.73
XS GIS Cut Line= 5
    -610578.8018   -1045690.2112    -610580.5927   -1045670.9478
    -610577.7248   -1045656.3694    -610578.6325   -1045641.3372
    -610601.1836   -1045533.5318
#Sta/Elev= 27
       0  348.42    5.21  345.89   14.12  345.85   18.84  345.56    21.2  345.29
   21.35  343.63   21.37  343.33   21.84  343.35   21.91   342.8   23.79  342.93
   26.89   342.8   28.71  342.64   30.42  342.66    32.2  344.02   32.28   344.2
   33.43  344.55   34.64  345.11   40.42  345.31   40.58   345.2    55.7  345.59
   64.24   345.6   86.53  345.98  117.11  345.91  132.48  346.25  140.48  346.34
  152.86  346.31   159.4  346.38
#Mann= 3 , 0 , 0
       0      .1       0    21.2     .04       0   34.64     .08       0
#Block Obstruct= 1 ,-1
   87.85  102.34 348.954
Bank Sta=21.2,34.64
XS Rating Curve= 0 ,0
Exp/Cntr=0.3,0.1

Type RM Length L Ch R = 1 ,16457.95,27.86,29.15,31.23
XS GIS Cut Line= 5
    -610600.4112   -1045709.3366    -610604.6319   -1045671.6896
    -610607.2707   -1045651.8644-610610.81619999   -1045634.4717
     -610633.272   -1045566.4278
#Sta/Elev= 27
       0  351.07     .76  350.61    9.29  350.34   14.42     348    19.7  345.78
   27.53  345.62      29  345.53   35.59  344.55   38.18   343.9   38.58  343.87
   39.46  343.46   42.87  342.66   45.62  342.29   51.48  342.39   52.72  342.49
   53.58  342.74   57.88  344.78   60.14  345.31   62.13345.3404   67.71  345.37
   75.12  345.21   84.25 345.403  107.15  345.71  122.62  345.58  128.27  345.62
  141.83  345.97  147.29     346
#Mann= 3 ,-1 , 0
       0      .1       0   62.13     .04       0   84.25      .1       0
Bank Sta=29,60.14
XS Rating Curve= 0 ,0
Exp/Cntr=0.3,0.1

Type RM Length L Ch R = 1 ,16401.95,1.88,1.88,1.88
XS GIS Cut Line= 6
    -610643.0462   -1045735.4757    -610657.9483   -1045686.2902
-610661.88529999   -1045666.6815-610664.87119999    -1045645.638
-610675.02239999   -1045602.4955-610708.26749999   -1045527.6306
#Sta/Elev= 30
       0  350.39    9.85  349.85   12.56  347.74   19.29   347.7   26.28     347
   27.32  346.82    28.7  345.85   38.33  345.26   50.16  345.27   51.22  344.63
    55.9  344.29   56.59343.2583   57.83  341.86   64.94  341.58   66.39  341.74
   68.65343.5249   69.38  344.11   93.96  344.66  103.63  344.41  128.62  345.51
  130.57  344.79  145.58  345.11  147.47  345.72  183.43  345.49  199.49  345.85
  205.61  346.54  211.97  349.07  212.55  348.24   214.3  348.24  218.88  350.17
#Mann= 3 ,-1 , 0
       0      .1       0   56.59     .04       0   68.65      .1       0
#Block Obstruct= 1 ,-1
  110.49  119.04347.9603
Bank Sta=55.9,69.38
XS Rating Curve= 0 ,0
Exp/Cntr=0.5,0.3

Type RM Length L Ch R = 3 ,16401.15,,,
BEGIN DESCRIPTION:
16595.9  PF 211 ŽELEZNÁ LÁVKA PRO PÌŠÍ V
END DESCRIPTION:
Bridge Culvert--1,0,-1,-1, 0
Deck Dist Width WeirC Skew NumUp NumDn MinLoCord MaxHiCord MaxSubmerge Is_Ogee
0.5,1.3,1.4,0, 2, 2, , , 0.98, 0, 0,0,,
    55.8   69.52
   344.2  344.09
  343.89  343.78
    55.8   69.52
   344.2  344.09
  343.89  343.78
BR Coef=-1 , 0 , 0 ,, 0 ,,,0.8,-1,,0,
WSPro=,,,, 1 ,,,, 0 ,,,, 0 ,,,,-1 ,-1 ,-1 , 0 , 0 , 0 , 0 , 0
BC Design=,, 0 ,, 0 ,,,,,,
BC HTab HWMax=345.1
BC HTab TWMax=345
BC HTab MaxFlow=80
BC Use User HTab Curves=0
BC User HTab FreeFlow(D)= 0

Type RM Length L Ch R = 1 ,16391.95,18.23,18.4,18.11
XS GIS Cut Line= 6
    -610650.4058   -1045738.2674    -610658.0192   -1045723.5482
     -610669.287   -1045687.5937     -610674.261   -1045646.3993
    -610688.4727    -1045603.003-610717.91099999   -1045531.9448
#Sta/Elev= 30
       0   350.4    7.41  349.97   10.49  347.07   18.16  347.13   33.37  346.12
   50.73  345.63   52.36  345.51   53.89  345.02   55.45   344.7   56.67  344.17
   58.88343.9468   60.79  341.65   64.07  341.35   68.83  341.69   71.64  343.96
   71.91  343.96   92.16  344.15   94.48  344.29  107.73  344.18  123.49  344.78
  142.72  345.13  155.66  345.79  188.15  345.67  201.62  346.03  203.37  346.36
  209.67  349.11  210.34  348.28  212.07  348.28  216.69  350.03   218.4  350.88
#Mann= 3 ,-1 , 0
       0     .08       0   58.88     .04       0   71.91     .08       0
#Block Obstruct= 1 ,-1
   74.51    86.6347.0706
Bank Sta=58.88,71.91
XS Rating Curve= 0 ,0
Exp/Cntr=0.3,0.1