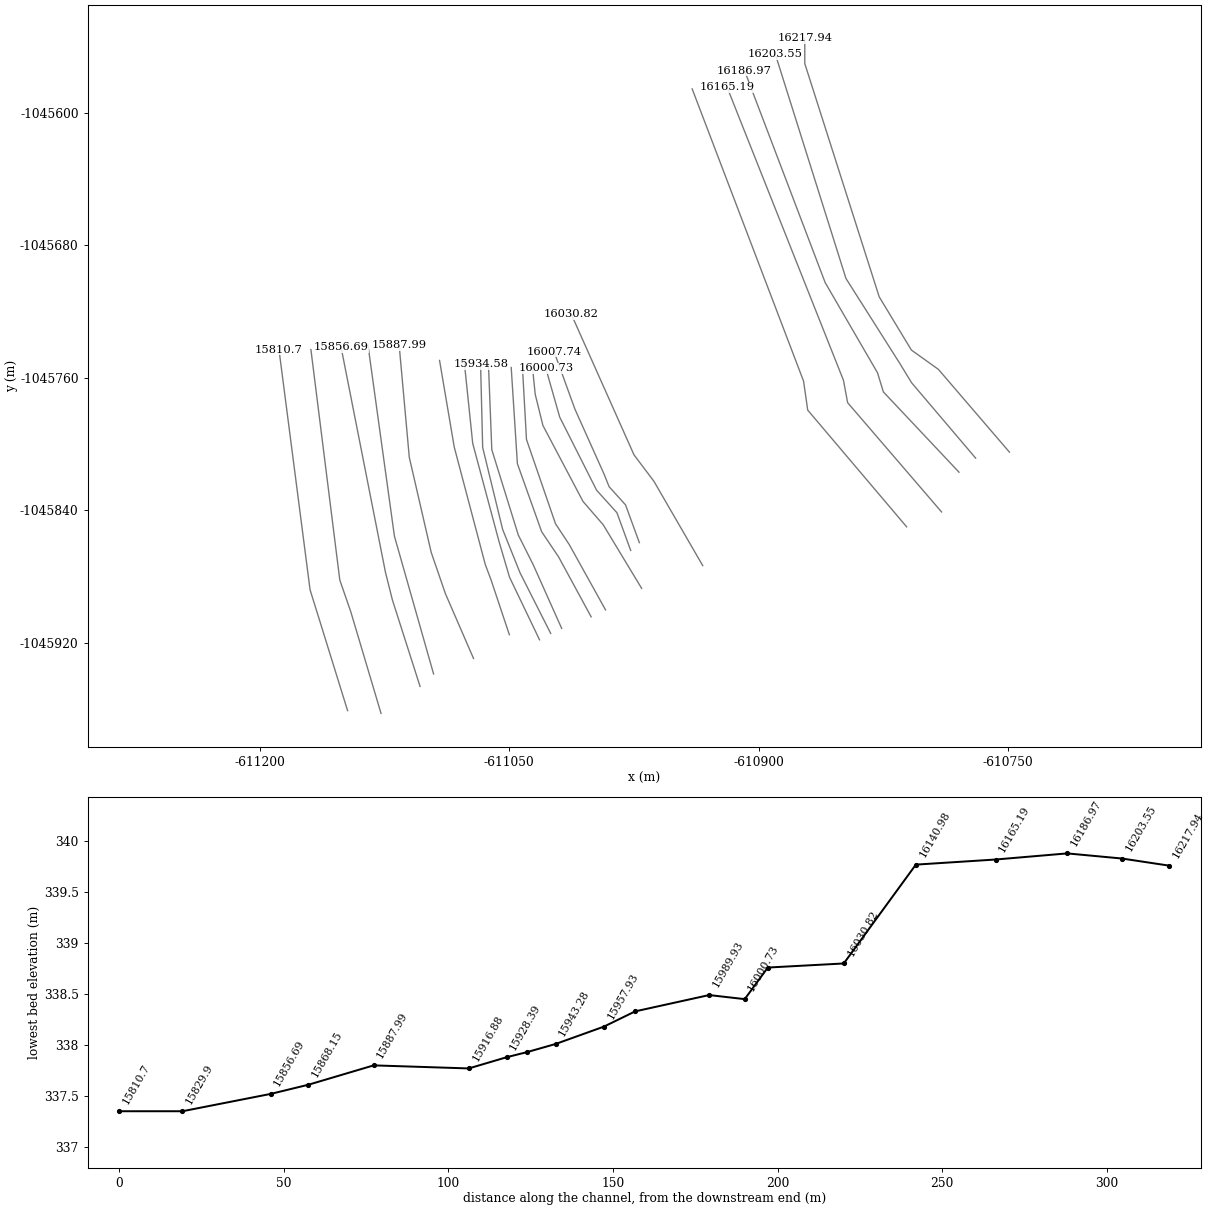
HEC-RAS study PPO_Kvasiny_efektiv.prj: PPO_Kvasiny_efektivita

--- PPO_Kvasiny_efektiv.g04 (geometry) --- (continued)

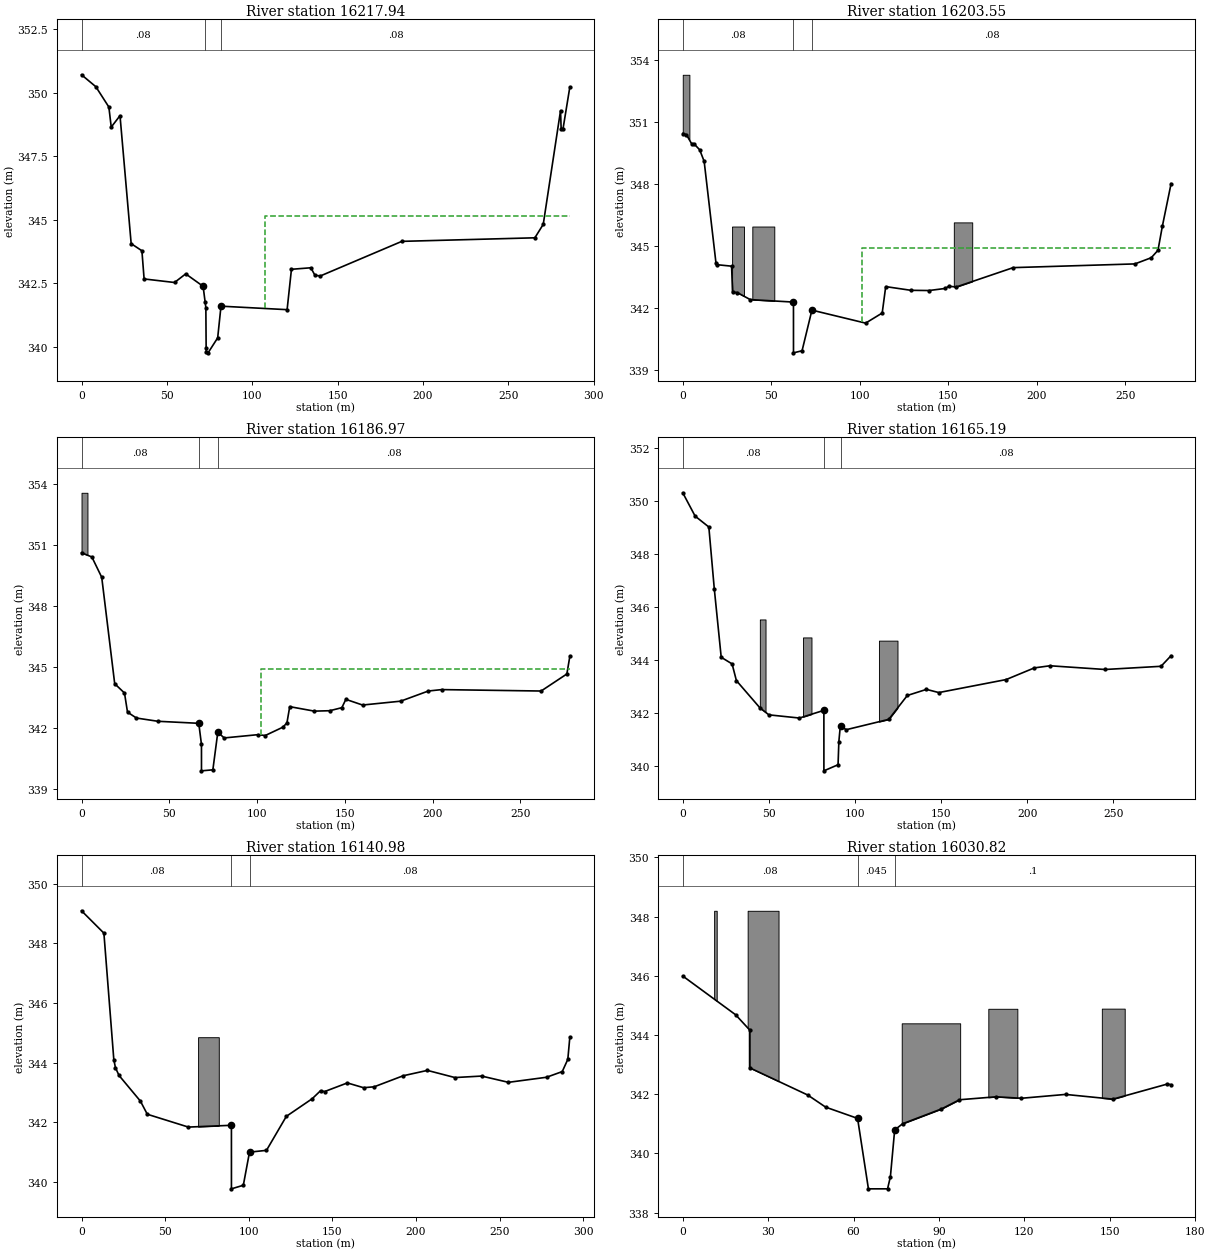
Type RM Length L Ch R = 1 ,16217.94,17.82,14.38,10.85
XS GIS Cut Line= 6
    -610749.3409   -1045804.8633    -610792.0326   -1045754.9198
    -610808.2784   -1045743.2547    -610827.6222   -1045711.1307
    -610872.3427   -1045570.3783    -610872.3427   -1045555.1515
#Sta/Elev= 30
       0  350.71    8.39  350.24   16.02  349.44   17.41  348.65   22.55   349.1
   29.09  344.06   35.38  343.78   36.67  342.67   54.49  342.53   61.05  342.87
   71.24  342.38   72.44341.7539   72.85  341.54   73.02  339.95    73.1  339.81
   74.14  339.76   79.78  340.35   81.72341.5977  120.46  341.46     123  343.05
  134.37  343.11  136.79  342.81  140.02  342.79  187.68  344.15  265.62  344.29
  270.54  344.82  280.67   349.3  281.02  348.59  282.12  348.58  286.12  350.23
#Mann= 3 ,-1 , 0
       0     .08       0   72.44     .04       0   81.72     .08       0
#XS Ineff= 2 , 0
                          107.39          345.13
Permanent Ineff=
       F       F
Bank Sta=71.24,81.72
XS Rating Curve= 0 ,0
Exp/Cntr=0.3,0.1

Type RM Length L Ch R = 1 ,16203.55,16.98,16.59,13.12
XS GIS Cut Line= 5
    -610769.6559   -1045808.4823    -610808.1264   -1045763.0171
    -610815.1211   -1045751.5259    -610847.5962   -1045700.0653
    -610890.0638   -1045564.6689
#Sta/Elev= 30
       0  350.46    2.07   350.4    4.97  349.97    6.36  349.96    9.56  349.67
   12.09  349.11   18.75  344.19   19.58   344.1   27.59  344.03    28.1  342.77
   30.81  342.75   38.12  342.41   62.52  342.29   62.53  339.83   67.37  339.93
   72.94   341.9  103.27  341.27  112.63  341.76  114.61  343.04  128.88  342.86
  139.06  342.85  148.15  342.95  150.27  343.06  154.36  343.02  186.61  343.96
  255.33  344.14  264.57  344.44  268.36   344.8  270.82  345.96  275.76  348.03
#Mann= 3 , 0 , 0
       0     .08       0   62.52     .04       0   72.94     .08       0
#XS Ineff= 2 , 0
                          101.15          344.89
Permanent Ineff=
       F       F
#Block Obstruct= 4 ,-1
  153.07  163.46346.1526       0    3.74353.3066   27.86   34.56 345.952
   39.28   51.69 345.952
Bank Sta=62.52,72.94
XS Rating Curve= 0 ,0
Exp/Cntr=0.3,0.1

Type RM Length L Ch R = 1 ,16186.97,23.06,21.77,16.29
XS GIS Cut Line= 5
    -610779.6482   -1045816.9759    -610825.1134   -1045768.5129
    -610828.6108   -1045757.0217-610860.08659999   -1045702.5634
    -610908.5496   -1045574.6612
#Sta/Elev= 30
       0  350.62    5.89  350.41   11.51  349.41    18.9  344.17   24.48  343.71
   26.19  342.77   31.27  342.48   43.49  342.32   66.78  342.22   68.32  341.18
   68.33  339.88   74.81  339.93   77.62  341.78   81.26   341.5  100.37  341.66
  104.66  341.62   114.7  342.03     117  342.24  118.59  343.04   132.6  342.82
  141.36  342.84  148.28  342.99  150.56   343.4  160.08  343.12  181.77  343.31
  197.52  343.81  205.12  343.88  261.78  343.81  276.45  344.65  278.14  345.52
#Mann= 3 , 0 , 0
       0     .08       0   66.78     .04       0   77.62     .08       0
#XS Ineff= 2 , 0
                          102.02          344.89
Permanent Ineff=
       F       F
#Block Obstruct= 1 ,-1
       0    3.38 353.571
Bank Sta=66.78,77.62
XS Rating Curve= 0 ,0
Exp/Cntr=0.3,0.1

Type RM Length L Ch R = 1 ,16165.19,23.88,24.21,22.28
XS GIS Cut Line= 4
    -610790.1402   -1045840.9575-610846.59699999    -1045775.008
    -610849.0951   -1045761.5183-610919.04149999   -1045584.6535
#Sta/Elev= 27
       0   350.3    7.18  349.42   15.14  349.01   18.29  346.69   22.32   344.1
   28.64  343.85   31.14  343.22   44.85  342.19   50.01  341.93   67.73  341.81
   81.92   342.1   81.93  339.82   90.15  340.05   90.61  340.92   91.47  341.52
   91.57  341.52   94.87  341.37  119.58  341.76  130.35  342.66  141.45  342.89
  148.64  342.77  187.72  343.26  204.08   343.7  213.17  343.78  245.14  343.64
  277.62  343.76  283.46  344.16
#Mann= 3 , 0 , 0
       0     .08       0   81.92     .04       0   91.57     .08       0
#Block Obstruct= 3 ,-1
   44.75   48.05345.5259   69.81   74.72344.8481  113.88  124.65344.7277
Bank Sta=81.92,91.57
XS Rating Curve= 0 ,0
Exp/Cntr=0.3,0.1

Type RM Length L Ch R = 1 ,16140.98,20.09,21.91,20.25
XS GIS Cut Line= 4
    -610811.1241   -1045849.9506    -610870.5786   -1045779.5045
-610873.07669999   -1045762.0179    -610940.0255   -1045585.6527
#Sta/Elev= 29
       0  349.09   13.38  348.34   19.31   344.1   20.29  343.83   22.43  343.57
   35.21  342.71   39.32  342.27   63.88  341.84   89.62   341.9   89.63  339.77
   96.74  339.89  100.43     341  110.58  341.06  122.46   342.2   137.9  342.79
  142.93  343.06  145.31  343.03  158.93  343.32  168.61  343.16  174.96  343.19
  192.29  343.56  206.78  343.74  223.24   343.5   239.2  343.55  255.24  343.34
  278.02  343.51   287.4   343.7  290.74  344.11  291.95  344.86
#Mann= 3 , 0 , 0
       0     .08       0   89.62     .04       0  100.43     .08       0
#Block Obstruct= 1 ,-1
   69.69   82.07344.8526
Bank Sta=89.62,100.43
XS Rating Curve= 0 ,0
Exp/Cntr=0.3,0.1

Type RM Length L Ch R = 1 ,16030.82,23.32,23.08,22.14
XS GIS Cut Line= 4
-610933.67859999    -1045873.336    -610963.0078   -1045822.4717
-610974.99879999   -1045806.4839-611012.67509999   -1045721.6095
#Sta/Elev= 20
       0  345.99   18.59  344.68   23.48  344.17   23.49  342.89    43.9  341.97
   50.21  341.56   61.42  341.18   65.23   338.8   71.95   338.8   72.95  339.21
   74.45  340.79   77.25     341    90.9   341.5   97.22  341.81  110.09  341.91
  118.98  341.86  134.47  341.99  151.11  341.83  170.21  342.34  171.56  342.32
#Mann= 3 , 0 , 0
       0     .08       0   61.42    .045       0   74.45      .1       0
#Block Obstruct= 5 ,-1
  107.35  117.55344.8834  147.23  155.27344.8887   76.93   97.46 344.392
   11.02   11.93348.1946    22.8   33.65348.1946
Bank Sta=61.42,74.45
XS Rating Curve= 0 ,0
Exp/Cntr=0.3,0.1

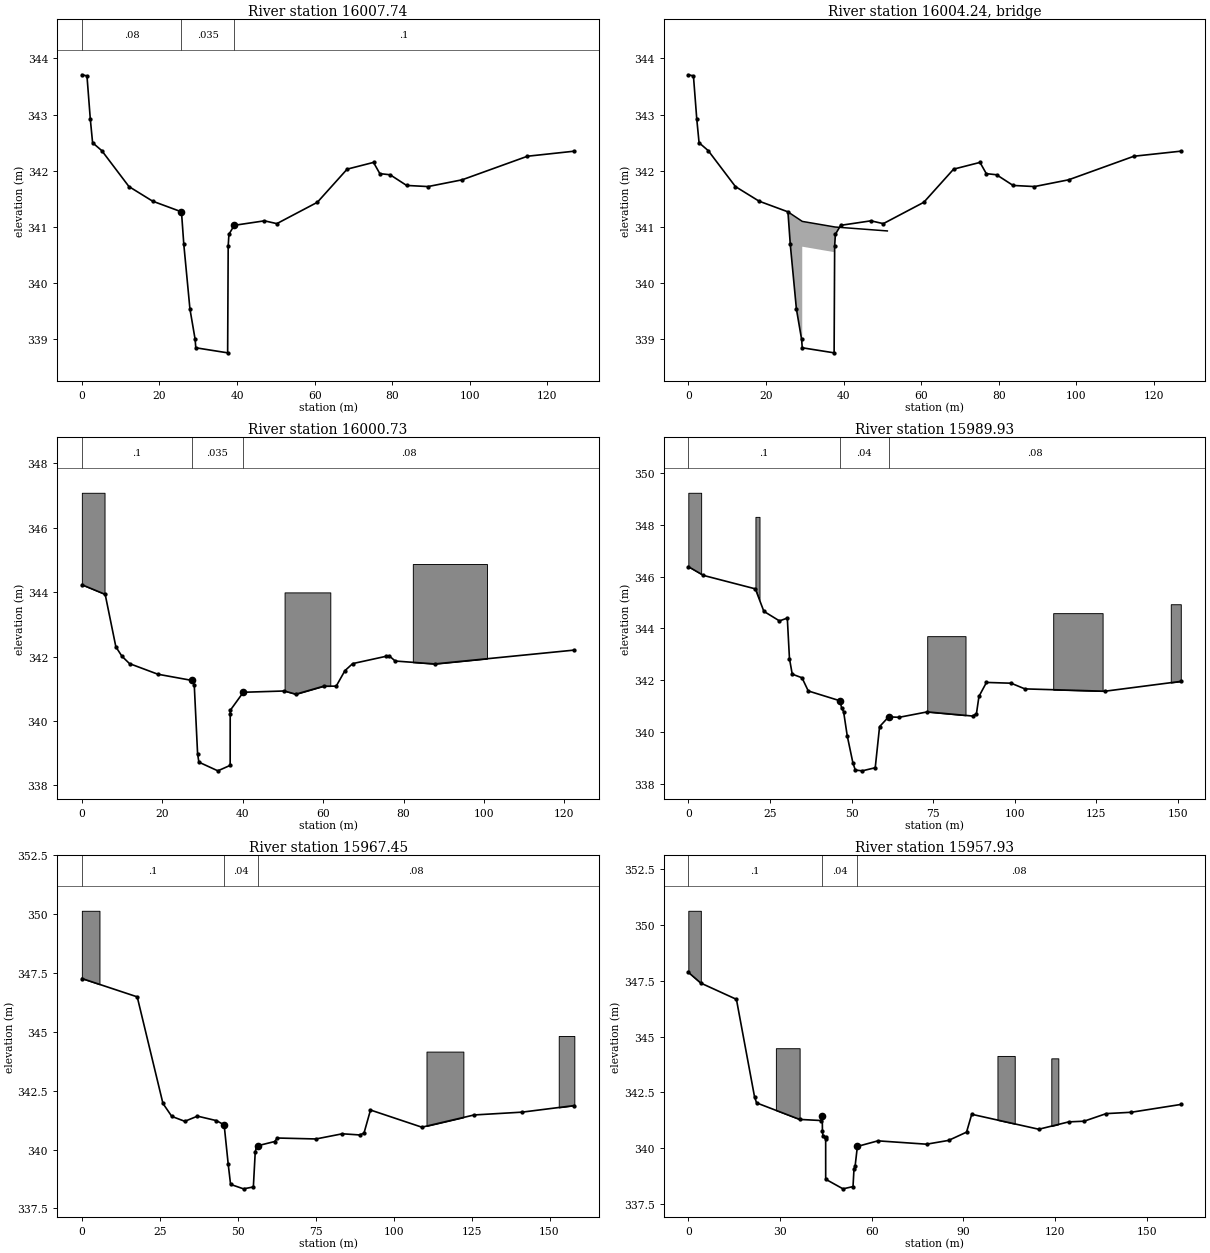
Type RM Length L Ch R = 1 ,16007.74,6.71,7.01,8.54
XS GIS Cut Line= 6
-610971.77129999   -1045859.4797    -610980.0408   -1045836.7296
    -610989.9356   -1045825.7279    -610992.9954   -1045818.0942
-611010.51089999   -1045778.8608    -611023.0044   -1045744.3002
#Sta/Elev= 28
       0  343.71    1.32  343.69    2.18  342.92    2.77   342.5    5.13  342.36
   12.14  341.72   18.24  341.46   25.68  341.27   26.28  340.69   27.86  339.54
    29.2     339   29.37  338.85   37.58  338.76   37.72  340.66   37.91  340.87
   39.28  341.03   47.07  341.11   50.26  341.06    60.7  341.44   68.38  342.03
   75.18  342.15   76.81  341.95   79.46  341.93   83.71  341.74   89.23  341.72
   98.01  341.84  114.86  342.26  126.94  342.35
#Mann= 3 , 0 , 0
       0     .08       0   25.68    .035       0   39.28      .1       0
Bank Sta=25.68,39.28
XS Rating Curve= 0 ,0
Exp/Cntr=0.5,0.3

Type RM Length L Ch R = 3 ,16004.24,,,
BEGIN DESCRIPTION:
16199.9  PF 206 SILNIÈNÍ ŽLB MOSTEK V
END DESCRIPTION:
Bridge Culvert--1,0,-1,-1, 0
Deck Dist Width WeirC Skew NumUp NumDn MinLoCord MaxHiCord MaxSubmerge Is_Ogee
0.5,6,1.4,0, 5, 5, , , 0.98, 0, 0,0,,
   25.68   29.37   37.83   37.83    51.3
  341.27   341.1     341     341  340.93
          340.65  340.55
   24.73   28.42   36.88   36.88   50.35
  341.27   341.1     341     341  340.93
          340.65  340.55
BR Coef=-1 , 0 , 0 ,, 0 ,,,0.8,-1,,0,
WSPro=,,,, 1 ,,,, 0 ,,,, 0 ,,,,-1 ,-1 ,-1 , 0 , 0 , 0 , 0 , 0
BC Design=,, 0 ,, 0 ,,,,,,
BC HTab HWMax=342.5
BC HTab TWMax=342.3
BC HTab MaxFlow=80
BC Use User HTab Curves=0
BC User HTab FreeFlow(D)= 0

Type RM Length L Ch R = 1 ,16000.73,9.83,10.81,10.61
XS GIS Cut Line= 5
     -610976.975   -1045864.1751    -610985.2445    -1045841.425
    -610997.4496   -1045827.8546-611019.62709999   -1045783.7506
    -611027.9807   -1045754.2729
#Sta/Elev= 26
       0  344.23     5.8  343.93    8.46   342.3    9.96  342.01   11.85  341.78
   18.91  341.45   27.28  341.26   27.95  341.12   28.78  338.98    29.1  338.72
   33.82  338.45   36.88  338.62   36.89   340.2   36.91  340.33   40.15  340.89
   50.35  340.93   53.21  340.83   60.15  341.08   63.25  341.08   65.41  341.56
   67.34  341.78   75.75  342.01   76.44  342.02   77.92  341.86   87.77  341.77
  122.46   342.2
#Mann= 3 , 0 , 0
       0      .1       0   27.28    .035       0   40.15     .08       0
#Block Obstruct= 3 ,-1
       0    5.64347.0853    82.3  100.74344.8723   50.41   61.78343.9916
Bank Sta=27.28,40.15
XS Rating Curve= 0 ,0
Exp/Cntr=0.5,0.3

Type RM Length L Ch R = 1 ,15989.93,23.84,22.47,19.81
XS GIS Cut Line= 6
    -610970.3973   -1045887.0677    -610993.4662   -1045848.7396
    -611005.6395   -1045834.6026    -611029.7291    -1045788.774
    -611034.3488   -1045770.0031    -611035.9998    -1045753.747
#Sta/Elev= 30
       0  346.39    4.63  346.05   20.52  345.53   23.14  344.66   27.92  344.29
   30.32   344.4   30.98  342.83   31.83  342.23   34.82  342.09   36.74  341.58
   46.45   341.2   46.96  340.92   47.56  340.78   48.68  339.84   50.39  338.81
   51.14  338.52   53.27  338.49   57.25  338.61   58.58   340.2   61.37  340.58
   64.54  340.56   73.16  340.77   87.05  340.61   88.25   340.7   89.02  341.37
   91.32  341.91   98.87  341.88  103.09  341.66   127.6  341.57  150.84  341.95
#Mann= 3 , 0 , 0
       0      .1       0   46.45     .04       0   61.37     .08       0
#Block Obstruct= 5 ,-1
   20.56    21.8348.3146  111.76  126.89  344.59   73.17    84.9   343.7
       0    3.93349.2465  147.77  150.84344.9349
Bank Sta=46.45,61.37
XS Rating Curve= 0 ,0
Exp/Cntr=0.3,0.1

Type RM Length L Ch R = 1 ,15967.45,9.35,9.53,9.59
XS GIS Cut Line= 5
-610992.09319999   -1045900.0587    -611013.8884   -1045860.6581
-611022.15659999   -1045848.0903-611039.60269999   -1045797.2262
-611042.06069999   -1045753.1775
#Sta/Elev= 26
       0  347.27   17.76  346.49   26.01  341.96   28.84  341.41   33.02   341.2
   37.08  341.42   43.15  341.23   45.64  341.05   46.95  339.37    47.7  338.52
   51.85  338.33   55.01  338.41   55.61  339.89   56.02  340.12   56.35  340.16
   61.82  340.34   62.73  340.49    75.1  340.45   83.56  340.67   89.14  340.62
    90.5   340.7   92.58  341.68  109.06  340.95   125.8  341.47  141.22  341.59
  157.96  341.87
#Mann= 3 , 0 , 0
       0      .1       0   45.64     .04       0   56.35     .08       0
#Block Obstruct= 3 ,-1
  110.54  122.37344.1635       0    5.65350.1486  152.96  157.96344.8275
Bank Sta=45.64,56.35
XS Rating Curve= 0 ,0
Exp/Cntr=0.3,0.1

Type RM Length L Ch R = 1 ,15957.93,15.71,14.65,13.63
XS GIS Cut Line= 5
     -611000.734   -1045904.2531    -611020.2591   -1045868.1678
-611030.47859999   -1045852.8987-611045.06769999   -1045811.8192
-611048.78449999   -1045753.7894
#Sta/Elev= 30
       0  347.88    4.05   347.4   15.74  346.67   21.67   342.3   22.34  342.03
   36.42  341.29    43.5  341.24   43.53  341.44   43.83  341.45   43.88  340.76
   44.08  340.53   44.92  340.42   44.94  340.49   44.95  338.61   50.61  338.18
   53.89  338.28    54.2  339.05   54.58   339.2   55.32  340.08   62.03  340.33
   77.96  340.18   85.16  340.35   91.04  340.72   92.73  341.52  114.67  340.85
  124.49  341.18  129.49  341.21  136.74  341.55   144.9  341.61  161.14  341.96
#Mann= 3 , 0 , 0
       0      .1       0   43.83     .04       0   55.32     .08       0
#Block Obstruct= 4 ,-1
  118.77  121.07344.0259  101.15   106.8344.1338       0    4.09350.6369
   28.65   36.42344.4799
Bank Sta=43.83,55.32
XS Rating Curve= 0 ,0
Exp/Cntr=0.3,0.1

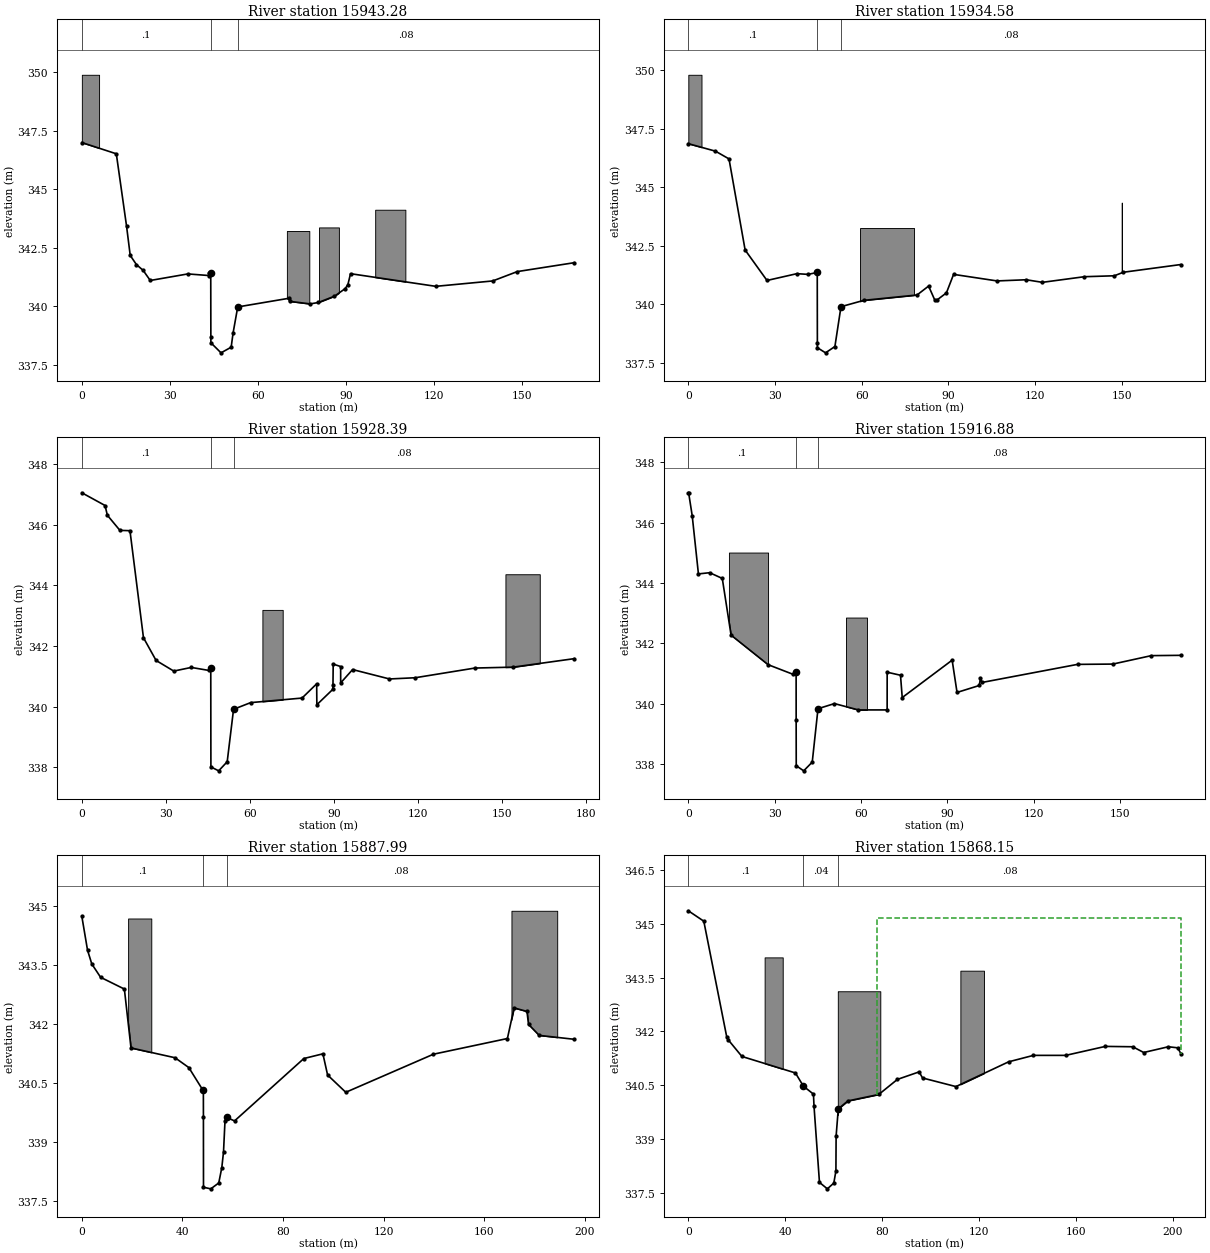
Type RM Length L Ch R = 1 ,15943.28,9.23,8.7,8.01
XS GIS Cut Line= 5
-611018.45259999   -1045911.2168    -611035.5181   -1045872.8951
-611044.51399999   -1045854.9034-611060.44139999   -1045803.4049
-611062.47329999   -1045751.5215
#Sta/Elev= 30
       0  346.99   11.75  346.51   15.23  343.43   16.49  342.17    18.6  341.78
   20.91  341.53   23.32   341.1   36.13  341.38   43.42  341.31   43.45  341.42
   43.92  341.41   43.94  341.41   43.98  338.67   43.99  338.44   47.44  338.01
    50.9  338.25   51.56  338.86   53.14  339.97    70.6  340.34   70.79  340.21
   77.82   340.1   80.64  340.16   86.13  340.43   89.75  340.75   90.69  340.92
   91.59  341.39  120.67  340.85  140.07  341.08  148.45  341.48  167.89  341.86
#Mann= 3 , 0 , 0
       0      .1       0   43.92     .04       0   53.14     .08       0
#Block Obstruct= 4 ,-1
   80.86   87.63 343.366     100  110.29344.1213    69.9   77.54 343.214
       0    5.87349.8845
Bank Sta=43.92,53.14
XS Rating Curve= 0 ,0
Exp/Cntr=0.3,0.1

Type RM Length L Ch R = 1 ,15934.58,6.66,6.18,4
XS GIS Cut Line= 5
    -611025.0566   -1045914.2648    -611043.4717   -1045877.6887
-611053.92689999   -1045851.5159    -611065.9296   -1045802.0495
    -611067.1996   -1045751.6727
#Sta/Elev= 28
       0  346.86    9.39  346.54   14.08  346.21   19.66  342.32   27.23  341.02
   37.57  341.31    41.4  341.28    44.6  341.36   44.62  341.36   44.66  338.33
   44.67  338.15   47.49  337.93   50.73   338.2   52.83   339.9   60.69  340.17
   79.16   340.4   83.15  340.78   85.27  340.19   85.89  340.17   89.32  340.49
    91.8  341.28  106.84     341  116.94  341.05  122.53  340.94  137.05  341.18
  147.45  341.22  150.52  341.37  170.43   341.7
#Mann= 3 , 0 , 0
       0      .1       0    44.6     .04       0   52.83     .08       0
#Block Obstruct= 3 ,-1
   59.43   78.12343.2577  149.97  150.06344.3423       0    4.56349.8012
Bank Sta=44.6,52.83
XS Rating Curve= 0 ,0
Exp/Cntr=0.3,0.1

Type RM Length L Ch R = 1 ,15928.39,11.22,11.51,11.57
XS GIS Cut Line= 5
    -611031.7622   -1045918.1087-611049.80559999   -1045880.3034
-611056.15569999   -1045858.6076    -611071.9197   -1045799.5853
    -611077.0852   -1045749.5899
#Sta/Elev= 30
       0  347.05    8.29  346.63     9.1  346.31   13.59  345.81   17.18   345.8
      22  342.27   26.51  341.52   32.82  341.17   39.07  341.29   45.43  341.19
   46.03  341.27   46.08  338.01   48.85  337.88    51.9  338.18   54.17  339.91
   60.29  340.13   78.62  340.28   83.85  340.75   83.91  340.06   89.64  340.57
   89.67  340.72   89.75   341.4   92.41  341.32   92.42  340.78   96.68  341.22
  109.85  340.91  119.02  340.95  140.36  341.27     154   341.3  175.85  341.58
#Mann= 3 , 0 , 0
       0      .1       0   46.03     .04       0   54.17     .08       0
#Block Obstruct= 2 ,-1
   64.47   71.72343.1876  151.25  163.51344.3635
Bank Sta=46.03,54.17
XS Rating Curve= 0 ,0
Exp/Cntr=0.3,0.1

Type RM Length L Ch R = 1 ,15916.88,28.68,28.89,29.62
XS GIS Cut Line= 5
    -611049.8937   -1045915.0428    -611060.9182    -1045881.891
    -611064.3608   -1045872.7106    -611083.0196   -1045801.8009
-611091.84849999   -1045749.5303
#Sta/Elev= 30
       0  346.99     .14  346.97    1.35  346.23    3.51   344.3    7.42  344.34
    11.8  344.15   14.85  342.27   27.72  341.29    36.4  340.97   37.45  341.06
   37.46  339.45   37.49  337.94   40.08  337.77   43.05  338.06   45.05  339.83
   50.76     340   59.07  339.79   69.07  339.79   69.08  341.04   73.71  340.94
   74.31   340.2   91.65  341.44   93.35  340.37  101.08   340.6   101.5  340.85
  101.99   340.7   135.2   341.3  147.48  341.31  160.85  341.59  171.08   341.6
#Mann= 3 , 0 , 0
       0      .1       0   37.45     .04       0   45.05     .08       0
#Block Obstruct= 2 ,-1
   54.77   62.06342.8527   14.11    27.7 345.008
Bank Sta=37.45,45.05
XS Rating Curve= 0 ,0
Exp/Cntr=0.3,0.1

Type RM Length L Ch R = 1 ,15887.99,19.91,19.84,18.61
XS GIS Cut Line= 5
-611071.43079999   -1045929.3784-611088.29679999   -1045890.3326
    -611096.8689   -1045865.3553-611110.03889999   -1045807.9662
    -611116.1349   -1045740.2327
#Sta/Elev= 30
       0  344.74    2.26  343.88    3.95  343.53    7.45  343.19   16.91  342.89
   19.54  341.39   37.06  341.14   42.53  340.89   48.17  340.31   48.32   340.3
   48.34  339.64   48.37  337.84   51.28   337.8   54.44  337.95   55.65  338.34
   56.33  338.74   56.93  339.54   57.62  339.62   60.71  339.53   88.27  341.12
   95.85  341.24   97.72   340.7  104.95  340.26   139.8  341.23  169.22  341.63
  171.87  342.41     177  342.32  177.61  341.99  181.85  341.71  195.83  341.61
#Mann= 3 , 0 , 0
       0      .1       0   48.17     .04       0   57.62     .08       0
#Block Obstruct= 2 ,-1
   18.39   27.61344.6881  170.83  189.02344.8846
Bank Sta=48.17,57.62
XS Rating Curve= 0 ,0
Exp/Cntr=0.3,0.1

Type RM Length L Ch R = 1 ,15868.15,11.59,11.46,10.73
XS GIS Cut Line= 3
    -611095.4338     -1045938.72    -611118.9712   -1045855.5772
    -611134.9309   -1045739.7811
#Sta/Elev= 30
       0  345.36    6.39  345.07    15.9  341.83   16.52  341.76   22.12   341.3
   44.21  340.84   47.53  340.47   51.66  340.25   51.88  339.92   54.14  337.79
   57.39  337.61   60.06  337.77   60.93  338.11   61.01  339.08   61.91  339.84
   65.86  340.06   78.61  340.24   86.31  340.66   95.28  340.87   96.69   340.7
  110.47  340.46  132.21  341.15  142.47  341.33  155.79  341.33  172.16  341.58
  183.48  341.57  187.98  341.41  198.16  341.57  202.07  341.54   203.3  341.38
#Mann= 3 , 0 , 0
       0      .1       0   47.53     .04       0   61.91     .08       0
#XS Ineff= 2 , 0
                           77.94          345.17
Permanent Ineff=
       F       F
#Block Obstruct= 3 ,-1
  112.31  122.04343.6905    31.5   38.97344.0612   61.71   79.25343.1169
Bank Sta=47.53,61.91
XS Rating Curve= 0 ,0
Exp/Cntr=0.3,0.1

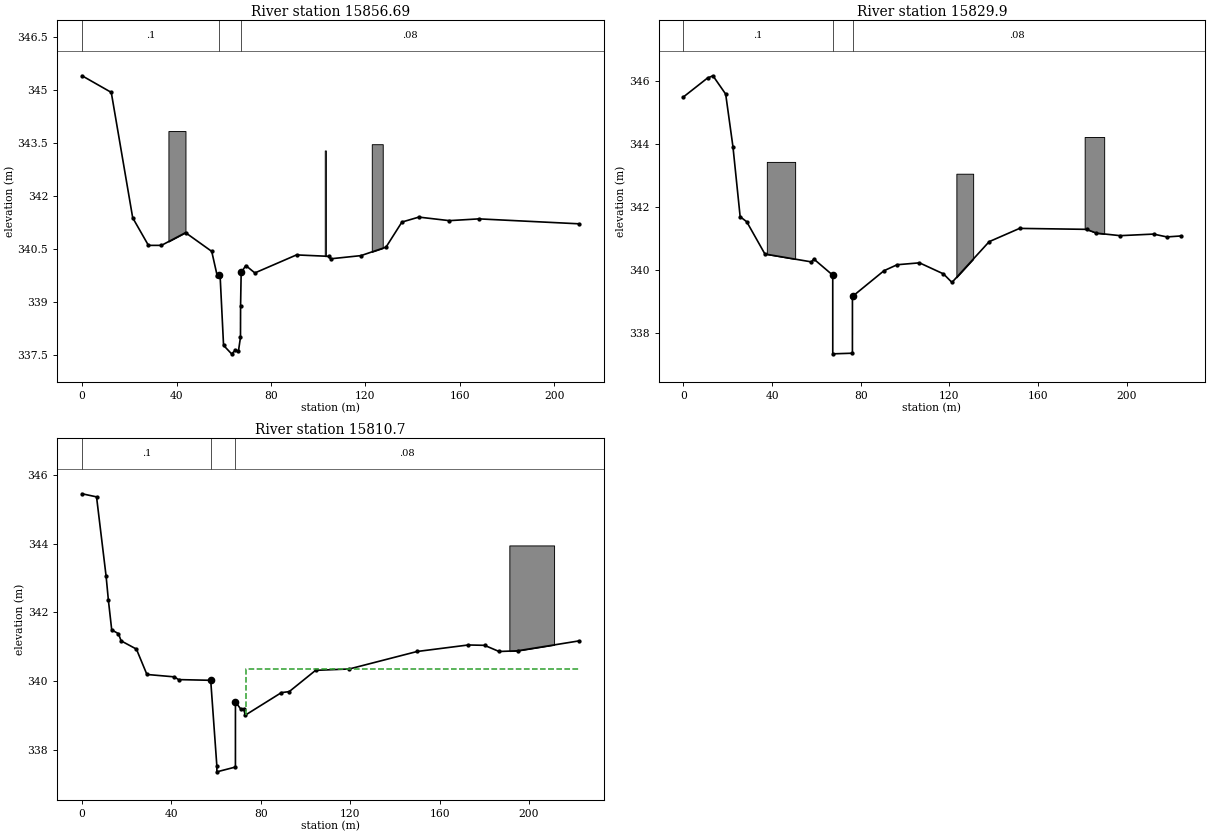
Type RM Length L Ch R = 1 ,15856.69,26.05,26.8,27.68
XS GIS Cut Line= 4
    -611103.5637   -1045946.2449-611120.18499999   -1045894.0618
    -611124.3476   -1045877.4141     -611151.067   -1045741.3785
#Sta/Elev= 30
       0  345.39   12.36  344.92   21.44  341.37    28.1  340.59   33.62  340.59
   43.81  340.95   54.91  340.42   57.26  339.72   57.88  339.75   58.46  339.73
   59.92  337.76   63.31  337.52   64.92  337.62   66.21  337.59   67.09  337.99
   67.13  338.88   67.38  339.83   67.49  339.83   69.33  340.02   73.18  339.81
   90.82  340.32  104.41  340.28   105.3  340.21  118.11   340.3  128.73  340.54
  135.47  341.25  142.63  341.39  155.53  341.29  168.07  341.34  210.56   341.2
#Mann= 3 , 0 , 0
       0      .1       0   57.88    .035       0   67.49     .08       0
#Block Obstruct= 3 ,-1
   122.7  127.34343.4536  102.78  103.27 343.276   36.57   43.79343.8254
Bank Sta=57.88,67.49
XS Rating Curve= 0 ,0
Exp/Cntr=0.3,0.1

Type RM Length L Ch R = 1 ,15829.9 ,19.46,19.19,18.61
XS GIS Cut Line= 4
-611127.02369999   -1045962.5109-611145.18809999   -1045901.2055
    -611151.8026   -1045882.0232    -611169.1645    -1045742.966
#Sta/Elev= 28
       0  345.48   10.89  346.08   13.33  346.15   19.07  345.57   22.36   343.9
    25.6  341.69   28.57  341.53   36.77  340.51   57.75  340.26   58.86  340.35
   67.39  339.84    67.4  337.35   76.27  337.37   76.28  339.16   76.36  339.17
   90.51  339.98   96.45  340.17  106.54  340.23  117.37  339.88  121.19  339.61
  137.99   340.9  151.71  341.32  181.95  341.29  186.38  341.17  197.12  341.09
  212.17  341.14   218.2  341.05  224.37  341.08
#Mann= 3 , 0 , 0
       0      .1       0   67.39    .035       0   76.36     .08       0
#Block Obstruct= 3 ,-1
  123.19  130.76343.0505  181.09   189.9344.2119   37.64   50.42343.4244
Bank Sta=67.39,76.36
XS Rating Curve= 0 ,0
Exp/Cntr=0.3,0.1

Type RM Length L Ch R = 1 ,15810.7 ,23.98,23.78,23.78
XS GIS Cut Line= 4
-611147.12029999   -1045960.8525-611163.70899999   -1045907.1587
-611169.66209999   -1045887.9764    -611188.3553   -1045742.9866
#Sta/Elev= 29
       0  345.46    6.47  345.37   10.74  343.06   11.78  342.35   13.26  341.49
   16.26  341.38   17.47  341.17   24.31  340.93   29.01  340.19    41.3  340.12
   43.17  340.04   57.56  340.02   60.31  337.52   60.32  337.35   68.62  337.49
   68.63  339.39   71.01  339.18   72.44  339.17   72.96     339   89.18  339.66
    92.7  339.69  104.49  340.31  119.55  340.35  149.92  340.86   172.8  341.05
   180.1  341.04  186.59  340.86  194.88  340.88  222.47  341.17
#Mann= 3 , 0 , 0
       0      .1       0   57.56     .04       0   68.63     .08       0
#XS Ineff= 2 , 0
                           73.33          340.34
Permanent Ineff=
       F       F
#Block Obstruct= 1 ,-1
   191.2  211.22343.9536
Bank Sta=57.56,68.63
XS Rating Curve= 0 ,0
Exp/Cntr=0.3,0.1