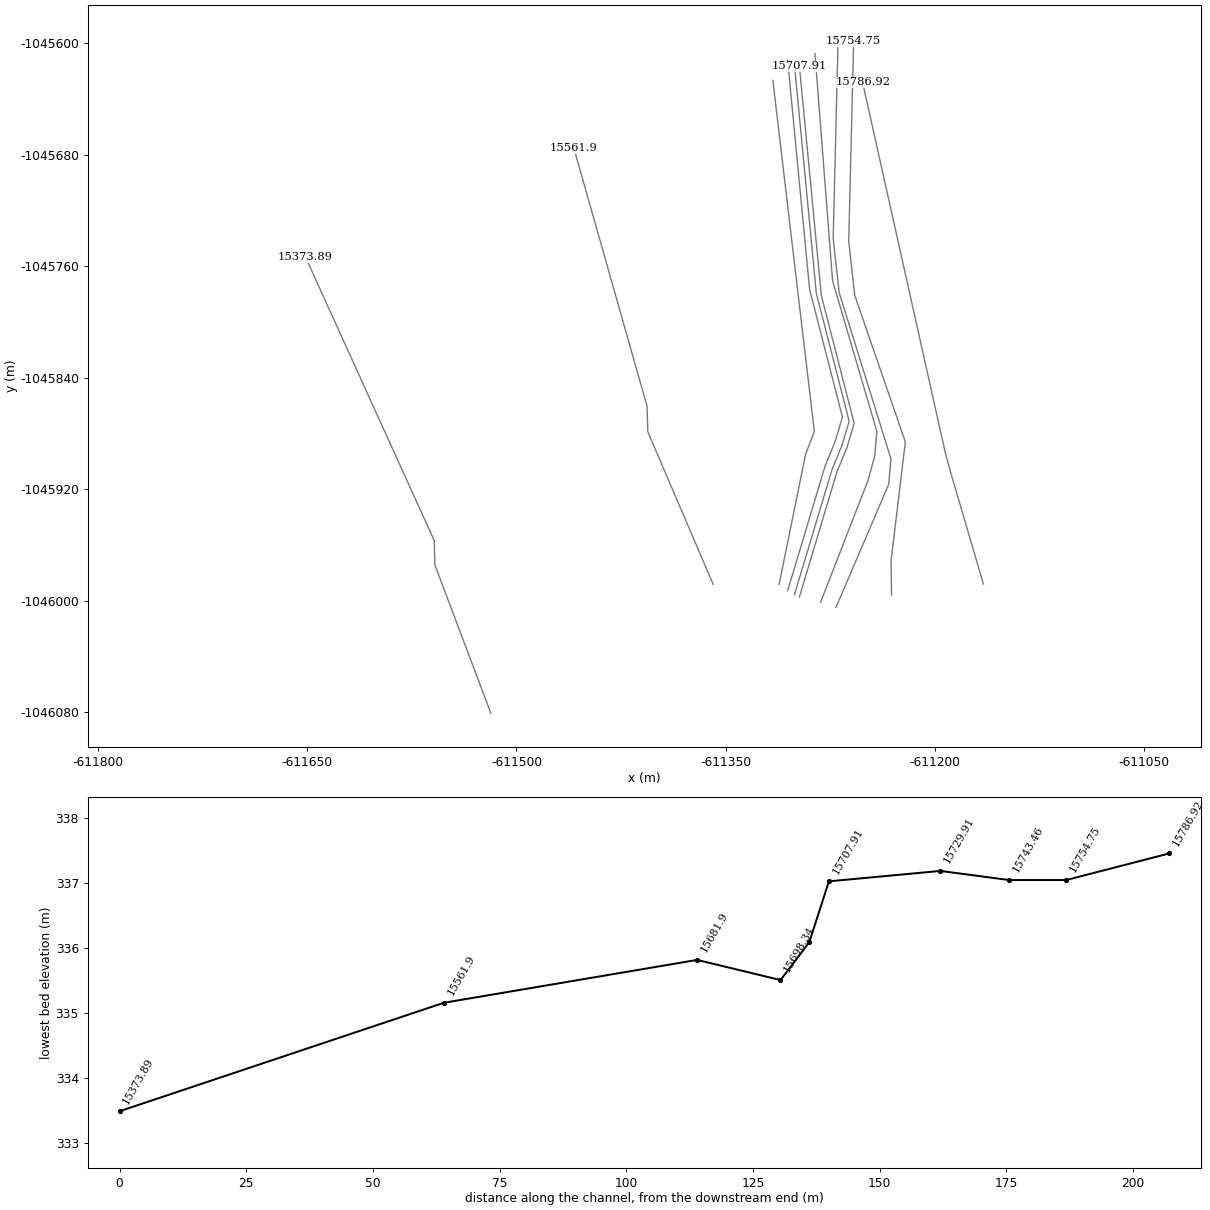
HEC-RAS study PPO_Kvasiny_efektiv.prj: PPO_Kvasiny_efektivita

--- PPO_Kvasiny_efektiv.g04 (geometry) --- (continued)

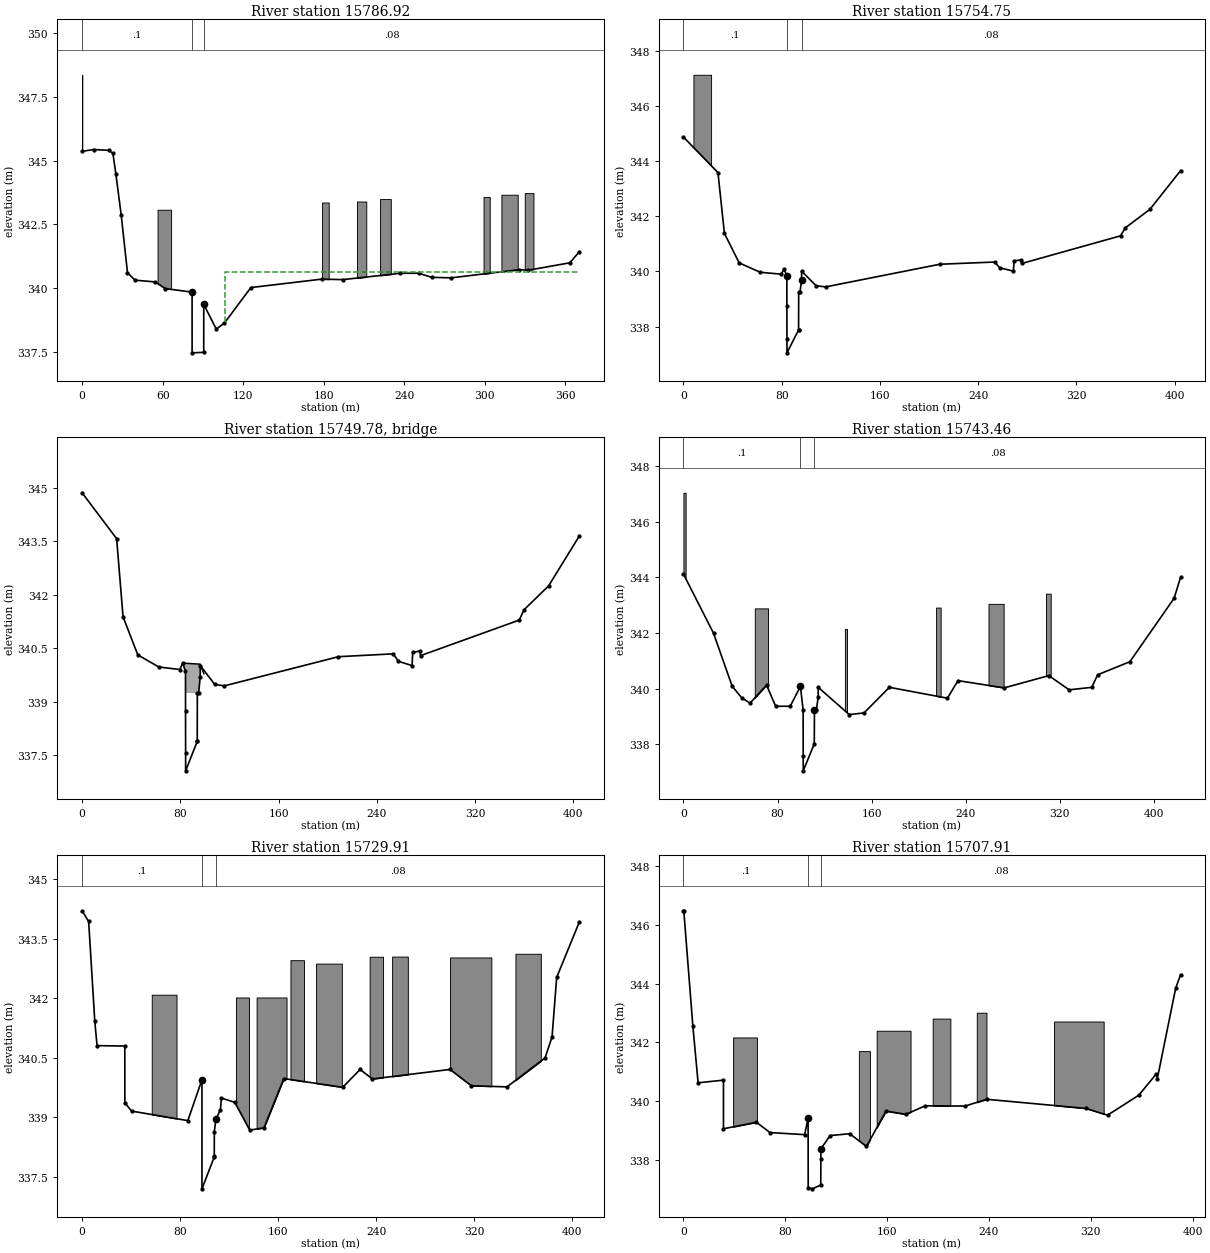
Type RM Length L Ch R = 1 ,15786.92,22.11,20.36,18.99
XS GIS Cut Line= 4
     -611165.032   -1045987.8568    -611187.5216   -1045911.1275
-611192.15179999    -1045894.591    -611251.6831   -1045628.0227
#Sta/Elev= 27
       0  345.36    8.56  345.43   19.87   345.4   22.95  345.28   25.17  344.47
   29.12  342.87   33.82   340.6   39.46  340.31   54.42  340.24   61.97  339.98
   81.93  339.84   81.94  337.46   90.61  337.48   90.62  339.36   99.95  338.39
  106.03  338.63  125.74  340.02  178.62  340.35  194.02  340.33  237.09  340.58
  250.73  340.58  260.41  340.42  274.87   340.4  325.38  340.72  332.41   340.7
  363.26  340.99  370.26  341.42
#Mann= 3 , 0 , 0
       0      .1       0   81.93    .035       0   90.62     .08       0
#XS Ineff= 2 , 0
                           106.7          340.64
Permanent Ineff=
       F       F
#Block Obstruct= 8 ,-1
   56.21    66.3343.0709  221.93  229.93343.4889  329.69  336.18343.7225
  312.31  324.45343.6595     299  303.61343.5717       0     .15348.3615
  178.74  183.69343.3546  204.71  211.66343.3929
Bank Sta=81.93,90.62
XS Rating Curve= 0 ,0
Exp/Cntr=0.3,0.1

Type RM Length L Ch R = 1 ,15754.75,11.28,11.29,11.04
XS GIS Cut Line= 6
     -611230.918   -1045995.6999    -611231.2355   -1045970.9348
    -611221.0212    -1045885.914    -611257.3088   -1045780.7867
    -611261.6351    -1045742.032    -611258.0872   -1045598.3207
#Sta/Elev= 30
       0  344.87   28.12  343.58   33.36  341.38   45.38  340.31    62.5  339.97
    79.6   339.9   81.88  340.08   84.19  339.85   84.22  338.74   84.29  337.54
    84.3  337.05   93.74  337.88   93.75  337.89   93.83  339.24   94.91  339.25
   96.15  339.68   96.21  340.01  108.01  339.48  115.83  339.44  208.71  340.26
  253.27  340.34  257.54  340.13  268.64  340.01  269.15  340.38  275.01  340.42
   275.6  340.29  355.89  341.29  359.79  341.58  379.77  342.25  404.72  343.65
#Mann= 3 , 0 , 0
       0      .1       0   84.19    .035       0   96.15     .08       0
#Block Obstruct= 1 ,-1
    8.14   22.52347.1254
Bank Sta=84.19,96.15
XS Rating Curve= 0 ,0
Exp/Cntr=0.5,0.3

Type RM Length L Ch R = 3 ,15749.78,,,
Bridge Culvert--1,0,-1,-1, 0
Deck Dist Width WeirC Skew NumUp NumDn MinLoCord MaxHiCord MaxSubmerge Is_Ogee
0.5,10.4,1.4,0, 3, 2, , , 0.98, 0, 0,0,,
   81.88   96.21   99.18
  340.08  340.05  339.78
  339.24  339.23  339.78
   99.48   114.6
  340.08  340.05
  339.24  339.23
BR Coef=-1 , 0 , 0 ,, 0 ,,,0.8,-1,,0,
WSPro=,,,, 1 ,,,, 0 ,,,, 0 ,,,,-1 ,-1 ,-1 , 0 , 0 , 0 , 0 , 0
BC Design=,, 0 ,, 0 ,,,,,,
BC HTab HWMax=340.6
BC HTab TWMax=340.5
BC HTab MaxFlow=80
BC Use User HTab Curves=0
BC User HTab FreeFlow(D)= 0

Type RM Length L Ch R = 1 ,15743.46,14.98,13.54,10.62
XS GIS Cut Line= 6
    -611270.7595   -1046004.5644    -611232.9684    -1045916.367
-611231.32099999   -1045898.0854-611268.45829999   -1045778.8404
    -611272.7846   -1045740.0857    -611269.2368   -1045596.3744
#Sta/Elev= 30
       0  344.12   25.61  341.99   41.43  340.09   49.41  339.68    56.6  339.48
   70.68  340.13   78.41  339.37   90.78  339.37   99.48  340.08  101.76  339.24
  101.86  337.58  101.87  337.05  111.26  338.02   111.4  339.23  113.07  339.24
  114.55   339.7   114.6  340.05  140.98  339.07  153.54  339.13  175.09  340.05
  224.48  339.66  233.43  340.29  272.77  340.03  310.69  340.47  327.95  339.96
  347.21  340.05  352.21   340.5  379.62  340.97  417.22  343.25  422.69     344
#Mann= 3 , 0 , 0
       0      .1       0   99.48    .035       0   111.4     .08       0
#Block Obstruct= 6 ,-1
   137.3  139.05342.1466  214.83  218.71342.9147   60.66   71.88342.8853
  308.26  312.29343.4149  259.38  272.25 343.048       0    1.87347.0369
Bank Sta=99.48,111.4
XS Rating Curve= 0 ,0
Exp/Cntr=0.5,0.3

Type RM Length L Ch R = 1 ,15729.91,23.06,22.01,19.38
XS GIS Cut Line= 6
    -611281.7885   -1046000.8759-611247.89779999   -1045913.8258
    -611243.0385   -1045896.2879    -611241.4543   -1045878.3214
    -611273.2296   -1045770.2109    -611285.8491   -1045607.2642
#Sta/Elev= 30
       0   344.2    5.36  343.93   10.38  341.41   12.22   340.8   34.88  340.79
    34.9  339.36   40.38  339.15    86.3  338.91   97.84  339.94   97.85  337.19
  107.83  337.99  107.89  338.03  107.94  338.63  109.25  338.95  112.92  339.18
  113.68  339.48  124.63  339.37  136.84  338.67  148.48  338.73  164.67  339.97
  212.71  339.75  226.96   340.2  236.88  339.96   300.3   340.2  317.72  339.79
  346.77  339.76  377.88  340.49   383.6  341.02  387.37  342.52  405.77  343.91
#Mann= 3 , 0 , 0
       0      .1       0   97.84    .035       0  109.25     .08       0
#Block Obstruct= 9 ,-1
  125.59  136.26342.0143  142.44  166.88342.0143     191  212.02 342.868
   56.85   77.08342.0844  300.27  334.05343.0232  253.06  265.89343.0455
  353.72  374.44343.1166  170.09  181.11342.9549   234.7  245.66343.0414
Bank Sta=97.84,109.25
XS Rating Curve= 0 ,0
Exp/Cntr=0.3,0.1

Type RM Length L Ch R = 1 ,15707.91,3.89,3.89,3.9
XS GIS Cut Line= 6
    -611297.0154   -1045997.0692-611269.98739999   -1045907.1252
    -611262.9829    -1045890.143    -611257.7215   -1045872.5269
    -611281.2811   -1045780.8493    -611297.0154   -1045616.4002
#Sta/Elev= 30
       0  346.46     .29  346.47     7.4  342.56   11.53  340.63   31.45  340.72
   31.46  339.07   57.35  339.29   68.02  338.94   95.25  338.87   97.93  339.43
   98.03  337.07   101.3  337.03  107.88  337.16  107.95  338.03  108.02  338.39
  115.25  338.84  130.67   338.9  143.77  338.47  159.13  339.67  174.73  339.56
  190.03  339.85  221.21  339.84  238.26  340.07  316.29  339.76  333.17  339.53
  357.76  340.21  371.62  340.94  372.23  340.76  386.69  343.84  390.53   344.3
#Mann= 3 , 0 , 0
       0      .1       0   97.93    .035       0  108.02     .08       0
#Block Obstruct= 6 ,-1
   39.03   57.74342.1694  291.09  330.12342.7108  195.81   209.7342.8094
  151.82  178.41342.3976  137.81  146.51341.7051  230.44  238.06343.0097
Bank Sta=97.93,108.02
XS Rating Curve= 0 ,0
Exp/Cntr=0.3,0.1

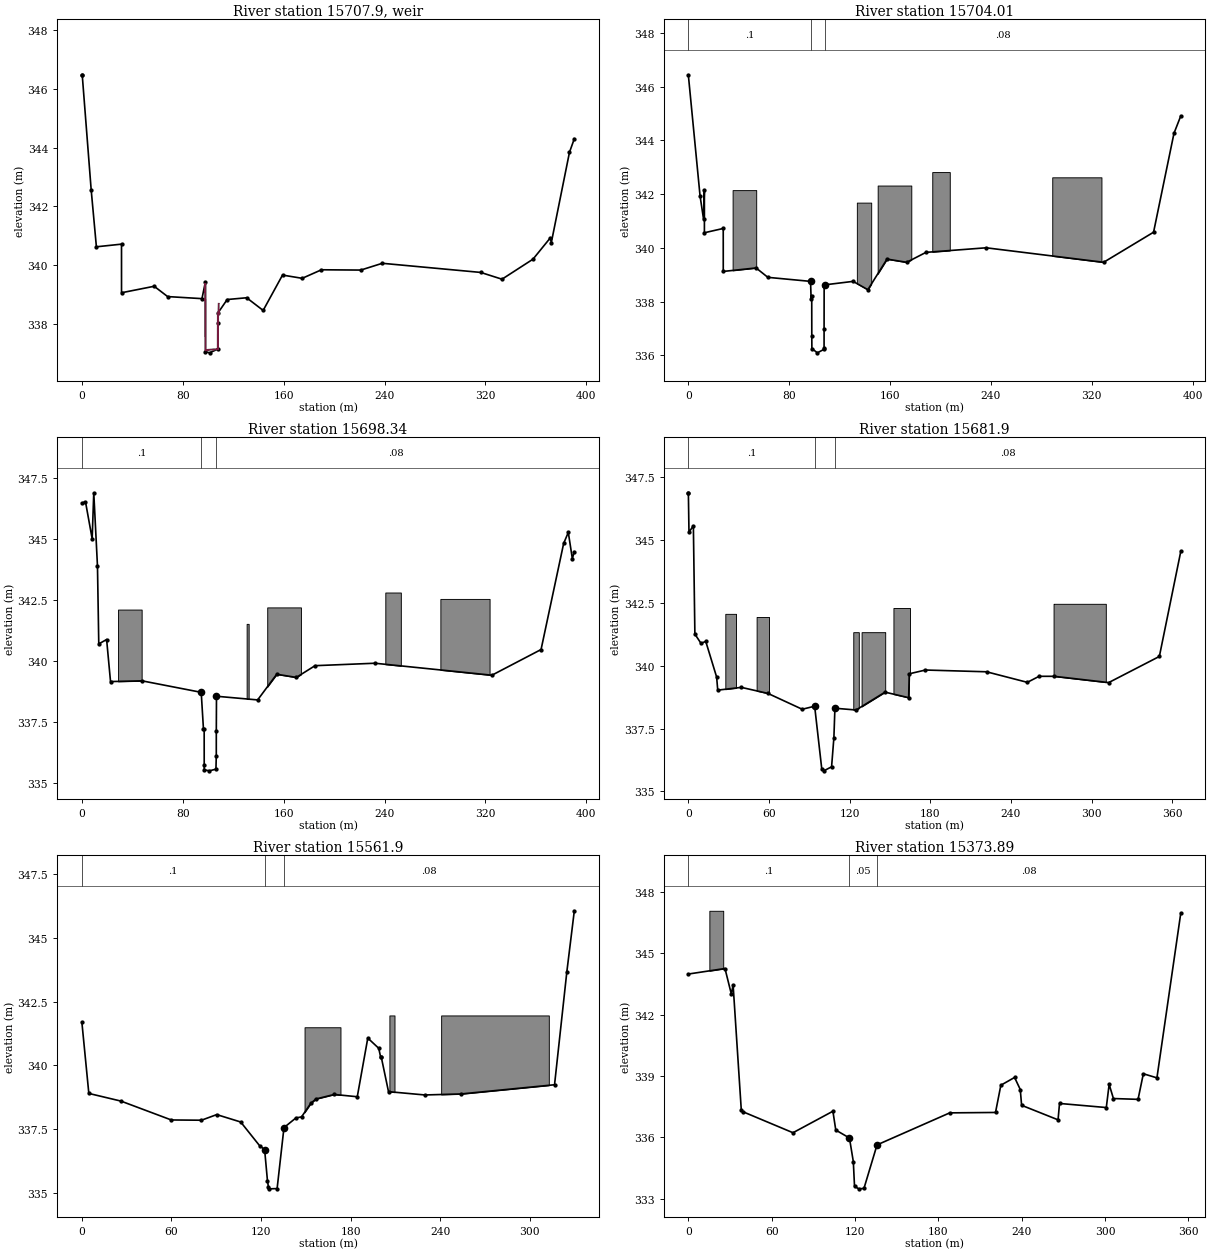
Type RM Length L Ch R = 5 ,15707.9 ,,,
IW Pilot Flow=0
#Inline Weir SE= 8
   97.93  339.36      98  337.62   98.07  337.12  107.87  337.16  107.88  337.57
  107.97  338.38  108.33  338.34   108.6  338.69
IW Dist,WD,Coef,Skew,MaxSub,Min_El,Is_Ogee,SpillHt,DesHd
0.1,1,1.4,0,0.98,, 0 ,,,0,0,
Inline Weir Flap Gates= 0

Type RM Length L Ch R = 1 ,15704.01,5.49,5.67,5.52
XS GIS Cut Line= 6
    -611300.6086    -1045995.581    -611273.5806   -1045905.6369
-611266.57609999   -1045888.6548    -611261.3147   -1045871.0387
    -611284.8744   -1045779.3611    -611300.6086    -1045614.912
#Sta/Elev= 30
       0  346.44    9.31  341.93   12.04  341.08   12.75  342.14   12.76  340.56
   27.69  340.72   27.71  339.12   53.73  339.25   63.09   338.9   96.92  338.75
   97.39  338.08   97.86  338.22   97.92   336.7   97.99  336.25  102.33  336.09
  107.55  336.22  107.65  336.28  107.66  336.99  107.71  338.56   108.6338.6232
  130.67  338.75  142.36  338.44  157.56  339.58  173.15  339.46  188.47  339.83
  236.17     340  329.33  339.46  368.94  340.58  385.12  344.26  390.53  344.91
#Mann= 3 , 0 , 0
       0      .1       0   96.92    .035       0   108.6     .08       0
#Block Obstruct= 5 ,-1
   35.12   53.83342.1467  288.59  327.61342.6234  193.44  207.33342.8185
  150.16  176.82342.3174  133.64  145.02341.6818
Bank Sta=96.92,108.6
XS Rating Curve= 0 ,0
Exp/Cntr=0.3,0.1

Type RM Length L Ch R = 1 ,15698.34,15.5,16.44,16.98
XS GIS Cut Line= 6
-611305.45039999   -1045992.6441-611278.42249999      -1045902.7
    -611271.4179   -1045885.7179    -611266.1565   -1045868.1018
    -611289.7162   -1045776.4242-611305.45039999   -1045611.9751
#Sta/Elev= 30
       0  346.46    2.89  346.51    8.18     345    9.45  346.88   12.39  343.88
   13.42   340.7   19.64  340.88   22.74  339.16   47.73  339.19   94.65  338.72
   96.42  337.23      97  337.23   97.03  335.75   97.05  335.55  101.17  335.51
  106.33  335.58  106.61  336.13  106.62  337.12  106.77  338.56   139.4  338.41
  154.52  339.46  170.07  339.33  184.92  339.81  232.43  339.91  325.16  339.42
  364.15  340.47  382.07  344.81  385.76  345.26  388.95  344.19  390.53  344.47
#Mann= 3 , 0 , 0
       0      .1       0   94.65    .035       0  106.77     .08       0
#Block Obstruct= 5 ,-1
   28.71   47.42342.1049  284.31  323.33  342.54  240.64  252.95342.8019
     147  173.73342.1931  130.67  132.27  341.52
Bank Sta=94.65,106.77
XS Rating Curve= 0 ,0
Exp/Cntr=0.3,0.1

Type RM Length L Ch R = 1 ,15681.9 ,45.84,50,51.56
XS GIS Cut Line= 4
-611311.56309999   -1045988.0799    -611292.5808   -1045894.7576
-611286.29859999   -1045878.4296-611316.05409999   -1045626.6029
#Sta/Elev= 30
       0  346.88     .04  346.88     .49  345.31    3.76  345.57    4.88  341.26
    9.43  340.89   12.96  340.97   21.06  339.55   21.88  339.03   39.45  339.14
    59.2   338.9   84.71  338.27   93.97  338.39   99.23  335.91  100.76  335.82
  106.56  335.98  108.28  337.14  109.04  338.31  124.79  338.24  146.31  338.95
   163.9  338.73  164.34  339.68  176.38  339.83   221.8  339.76  252.17  339.34
  260.89  339.58  272.13  339.58  312.67  339.33  350.37  340.37  366.31  344.55
#Mann= 3 , 0 , 0
       0      .1       0   93.97    .035       0  109.04     .08       0
#Block Obstruct= 6 ,-1
   27.52   35.49342.0646  271.67  310.54342.4639  152.57  164.87342.2979
    50.8   60.03341.9404  122.69  126.81341.3354  128.89  146.45341.3354
Bank Sta=93.97,109.04
XS Rating Curve= 0 ,0
Exp/Cntr=0.3,0.1

Type RM Length L Ch R = 1 ,15561.9 ,53.46,64.01,67.42
XS GIS Cut Line= 4
    -611358.8707   -1045988.0799    -611405.7524    -1045878.675
    -611406.3202   -1045860.2644    -611458.7895   -1045675.2631
#Sta/Elev= 30
       0   341.7    4.67   338.9   26.16   338.6   59.88  337.86   80.08  337.85
   90.31  338.07  106.36  337.78  119.03  336.85  122.37   336.7  124.27  335.48
  124.95  335.22  125.54  335.16  130.74  335.17  135.33  337.56  143.34  337.94
  147.09  337.98  153.27  338.51  156.65  338.68  168.99  338.86  184.41  338.77
  191.45  341.07  198.78  340.67  200.07  340.32   200.5  340.32  205.32  338.97
  229.63  338.84  253.98  338.88  316.49  339.24  324.73  343.67  329.74  346.06
#Mann= 3 , 0 , 0
       0      .1       0  122.37     .05       0  135.33     .08       0
#Block Obstruct= 3 ,-1
  205.92  209.34341.9575  240.57  312.66341.9575  149.11  173.16341.4943
Bank Sta=122.37,135.33
XS Rating Curve= 0 ,0
Exp/Cntr=0.3,0.1

Type RM Length L Ch R = 1 ,15373.89,10.94,373.89,55.99
XS GIS Cut Line= 4
    -611518.3532   -1046080.6446    -611558.4674   -1045974.2846
    -611559.0168   -1045956.5783    -611651.2961   -1045753.4009
#Sta/Elev= 30
       0  343.98   26.39  344.25   30.94  343.01   32.25  343.44   38.14  337.33
   39.14  337.26   75.35  336.23  104.09  337.28  106.16  336.36  115.99335.9734
  118.79  334.82  119.65  333.61  122.73  333.49  126.44  333.51  135.86335.6363
  188.19   337.2  221.15  337.22     225  338.55  234.88  338.93  238.98  338.34
  239.94  337.57  266.18  336.86  267.23  337.66  300.91  337.46  302.96  338.59
  306.04   337.9  323.77  337.86  327.58  339.11  337.36  338.91  354.54  346.96
#Mann= 3 , 0 , 0
       0      .1       0  115.99     .05       0  135.86     .08       0
#Block Obstruct= 1 ,-1
   15.15   25.12347.0693
Bank Sta=115.99,135.86
XS Rating Curve= 0 ,0
Exp/Cntr=0.3,0.1
LCMann Table=0

--- PPO_Kvasiny_efektiv.g05 (geometry) ---

Geom Title=A2
Program Version=5.03

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
River Reach=Bela            ,Bela_reach

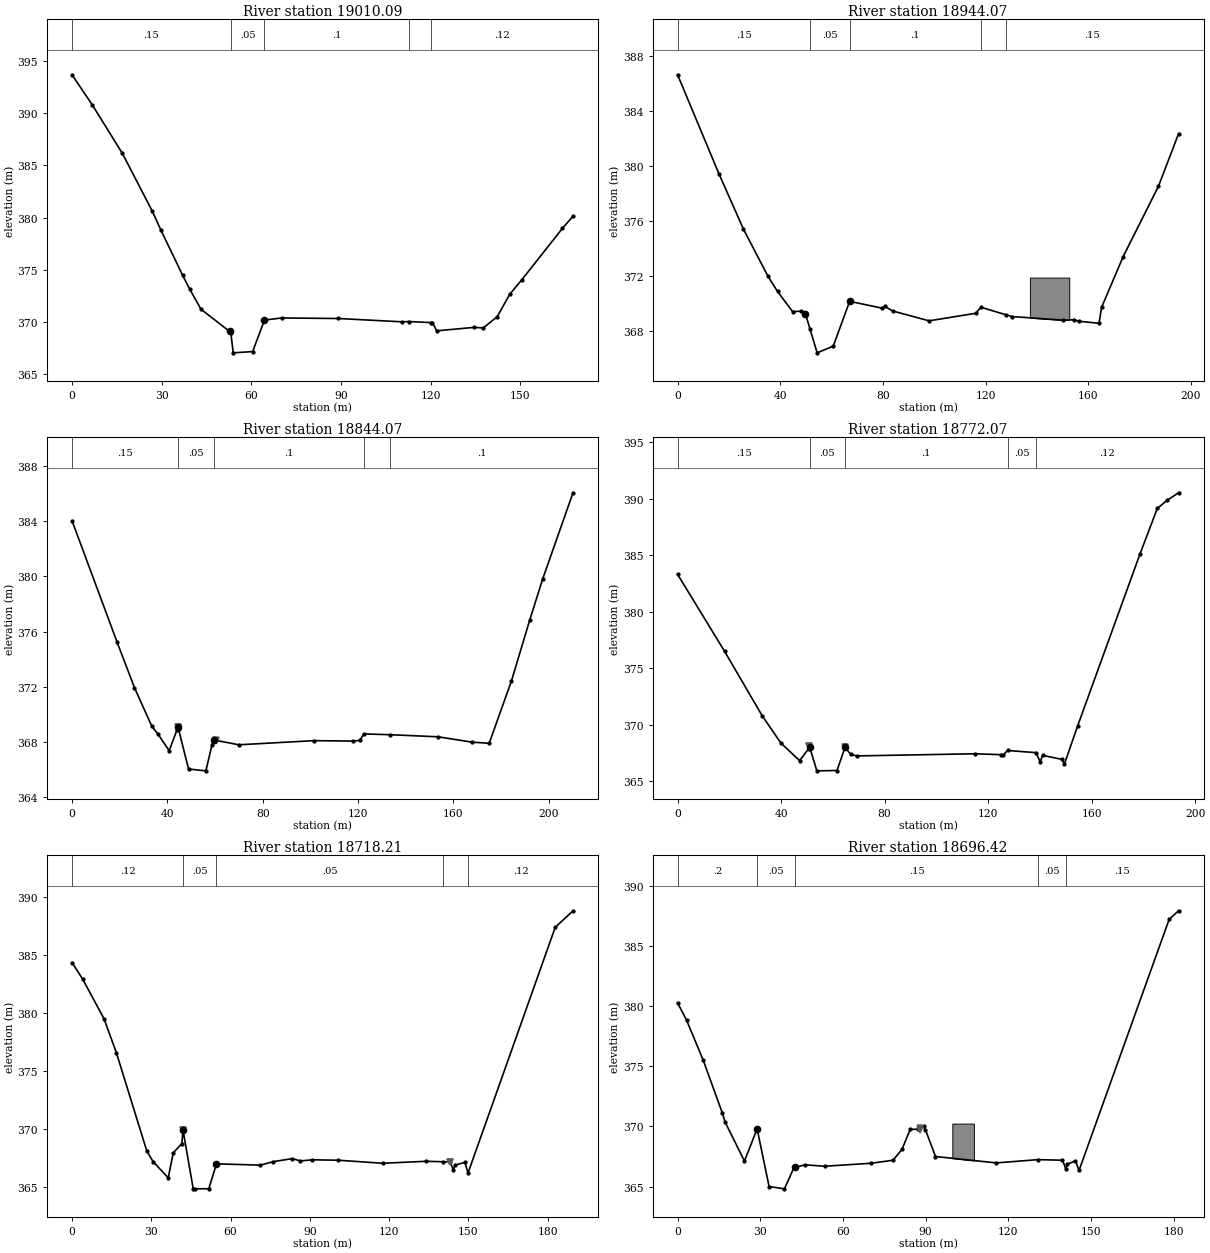
Type RM Length L Ch R = 1 ,19010.09,63.81,66.01,58.86
XS GIS Cut Line= 5
-608502.66209999   -1044593.6857    -608536.6251   -1044560.8986
     -608549.118   -1044545.2805    -608586.5786   -1044508.0775
     -608607.896   -1044465.4426
#Sta/Elev= 27
       0  393.68    6.75  390.81   16.83  386.16    26.9  380.59   29.66  378.85
   36.98  374.49   39.39  373.14   43.16  371.22   52.73  369.09   53.15 368.985
   53.94  367.04   60.45  367.16    64.4370.1805   70.18  370.38   89.09  370.33
   110.6  370.01  112.68  370.04     120  369.94  120.58  369.94  122.07  369.15
  134.59  369.48  137.58  369.42  142.28  370.49  146.47  372.64  150.45  374.01
  164.12  378.96  167.67  380.13
#Mann= 5 ,-1 , 0
       0     .15       0   53.15     .05       0    64.4      .1       0
  112.68     .05       0     120     .12       0
Bank Sta=52.73,64.4
XS Rating Curve= 0 ,0
Exp/Cntr=0.3,0.1

Type RM Length L Ch R = 1 ,18944.07,107.06,100,81.52
XS GIS Cut Line= 5
    -608546.4782   -1044642.7763-608578.86259999   -1044608.0005
     -608594.864   -1044596.0024    -608642.9144   -1044514.1948
    -608653.0656   -1044483.0645
#Sta/Elev= 29
       0  386.63   16.09  379.43   25.66  375.39   35.22  371.96   38.92  370.86
   44.79  369.39   48.23  369.42    49.8  369.23   51.56368.1339   54.36  366.39
   60.63  366.88   67.02  370.14   67.03370.1393   79.71  369.64   80.76  369.77
   83.72  369.44   97.93  368.72  116.15  369.27  118.16  369.71   127.9369.1595
  130.38  369.03  150.14  368.77  154.47   368.8  156.24  368.69  164.17  368.54
  165.15   369.7  173.57   373.4  187.32  378.52  195.14  382.34
#Mann= 5 ,-1 , 0
       0     .15       0   51.56     .05       0   67.03      .1       0
  118.16     .05       0   127.9     .15       0
#Block Obstruct= 1 ,-1
  137.23  152.56371.8682
Bank Sta=49.8,67.02
XS Rating Curve= 0 ,0
Exp/Cntr=0.3,0.1

Type RM Length L Ch R = 1 ,18844.07,72.16,72,73.34
XS GIS Cut Line= 6
-608649.34349999   -1044712.1427    -608661.1943   -1044671.2681
    -608666.6842   -1044652.0363-608687.57959999     -1044587.96
    -608711.2657   -1044551.4157    -608740.0273   -1044528.7448
#Sta/Elev= 27
       0  384.04   18.89  375.24   26.18  371.94   33.47  369.13    35.9   368.6
   40.75  367.36   44.03  368.88   44.35  369.09   44.67  368.93   48.88  366.03
   56.14   365.9   58.65  367.74   59.34  368.14   59.46368.1367   70.03  367.79
  101.43  368.09     118  368.06  120.69  368.11  122.41  368.58  133.48  368.52
  153.46  368.37  167.81  367.98  174.98   367.9  184.29  372.41  191.95  376.82
  197.36  379.79  210.13  386.07
#Mann= 5 ,-1 , 0
       0     .15       0   44.35     .05       0   59.46      .1       0
  122.41     .05       0  133.48      .1       0
Levee=-1,44.3,369.1,-1,60.19,368.06,,
Bank Sta=44.35,59.46
XS Rating Curve= 0 ,0
Exp/Cntr=0.3,0.1

Type RM Length L Ch R = 1 ,18772.07,49.5,53.87,46.34
XS GIS Cut Line= 5
-608717.01799999   -1044739.5508    -608729.3973    -1044693.413
    -608735.3242   -1044674.3114    -608762.3599   -1044598.1112
    -608783.6774   -1044558.5216
#Sta/Elev= 27
       0  383.29   18.17  376.48   32.67  370.79   39.91  368.37   47.16  366.81
   50.67  367.88   50.91  368.11   50.99368.0506   53.81  365.91    61.6  365.94
    64.7367.9844   66.95  367.36   69.23  367.23  114.85  367.42     125  367.34
  125.72  367.28   127.5  367.71  138.51  367.52  140.12  366.69  141.02  367.28
  148.38  366.93  149.49  366.52  154.63  369.91  178.71  385.11  185.36  389.12
  189.15  389.84  193.59  390.51
#Mann= 5 ,-1 , 0
       0     .15       0   50.99     .05       0    64.7      .1       0
   127.5     .05       0  138.51     .12       0
Levee=-1,50.87,368.11,-1,64.69,367.98,,
Bank Sta=50.99,64.7
XS Rating Curve= 0 ,0
Exp/Cntr=0.3,0.1

Type RM Length L Ch R = 1 ,18718.21,29.06,21.79,6.52
XS GIS Cut Line= 5
-608753.54699999   -1044753.4637     -608781.487   -1044705.5211
    -608789.4245   -1044670.2786    -608798.9496    -1044622.336
-608821.80959999   -1044578.8384
#Sta/Elev= 30
       0  384.35    4.01  382.93   12.11  379.51   16.79  376.59   28.31  368.13
   30.69  367.22   36.42  365.83   38.32  367.98   41.56  368.77   42.02  369.93
   45.86   364.9   46.37  364.88   51.77  364.89   54.68  367.03   71.29  366.92
    76.2  367.22   83.37  367.48   86.48  367.28   90.94  367.38  100.86  367.34
  117.53  367.08  134.11  367.25  140.49  367.21  143.13   367.2  144.27  366.52
  144.99  366.93  148.71  367.15  149.91  366.25  182.91  387.38  189.63   388.8
#Mann= 5 ,-1 , 0
       0     .12       0   42.02     .05       0   54.68     .05       0
  140.49     .05       0  149.91     .12       0
Levee=-1,42.02,369.93,-1,142.96,367.15,,
Bank Sta=42.02,54.68
XS Rating Curve= 0 ,0
Exp/Cntr=0.3,0.1

Type RM Length L Ch R = 1 ,18696.42,50.22,38.35,4.09
XS GIS Cut Line= 4
-608796.05849999    -1044760.252    -608795.7939   -1044693.8414
    -608803.2023   -1044622.1392    -608824.1044   -1044584.3037
#Sta/Elev= 30
       0  380.28    3.25  378.85    9.27  375.53   16.25  371.11   17.25  370.36
   24.25  367.12   28.85   369.8   33.19     365   38.76  364.81   42.24  366.59
    42.5  366.59   46.19  366.81   53.31  366.69   70.21  366.94   78.14  367.19
   81.39  368.09   84.36  369.75   87.08  369.78   89.29     370   89.92  369.72
   93.55   367.5  115.58  366.97  130.78  367.24  139.61  367.19  140.83  366.48
  141.43  366.87  144.32  367.13  145.62  366.34   178.3  387.23  181.72  387.95
#Mann= 5 ,-1 , 0
       0      .2       0   28.85     .05       0    42.5     .15       0
  130.78     .05       0  140.83     .15       0
Levee=0,,,-1,87.99,369.73,,
#Block Obstruct= 1 ,-1
   99.66  107.48370.2419
Bank Sta=28.85,42.5
XS Rating Curve= 0 ,0
Exp/Cntr=0.3,0.1

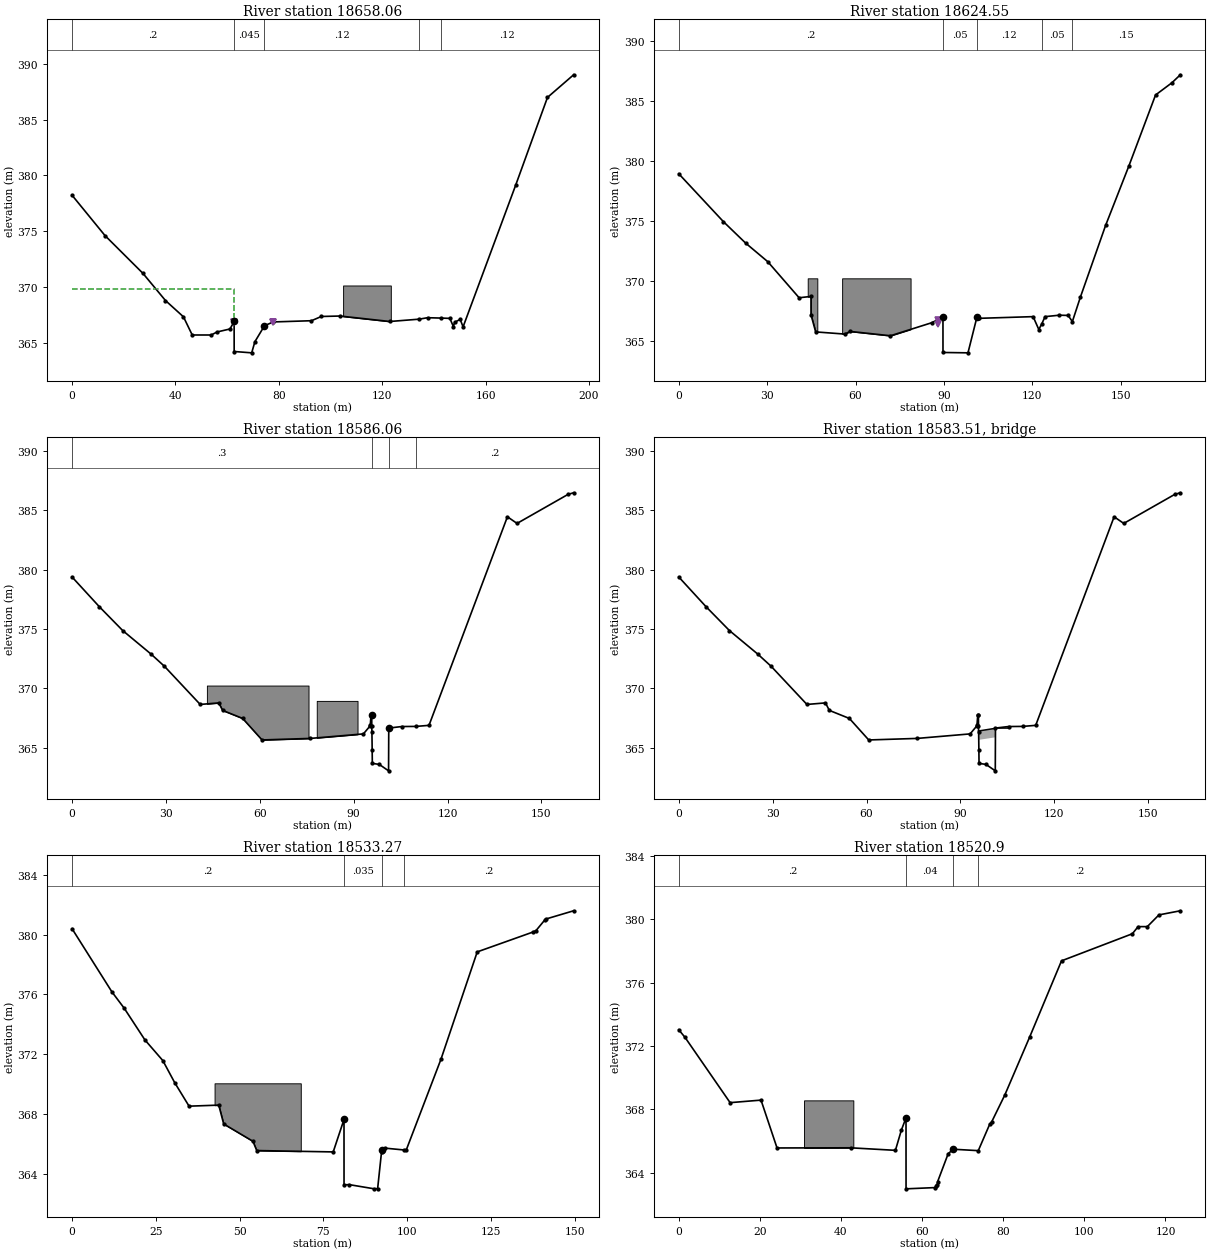
Type RM Length L Ch R = 1 ,18658.06,22,33.51,26.87
XS GIS Cut Line= 6
-608811.08549999    -1044755.116     -608825.589   -1044701.0257
    -608807.8792   -1044691.7325-608803.30299999   -1044664.7705
    -608806.6867   -1044622.1356-608834.09479999   -1044582.8844
#Sta/Elev= 30
       0  378.22   12.72  374.61   27.41  371.22   36.15  368.78    43.1  367.32
    46.5  365.69   53.84  365.69   56.09  365.96   61.11  366.23   62.71   366.9
   62.73  364.21   69.51  364.09   70.75  365.09   74.46366.5206   77.86  366.86
   92.64  366.97   96.45  367.35  103.66  367.39  122.92   366.9  134.34  367.11
  137.58  367.24   142.8367.2064  146.19  367.18  147.55  366.45  148.03  366.83
  150.17  367.09  151.31  366.42  171.67  379.13  183.96  386.99  194.08  389.02
#Mann= 5 ,-1 , 0
       0      .2       0   62.71    .045       0   74.46     .12       0
  134.34     .05       0   142.8     .12       0
Levee=-1,62.62,366.83,-1,77.85,366.86,,
#XS Ineff= 2 , 0
           62.66  369.79
Permanent Ineff=
       F       F
#Block Obstruct= 1 ,-1
  104.88  123.34370.1295
Bank Sta=62.71,74.46
XS Rating Curve= 0 ,0
Exp/Cntr=0.3,0.1

Type RM Length L Ch R = 1 ,18624.55,27.54,38.49,47.2
XS GIS Cut Line= 6
    -608813.3292   -1044757.0751-608830.65819999   -1044713.3605
     -608838.708   -1044671.6675    -608829.9133   -1044663.7088
    -608830.5483   -1044653.6758    -608851.3869   -1044598.6741
#Sta/Elev= 30
       0  378.92   15.14  374.94   22.67  373.16    30.2  371.61   40.84  368.61
   44.87  368.72   44.88  367.19   46.46  365.77   56.35  365.59   58.15  365.81
   71.85  365.45   85.93  366.54   89.66  367.02   89.67  364.06   98.15  364.03
   101.2  367.01  101.96   366.9  120.26  367.04  122.19  365.97  123.18  366.43
  124.31  367.04  129.18  367.16  132.12  367.14  133.58  366.63  136.31  368.67
  144.85  374.62  152.76  379.57  161.81  385.47  167.38  386.49  170.22  387.15
#Mann= 5 ,-1 , 0
       0      .2       0   89.66     .05       0   101.2     .12       0
  123.18     .05       0  133.58     .15       0
Levee=-1,87.92,366.43,0,,,,
#Block Obstruct= 2 ,-1
   43.76   47.02 370.226   55.44   78.67 370.226
Bank Sta=89.66,101.2
XS Rating Curve= 0 ,0
Exp/Cntr=0.3,0.1

Type RM Length L Ch R = 1 ,18586.06,7.01,7,6.98
XS GIS Cut Line= 5
-608816.16099999   -1044758.1613-608829.69599999   -1044721.9555
-608861.31879999   -1044682.8263    -608874.4763   -1044667.7636
    -608911.2437   -1044631.9484
#Sta/Elev= 30
       0  379.37    8.71  376.87   16.19  374.86   25.24  372.88   29.53  371.85
   40.95  368.64   46.89  368.77   48.11  368.14   54.53  367.46   60.71  365.65
    76.2  365.78   93.11  366.16   95.27  366.84   95.31  366.91   95.55  367.76
   95.77  367.75   95.78  366.84   95.83  366.33   95.91   364.8   95.96  363.68
   98.19  363.59  101.15  363.05  101.21  366.65  105.39  366.78   109.9  366.79
  114.07  366.88  139.13  384.44  142.21  383.88  158.54  386.33  160.29  386.46
#Mann= 4 ,-1 , 0
       0      .3       0   95.77    .035       0  101.21     .05       0
   109.9      .2       0
#Block Obstruct= 2 ,-1
   43.09   75.57370.2309    78.2   91.23368.9392
Bank Sta=95.77,101.21
XS Rating Curve= 0 ,0
Exp/Cntr=0.5,0.3

Type RM Length L Ch R = 3 ,18583.51,,,
BEGIN DESCRIPTION:
18779.9  PF 244 SILNIÈNÍ ŽLB MOSTEK F.PORKET
END DESCRIPTION:
Bridge Culvert--1,0,-1,-1, 0
Deck Dist Width WeirC Skew NumUp NumDn MinLoCord MaxHiCord MaxSubmerge Is_Ogee
0.2,6.6,1.4,0, 4, 4, , , 0.98, 0, 0,0,,
    95.8   95.89  101.67     105
  366.41  366.41  366.65  366.65
  365.66  365.66  365.89  365.89
      95   95.89  101.67     105
  366.41  366.41  366.65  366.65
  365.66  365.66  365.89  365.89
BR Coef= 1 , 0 , 0 ,, 0 ,,,0.8,-1,1,0,
WSPro=,,,, 1 ,,,, 0 ,,,, 0 ,,,,-1 ,-1 ,-1 , 0 , 0 , 0 , 0 , 0
BC Design=,, 0 ,, 0 ,,,,,,
BC HTab HWMax=368.5
BC HTab TWMax=367.5
BC HTab MaxFlow=80
BC Use User HTab Curves=0
BC User HTab FreeFlow(D)= 51
              0.         363.053           0.305         363.709
           0.763         363.796           1.832         363.921
           3.053         364.022            4.58         364.119
           6.107         364.196           7.633         364.262
            9.16         364.333          10.687         364.401
          12.214         364.462           13.74         364.523
          15.267         364.579          16.794         364.634
           18.32         364.686          19.847         364.738
          21.374         364.787            22.9         364.837
          24.427         364.939          25.954         364.987
          27.481          365.09          29.007         365.136
          30.534         365.209          32.061         365.281
          33.587         365.352          35.114         365.423
          36.641         365.492          38.167         365.558
          39.694         365.613          41.221         365.673
          42.747         365.727          44.274         365.777
          45.801         365.838          47.328         365.889
          48.854         365.946          50.487         366.013
          52.175         366.075          53.919         366.151
          55.721         366.283          57.584         366.413
          59.508         366.545          61.497         366.686
          63.553         366.871          65.677         367.183
          67.873         367.443          70.141         367.667
          72.486         367.879          74.909         368.086
          77.412         368.292             80.         368.292
            80.8           368.5
BC User HTab Sub Curve(D)= 7
              0.         363.667           0.133         363.676
            0.19         363.684           0.247         363.695
            0.29         363.704           0.304         363.707
           0.304         363.707
BC User HTab Sub Curve(D)= 8
              0.         363.745           0.218          363.75
           0.392          363.76           0.435         363.764
           0.479         363.767           0.522         363.771
           0.566         363.775           0.677          363.78
BC User HTab Sub Curve(D)= 10
              0.         363.824            0.43         363.829
           0.688         363.837           0.774         363.841
            0.86         363.845           0.946          363.85
           1.032         363.855           1.118          363.86
           1.204         363.866           1.414         363.872
BC User HTab Sub Curve(D)= 10
              0.         363.902           0.689         363.907
           1.103         363.916           1.241          363.92
           1.379         363.924           1.517         363.929
           1.654         363.935           1.792         363.941
            1.93         363.947           2.241         363.954
BC User HTab Sub Curve(D)= 12
              0.          363.98           0.988         363.985
           1.581         363.993           1.778         363.997
           1.976         364.001           2.174         364.006
           2.371         364.012           2.569         364.018
           2.767         364.025           2.964         364.032
           3.053         364.034           3.252         364.034
BC User HTab Sub Curve(D)= 12
              0.         364.058           1.322         364.063
            2.38         364.073           2.645         364.077
           2.909         364.081           3.174         364.086
           3.438         364.092           3.702         364.098
           3.967         364.105           4.231         364.114
            4.58         364.121           4.625         364.121
BC User HTab Sub Curve(D)= 11
              0.         364.137           1.685         364.141
           3.033          364.15            3.37         364.153
           3.707         364.157           4.044         364.161
           4.381         364.166           4.718          364.17
           5.055         364.176           5.392         364.182
           5.976         364.189
BC User HTab Sub Curve(D)= 11
              0.         364.215           2.078         364.219
           3.741         364.227           4.988         364.238
           5.404         364.242            5.82         364.246
           6.235         364.252           6.651         364.257
           7.067         364.263           7.633         364.269
           7.765         364.269
BC User HTab Sub Curve(D)= 10
              0.         364.293           2.994         364.301
           3.993         364.302           4.991         364.307
           5.989         364.314           6.987         364.322
           7.985         364.332           8.983         364.344
            9.16         364.347           9.481         364.347
BC User HTab Sub Curve(D)= 8
              0.         364.371           4.708         364.379
           5.885         364.383           7.061         364.389
           8.238         364.397           9.415         364.405
          10.592         364.417          11.434         364.431
BC User HTab Sub Curve(D)= 8
              0.         364.449           5.458         364.456
           6.823          364.46           8.188         364.465
           9.552         364.471          10.917         364.479
          12.282         364.488          13.205         364.502
BC User HTab Sub Curve(D)= 6
              0.         364.528            6.24         364.533
          10.919         364.545          12.479         364.551
          14.039          364.56          15.042          364.57
BC User HTab Sub Curve(D)= 6
              0.         364.606           8.827         364.612
          14.123         364.624          15.888          364.63
          16.794         364.638          16.906         364.638
BC User HTab Sub Curve(D)= 5
              0.         364.684          11.871          364.69
          17.806           364.7           18.32         364.701
           18.75         364.701
BC User HTab Sub Curve(D)= 9
              0.         364.762          15.398         364.766
          19.798         364.773          21.998         364.831
          24.198         365.017          26.397         365.071
          28.597         365.142          30.534         365.212
          30.594         365.212
BC User HTab Sub Curve(D)= 10
              0.         364.841          21.856         364.844
          22.464         364.874          24.198         365.018
          24.284         365.022          26.713         365.135
          29.141         365.209           31.57         365.275
          32.061         365.294          32.352         365.294
BC User HTab Sub Curve(D)= 12
              0.         364.919          23.432         364.958
          23.979         365.003          24.041         365.008
          24.198          365.02          24.284         365.024
          26.713         365.136          29.141          365.21
           31.57         365.276          32.061         365.296
          32.352         365.297          32.417         365.297
BC User HTab Sub Curve(D)= 12
              0.         364.997          23.939         365.003
          24.041          365.01          24.198         365.021
           26.17         365.114          26.351         365.122
          26.713         365.138          29.141         365.212
           31.57         365.278          32.061         365.297
          32.417           365.3          32.482           365.3
BC User HTab Sub Curve(D)= 9
              0.         365.075          25.036         365.081
          26.844         365.145          27.913         365.177
          29.141         365.213           31.57         365.279
          32.061         365.299          32.482         365.303
          32.547         365.303
BC User HTab Sub Curve(D)= 7
              0.         365.153          27.176         365.159
          29.029         365.213          29.904         365.238
          32.061           365.3          32.547         365.306
          32.612         365.306
BC User HTab Sub Curve(D)= 7
              0.         365.232          29.781         365.238
          31.275         365.281          31.592          365.29
          32.061         365.302          32.612         365.309
          32.677         365.309
BC User HTab Sub Curve(D)= 2
              0.          365.31          32.751         365.313
BC User HTab Sub Curve(D)= 2
              0.         365.388          34.423         365.391
BC User HTab Sub Curve(D)= 2
              0.         365.466           36.14         365.469
BC User HTab Sub Curve(D)= 2
              0.         365.545          37.934         365.548
BC User HTab Sub Curve(D)= 3
              0.         365.623          39.694         365.626
          40.023         365.626
BC User HTab Sub Curve(D)= 2
              0.         365.701          42.102         365.704
BC User HTab Sub Curve(D)= 3
              0.         365.779          44.274         365.782
          44.399         365.782
BC User HTab Sub Curve(D)= 10
              0.         365.857          18.035         365.865
          24.047         365.867          30.058         365.874
           36.07         365.888          42.082         365.917
          48.094         365.988          54.105         366.194
          57.584         366.421          57.706         366.421
BC User HTab Sub Curve(D)= 12
              0.         365.936          12.413         365.945
          18.619          365.95          24.826         365.964
          31.032         365.986          37.239         366.025
          43.445         366.096          49.651         366.226
          55.858         366.451          62.064          366.77
          65.677         367.185          65.697         367.185
BC User HTab Sub Curve(D)= 18
              0.         366.014          12.758         366.023
          17.011         366.031          21.263         366.042
          25.516         366.057          29.768         366.078
          34.021         366.107          38.274         366.147
          42.526         366.205          46.779         366.289
          51.032         366.404          55.284          366.56
          59.537         366.762          63.789         367.147
          68.042         367.543          72.295         367.878
          72.486         367.893          72.651         367.893
BC User HTab Sub Curve(D)= 19
              0.         366.092           8.505           366.1
          12.758         366.104          17.011         366.114
          21.263         366.128          25.516         366.146
          29.768         366.172          34.021         366.206
          38.274         366.253          42.526         366.318
          46.779         366.407          51.032         366.525
          55.284         366.675          59.537         366.904
          63.789         367.282          68.042         367.632
          72.295         367.952          76.547         368.265
          77.121         368.268
BC User HTab Sub Curve(D)= 19
              0.          366.17           8.505         366.179
          12.758         366.184          17.011         366.196
          21.263         366.212          25.516         366.234
          29.768         366.263          34.021         366.302
          38.274         366.354          42.526         366.423
          46.779         366.514          51.032         366.633
          55.284         366.786          59.537         367.058
          63.789         367.395          68.042         367.713
          72.295         368.017          76.547          368.32
          80.119         368.323
BC User HTab Sub Curve(D)= 19
              0.         366.249           8.505         366.258
          12.758         366.264          17.011         366.278
          21.263         366.296          25.516          366.32
          29.768         366.353          34.021         366.395
          38.274          366.45          42.526         366.522
          46.779         366.615          51.032         366.735
          55.284         366.912          59.537         367.191
          63.789         367.495          68.042         367.789
          72.295         368.081          76.547         368.375
          80.331         368.378
BC User HTab Sub Curve(D)= 19
              0.         366.327           8.505         366.337
          12.758         366.344          17.011         366.359
          21.263         366.379          25.516         366.405
          29.768          366.44          34.021         366.485
          38.274         366.543          42.526         366.617
          46.779         366.712          51.032         366.839
          55.284         367.046          59.537         367.305
          63.789         367.584          68.042         367.863
          72.295         368.144          76.547          368.43
          80.543         368.433
BC User HTab Sub Curve(D)= 19
              0.         366.405           8.505         366.416
          12.758         366.424          17.011         366.439
          21.263         366.461          25.516         366.489
          29.768         366.526          34.021         366.572
          38.274         366.632          42.526         366.708
          46.779         366.806          51.032         366.953
          55.284         367.162          59.537         367.408
          63.789         367.668          68.042         367.933
          72.295         368.205          76.547         368.485
          80.753         368.488
BC User HTab Sub Curve(D)= 18
              0.         366.483           8.505         366.495
          12.758         366.503          17.011          366.52
          21.263         366.543          25.516         366.574
          29.768         366.612          34.021         366.661
          38.274         366.722          42.526           366.8
          46.779         366.909          51.032         367.067
          55.284         367.269          59.537           367.5
          63.789         367.746          68.042         368.002
          72.295         368.265          75.333           368.5
BC User HTab Sub Curve(D)= 19
              0.         366.561           8.058         366.572
          12.086          366.58          16.115         366.595
          20.144         366.615          24.173         366.642
          28.202         366.676           32.23          366.72
          36.259         366.775          40.288          366.85
          44.317         366.951          48.346         367.081
          52.375         367.243          56.403          367.43
          60.432         367.637          64.461         367.858
           68.49         368.092          72.519         368.338
          74.511           368.5
BC User HTab Sub Curve(D)= 19
              0.          366.64           8.058          366.65
          12.086         366.657          16.115          366.67
          20.144          366.69          24.173         366.715
          28.202         366.748           32.23         366.791
          36.259         366.849          40.288         366.928
          44.317          367.03          48.346         367.164
          52.375          367.33          56.403         367.529
          60.432         367.734          64.461         367.944
           68.49         368.165          72.519         368.395
           73.79           368.5
BC User HTab Sub Curve(D)= 19
              0.         366.718           8.058         366.727
          12.086         366.733          16.115         366.745
          20.144         366.762          24.173         366.785
          28.202         366.815           32.23         366.855
          36.259         366.908          40.288         366.979
          44.317         367.076          48.346         367.206
          52.375         367.373          56.403         367.569
          60.432         367.778          64.461          368.01
           68.49          368.24          72.519         368.474
          72.848           368.5
BC User HTab Sub Curve(D)= 20
              0.         366.796           8.058         366.805
          12.086         366.809          16.115         366.819
          20.144         366.834          24.173         366.854
          28.202         366.881           32.23         366.915
          36.259         366.963          40.288         367.027
          44.317         367.114          48.346         367.231
          52.375         367.377          53.333         367.423
          56.403         367.572          57.493         367.629
          60.432         367.781          64.461         368.016
           68.49         368.261          71.741           368.5
BC User HTab Sub Curve(D)= 24
              0.         366.874           11.45         366.883
          15.267         366.891          19.084         366.901
          22.901         366.916          26.717         366.935
          30.534          366.96          34.351         366.995
          38.168         367.041          41.984         367.105
          45.801         367.184          49.618         367.288
          52.743         367.398          53.435         367.431
          53.762         367.447          57.251         367.619
          57.528         367.634          61.068         367.821
          61.316         367.836          64.885         368.045
          66.277         368.129          68.702         368.279
          71.741         368.502          71.782         368.502
BC User HTab Sub Curve(D)= 26
              0.         366.953           11.45         366.959
          15.267         366.965          19.084         366.974
          22.901         366.985          26.717            367.
          30.534          367.02          34.351         367.046
          38.168         367.082          41.984          367.13
          45.801         367.196          49.547         367.289
          49.618         367.291          50.586         367.325
          53.435         367.434          53.652         367.445
          57.251         367.623          57.393          367.63
          61.068         367.824          61.186         367.831
          64.885         368.048          65.034         368.057
          68.702         368.282          71.741         368.503
          71.782         368.503          72.235         368.503
BC User HTab Sub Curve(D)= 28
              0.         367.031           11.45         367.039
          15.267          367.04          19.084         367.046
          22.901         367.054          26.717         367.065
          30.534         367.079          34.351         367.098
          38.168         367.124          41.984          367.16
          45.801          367.21          47.982         367.253
          49.618         367.294          49.854         367.303
          53.435         367.437          53.532         367.442
          57.251         367.626          57.328          367.63
          61.068         367.827          61.144         367.832
          64.885         368.051          64.958         368.055
          68.702         368.285          71.741         368.505
          71.782         368.505          72.235         368.505
          72.519         368.505          73.398         368.505
BC User HTab Sub Curve(D)= 24
              0.         367.109          12.758         367.116
          17.011         367.117          21.263         367.122
          25.516          367.13          29.768          367.14
          34.021         367.154          38.274         367.174
          42.526         367.202          46.779         367.244
          48.976         367.281          51.032          367.35
          51.136         367.354          55.284         367.531
          55.345         367.535          59.537         367.749
          59.594         367.753          63.789          367.99
          63.842         367.993          68.042         368.248
          68.102         368.252          71.741         368.506
          72.295         368.508          73.894         368.508
BC User HTab Sub Curve(D)= 22
              0.         367.187          16.115         367.192
          28.202         367.205           32.23         367.213
          36.259         367.223          40.288         367.238
          44.317         367.257          48.346         367.284
          50.201         367.325          52.375          367.41
          52.446         367.413          56.403         367.592
          56.462         367.595          60.432         367.803
          60.486         367.806          64.461         368.033
          64.511         368.036           68.49         368.282
          68.533         368.285          71.741         368.508
          72.519         368.511          75.823         368.511
BC User HTab Sub Curve(D)= 23
              0.         367.265          20.144          367.27
           32.23         367.281          36.259         367.288
          40.288         367.297          44.317         367.309
          48.346         367.326          50.881         367.355
          52.375         367.413          52.445         367.416
          56.403         367.595          56.462         367.598
          60.432         367.806          60.486         367.809
          64.461         368.036          64.511          368.04
           68.49         368.285          68.533         368.286
          71.741         368.509          72.519         368.512
          75.823         368.512            80.8         368.512
            80.8         368.512
BC User HTab Sub Curve(D)= 21
              0.         367.344          25.516         367.349
          38.274          367.36          42.526         367.367
          46.779         367.376          51.032         367.388
           51.81         367.394          55.284         367.547
          55.351          367.55          59.537         367.762
          59.595         367.765          63.789         368.001
          63.843         368.004          68.042          368.26
          68.091         368.263           68.49         368.286
          68.533         368.288          71.741         368.511
          72.519         368.514            80.8         368.515
            80.8         368.515
BC User HTab Sub Curve(D)= 19
              0.         367.422          29.768         367.426
          42.526         367.434          46.779          367.44
          51.032         367.447          53.105         367.454
          55.284          367.55          55.351         367.553
          59.537         367.765          59.595         367.768
          63.789         368.004          63.842         368.007
          68.042         368.263          68.091         368.266
           68.49         368.288          68.533         368.289
          71.741         368.512          72.519         368.515
            80.8         368.518
BC User HTab Sub Curve(D)= 17
              0.           367.5          38.274         367.504
          51.032          367.51           54.45         367.517
          55.284         367.553          55.351         367.557
          59.537         367.768          59.594         367.771
          63.789         368.007          63.842          368.01
          68.042         368.266           68.09         368.269
           68.49         368.289          68.533         368.291
          71.741         368.514          72.519         368.517
            80.8         368.522

Type RM Length L Ch R = 1 ,18533.27,12.87,12.37,12.43
XS GIS Cut Line= 4
    -608836.7278   -1044771.9928-608886.99879999   -1044726.4844
    -608909.2238   -1044709.0218    -608949.4406   -1044673.5676
#Sta/Elev= 29
       0   380.4   11.91  376.17   15.57  375.08   21.75  372.96   27.09  371.58
   30.64   370.1   34.92  368.53   43.78   368.6   45.25  367.34   53.98  366.18
   55.12  365.56   77.94  365.47   81.16  367.64   81.17  363.27   82.75  363.28
   90.22     363    91.2  363.02   92.37  365.49   92.53   365.6   93.52  365.72
   99.07   365.6   99.74   365.6   110.1  371.67  120.92  378.85  137.46  380.17
  138.48  380.28  141.03  380.97  141.59  381.06  149.69   381.6
#Mann= 4 ,-1 , 0
       0      .2       0   81.16    .035       0   92.53     .05       0
   99.07      .2       0
#Block Obstruct= 1 ,-1
   42.53   68.26370.0591
Bank Sta=81.16,92.53
XS Rating Curve= 0 ,0
Exp/Cntr=0.3,0.1

Type RM Length L Ch R = 1 ,18520.9 ,21.89,22.29,22.52
XS GIS Cut Line= 4
    -608863.4842   -1044765.4406-608906.08109999   -1044727.1808
-608921.42689999     -1044715.01    -608957.6926   -1044685.3842
#Sta/Elev= 27
       0  373.03    1.54  372.55   12.66  368.43   20.28  368.59   24.23  365.57
   42.35  365.58   53.42  365.42   54.89   366.7   56.03  367.47   56.04  362.99
   63.28  363.07   63.48   363.2   63.73  363.25   63.82  363.44   66.43  365.21
   67.69  365.49   73.85   365.4   76.67  367.07   77.16  367.22   80.37   368.9
    86.5  372.56   94.37  377.38  111.84  379.09  113.26  379.54  115.53  379.54
  118.39  380.28  123.67  380.54
#Mann= 4 ,-1 , 0
       0      .2       0   56.03     .04       0   67.69     .05       0
   73.85      .2       0
#Block Obstruct= 1 ,-1
   30.89   43.04368.5746
Bank Sta=56.03,67.69
XS Rating Curve= 0 ,0
Exp/Cntr=0.3,0.1