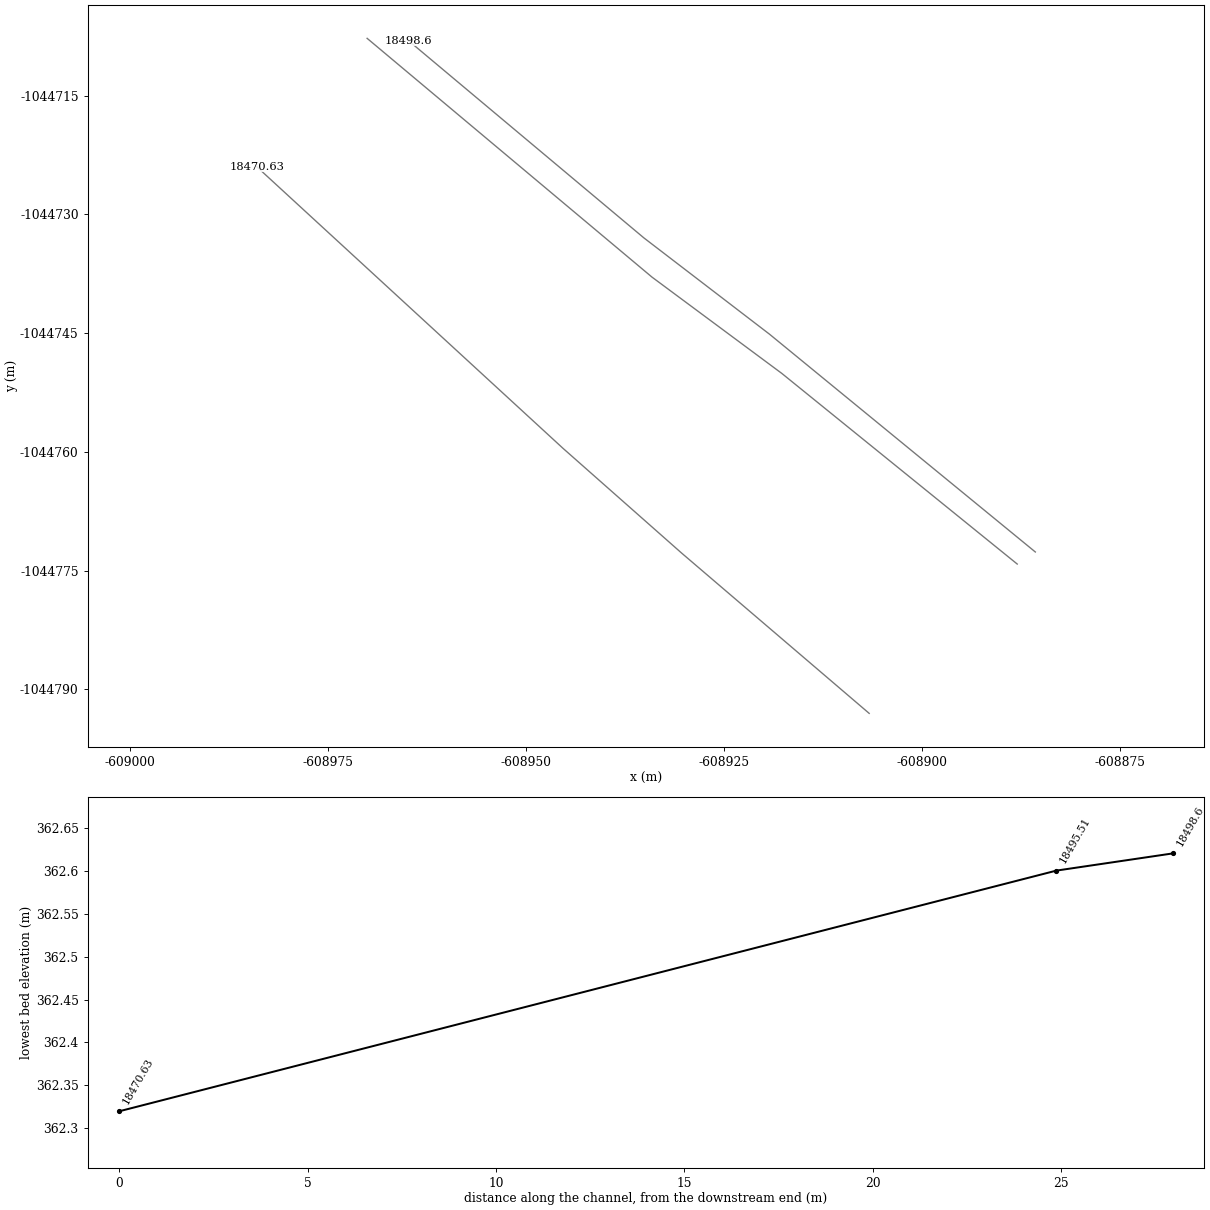
HEC-RAS study PPO_Kvasiny_efektiv.prj: PPO_Kvasiny_efektivita

--- PPO_Kvasiny_efektiv.g05 (geometry) --- (continued)

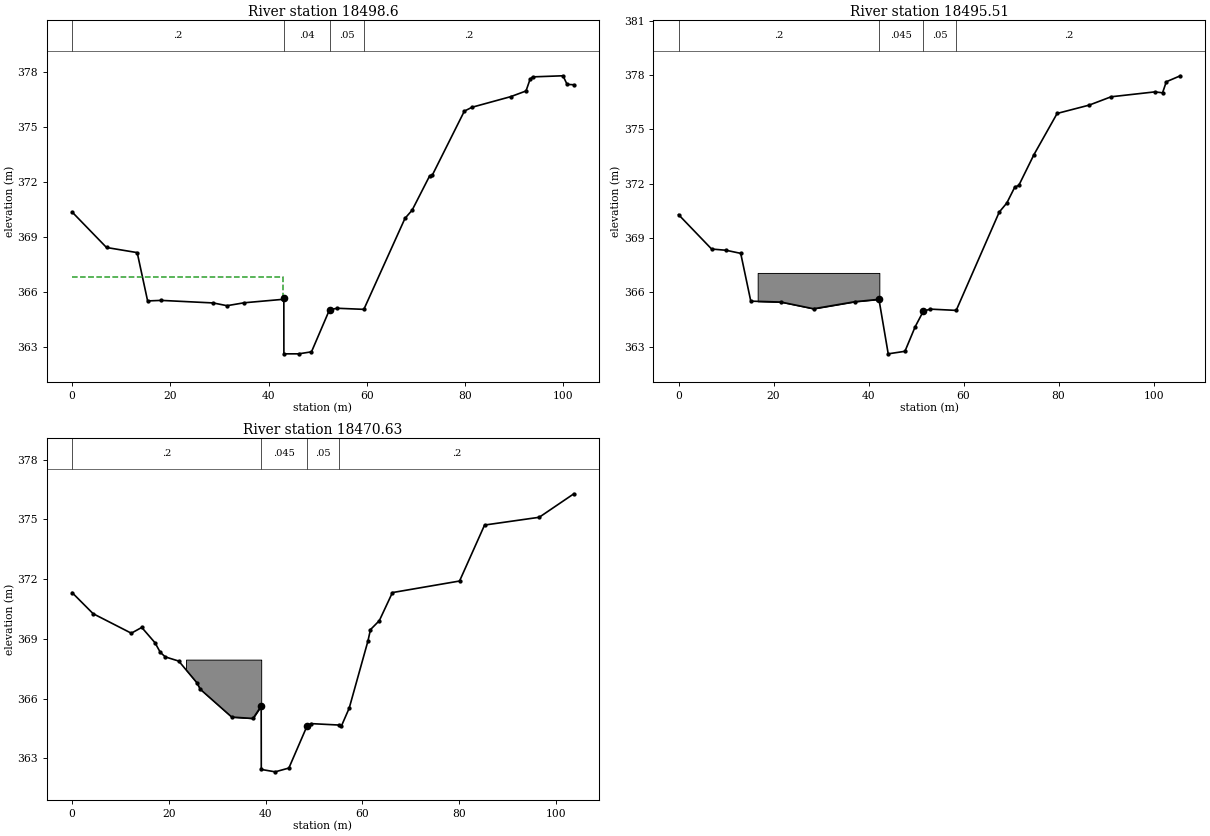
Type RM Length L Ch R = 1 ,18498.6 ,2.83,3.09,3.31
XS GIS Cut Line= 4
    -608885.6669   -1044772.6373    -608919.2351   -1044745.1325
    -608935.1101   -1044732.9616    -608964.8046   -1044708.0749
#Sta/Elev= 29
       0  370.37    7.01  368.43   13.26  368.15   15.38  365.51   18.15  365.54
   28.73   365.4   31.54  365.25   35.05  365.41   43.04   365.6   43.11  365.66
   43.12  362.62   46.14  362.62   48.74  362.73   52.41  365.03   53.99  365.11
    59.4  365.05   67.77  370.02   69.23  370.47   72.79  372.34   73.35  372.39
   79.86  375.88   81.41  376.09    89.3  376.67   92.41  376.98   93.25  377.63
   93.77  377.75   99.93  377.81  100.78  377.34  102.15  377.32
#Mann= 4 ,-1 , 0
       0      .2       0   43.11     .04       0   52.41     .05       0
    59.4      .2       0
#XS Ineff= 2 , 0
           42.92  366.84
Permanent Ineff=
       F       F
Bank Sta=43.11,52.41
XS Rating Curve= 0 ,0
Exp/Cntr=0.3,0.1

Type RM Length L Ch R = 1 ,18495.51,25.6,24.88,23.57
XS GIS Cut Line= 4
    -608887.9529   -1044774.1613    -608917.6792   -1044750.0879
    -608934.0835    -1044737.917    -608970.0669   -1044707.7544
#Sta/Elev= 27
       0  370.29    6.96  368.39   10.03  368.32   13.09  368.15   15.21  365.51
   21.57  365.46   28.43  365.09   37.14  365.48   42.19  365.61   44.14   362.6
   47.66  362.74   49.82   364.1   51.54  364.96   53.01  365.07   58.45     365
   67.51  370.43    69.1  370.93    70.8  371.82   71.62   371.9   74.81   373.6
    79.7  375.88   86.45  376.34   91.06   376.8  100.25  377.07  101.89  377.02
  102.68  377.63  105.63  377.96
#Mann= 4 ,-1 , 0
       0      .2       0   42.19    .045       0   51.54     .05       0
   58.45      .2       0
#Block Obstruct= 1 ,-1
   16.66   42.27367.0693
Bank Sta=42.19,51.54
XS Rating Curve= 0 ,0
Exp/Cntr=0.3,0.1

Type RM Length L Ch R = 1 ,18470.63,5.16,5.37,5.75
XS GIS Cut Line= 4
-608906.65179999   -1044793.0242    -608930.3372   -1044772.7807
-608945.32779999   -1044759.5411    -608983.9917   -1044723.9844
#Sta/Elev= 30
       0  371.32    4.35  370.26   12.24  369.28    14.4  369.57   17.14   368.8
   18.23  368.32   19.27  368.09   22.05  367.88   25.79  366.79   26.47  366.47
   32.99  365.07   37.38     365      39365.5917   39.08  365.61    39.1  362.44
   41.97  362.32    44.8  362.51   48.59  364.64   49.46  364.74   55.09  364.67
   55.62   364.6   57.27  365.52   61.13  368.88   61.66  369.46   63.49  369.91
    66.2  371.32   80.07   371.9   85.24  374.71   96.53   375.1  103.69  376.28
#Mann= 4 ,-1 , 0
       0      .2       0      39    .045       0   48.59     .05       0
   55.09      .2       0
#Block Obstruct= 1 ,-1
   23.55   39.08 367.954
Bank Sta=39.08,48.59
XS Rating Curve= 0 ,0
Exp/Cntr=0.3,0.1