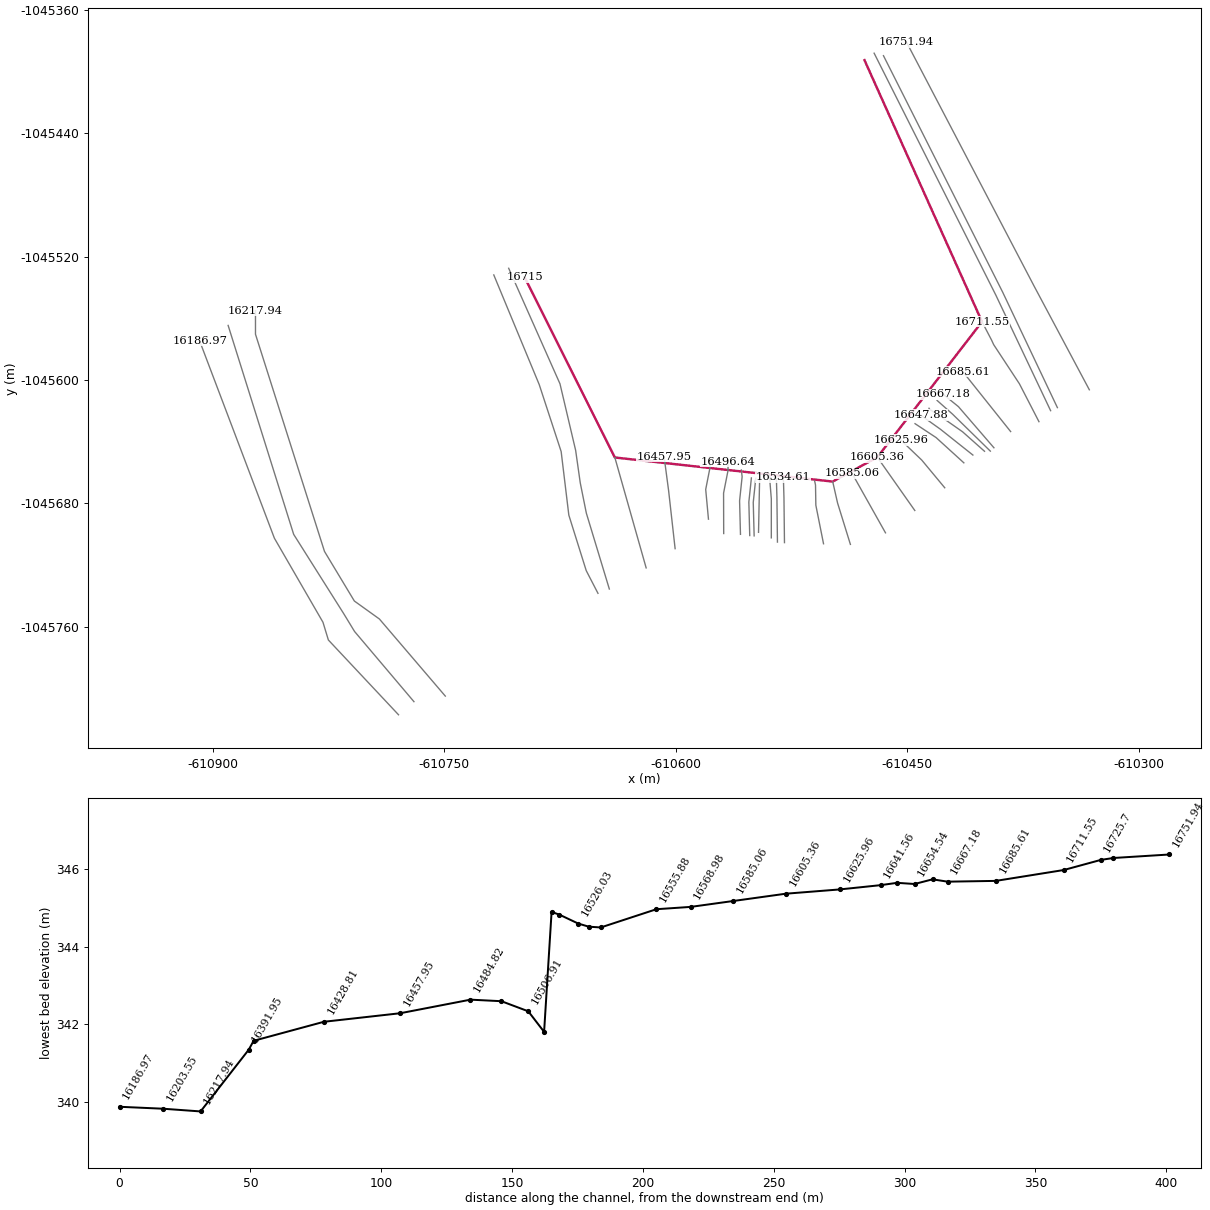
HEC-RAS study PPO_Kvasiny_efektiv.prj: PPO_Kvasiny_efektivita

--- PPO_Kvasiny_efektiv.g05 (geometry) --- (continued)

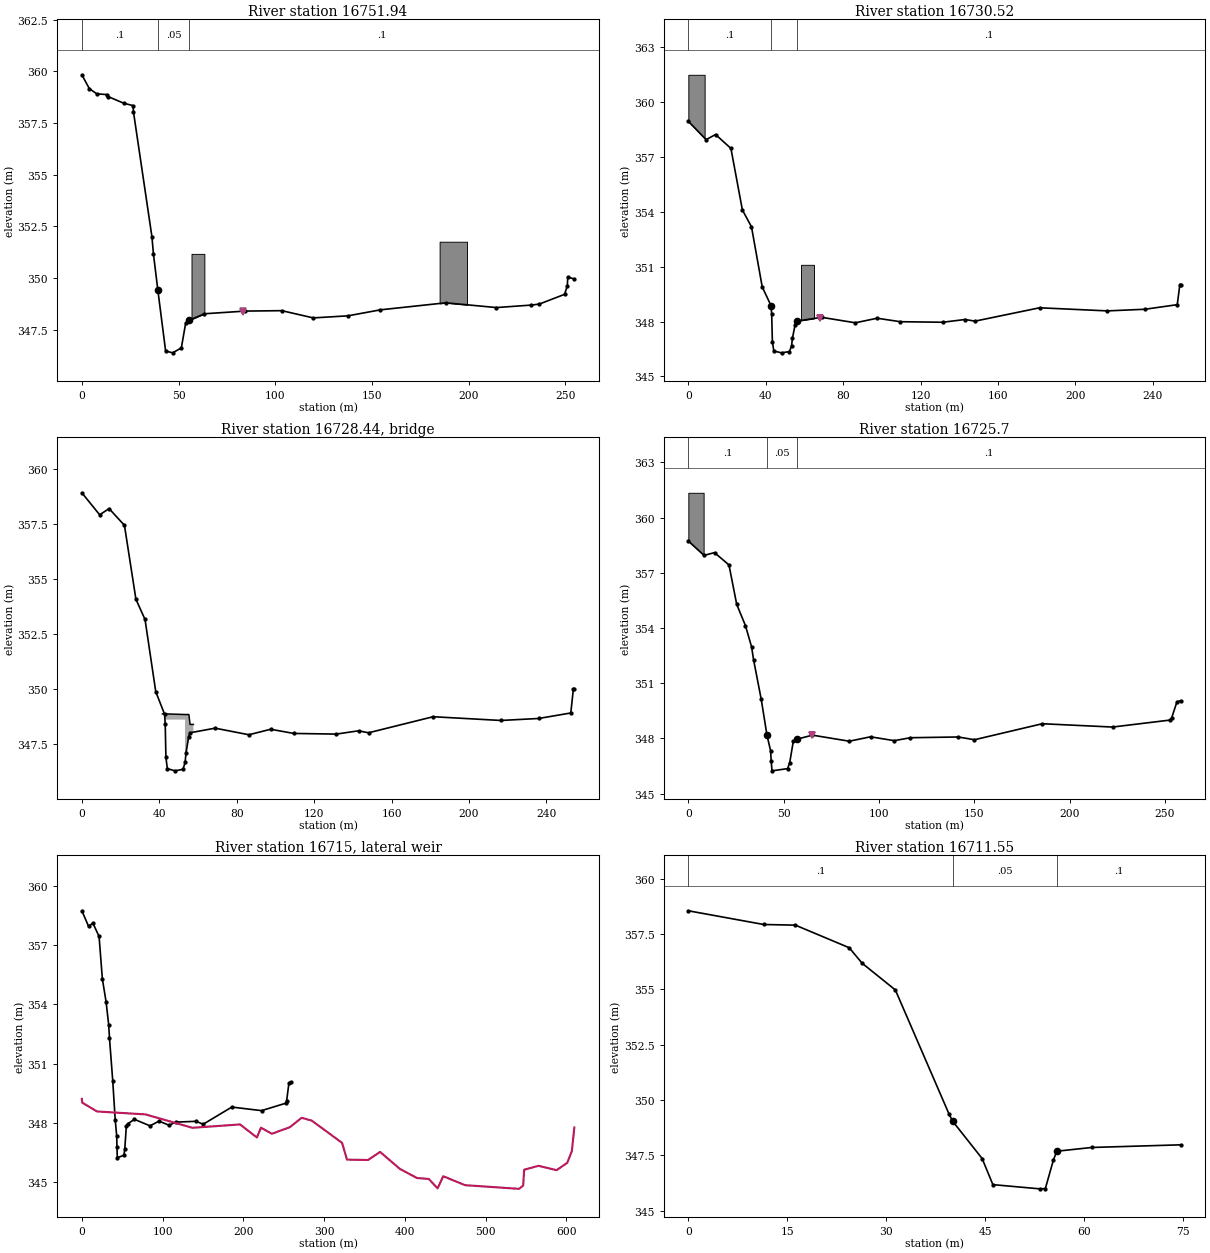
Type RM Length L Ch R = 1 ,16751.94,21.77,21.42,20.49
XS GIS Cut Line= 3
-610331.99179999   -1045606.3583     -610368.002   -1045538.7669
    -610450.4891    -1045381.048
#Sta/Elev= 30
       0  359.83    3.86  359.16    7.68  358.91    13.1  358.87   13.71  358.77
   21.76  358.45   26.44  358.34   26.69  358.03   36.22     352   37.03  351.14
    39.3   349.4    43.3  346.47   46.95  346.38   51.43  346.62   53.67  347.82
   55.59  347.96   63.34  348.27    84.5   348.4  103.36  348.42  119.61  348.07
  137.55  348.17  154.31  348.46  188.11   348.8   214.3  348.57  232.32  348.69
   236.5  348.74  249.53  349.21  250.98  349.63  251.15  350.05  254.57  349.95
#Mann= 3 , 0 , 0
       0      .1       0    39.3     .05       0   55.59      .1       0
Levee=0,,,-1,83.25,348.35,,
#Block Obstruct= 2 ,-1
  184.93  199.08351.7553   56.68   63.33351.1675
Bank Sta=39.3,55.59
XS Rating Curve= 0 ,0
Exp/Cntr=0.3,0.1

Type RM Length L Ch R = 1 ,16730.52,4.86,4.82,4.85
XS GIS Cut Line= 3
    -610352.6812   -1045617.9347-610388.15709999   -1045543.0952
    -610465.3939   -1045389.8634
#Sta/Elev= 30
       0  358.93    9.19  357.93   14.08  358.21   22.01  357.45   27.93  354.09
   32.64  353.17   38.18  349.89   42.75  348.86   43.07   348.4   43.43   346.9
   44.17  346.39   48.14  346.29   52.25  346.36   53.34  346.67   53.78  347.08
   55.17  347.83   55.91  348.02   68.85  348.23    86.3  347.93   97.54  348.18
  109.47  347.99  131.38  347.96  142.98  348.11   148.1  348.02  181.48  348.75
  216.45  348.58  235.97  348.67  252.59  348.92  253.94  350.02  254.42  350.01
#Mann= 3 , 0 , 0
       0      .1       0   42.75     .05       0   55.91      .1       0
Levee=0,,,-1,67.9,348.17,,
#Block Obstruct= 2 ,-1
       0    8.43361.4715   58.22   64.91351.0959
Bank Sta=42.75,55.91
XS Rating Curve= 0 ,0
Exp/Cntr=0.5,0.3

Type RM Length L Ch R = 3 ,16728.44,,,
Bridge Culvert--1,0,-1,-1, 0
Deck Dist Width WeirC Skew NumUp NumDn MinLoCord MaxHiCord MaxSubmerge Is_Ogee
1,1.6,1.4,0, 6, 6, , , 0.98, 0, 0,0,,
   41.62   43.12   53.32   55.29    55.9   57.62
  348.88  348.88  348.85  348.85   348.4   348.4
          348.62  348.62
   41.45   42.95   53.15   55.12   55.73   57.45
  348.88  348.88  348.85  348.85   348.4   348.4
          348.62  348.62
BR Coef=-1 , 0 , 0 ,, 0 ,,,0.8,-1,,0,
WSPro=,,,, 1 ,,,, 0 ,,,, 0 ,,,,-1 ,-1 ,-1 , 0 , 0 , 0 , 0 , 0
BC Design=,, 0 ,, 0 ,,,,,,
BC HTab HWMax=350
BC HTab TWMax=349.9
BC HTab MaxFlow=80
BC Use User HTab Curves=0
BC User HTab FreeFlow(D)= 0

Type RM Length L Ch R = 1 ,16725.7 ,12.99,14.15,15.54
XS GIS Cut Line= 3
-610357.07759999   -1045619.9076    -610392.5535   -1045545.0681
    -610471.4441   -1045388.2447
#Sta/Elev= 30
       0  358.73    8.25  357.95   13.74   358.1   21.33  357.43   25.38  355.29
   29.98  354.13   33.21  352.97   34.21  352.29   38.23  350.14   41.28  348.17
   43.17  347.33   43.48  346.77    43.9  346.24   52.08  346.36   53.19  346.68
   55.07  347.84   56.99  347.96   65.11  348.18   84.43  347.85   95.58  348.09
  108.04  347.88  116.51  348.04   141.6  348.08  150.14  347.93  185.69   348.8
  222.57  348.62  252.83     349  253.56  349.11  256.38     350  258.37  350.05
#Mann= 3 , 0 , 0
       0      .1       0   41.28     .05       0   56.99      .1       0
Levee=0,,,-1,64.95,348.17,,
#Block Obstruct= 1 ,-1
       0    8.03361.3521
Bank Sta=41.28,56.99
XS Rating Curve= 0 ,0
Exp/Cntr=0.5,0.3

Type RM Length L Ch R = 6 ,16715   ,,,
Lateral Weir Pos= 3
Lateral Weir End=                ,                ,        ,2 d
Lateral Weir Distance=0
Lateral Weir TW Multiple XS=0
Lateral Weir WD=1
Lateral Weir Coef=0.3
LW OverFlow Method 2D=True
Lateral Weir WSCriteria=-1
Lateral Weir Flap Gates= 0
Lateral Weir Hagers EQN= 0 ,,,,,
Lateral Weir SS=0.05,0.05,
Lateral Weir Type= 0
Lateral Weir Connection Pos and Dist= 3 ,
Lateral Weir SE= 30
       0 349.215    .474 349.023  18.891 348.578  78.748  348.43  136.85 347.752
 195.867 347.922 216.797 347.261 221.779 347.757 235.284 347.449 257.518 347.782
 272.199 348.258 284.653 348.115 322.214 346.991  328.31 346.141 354.429 346.124
 369.233 346.533 393.997 345.668 415.066 345.211 429.638 345.164 440.479 344.687
 447.487 345.302 474.598 344.849 541.309 344.664 546.453 344.826 547.738 345.632
 565.492 345.828 587.833 345.609 601.029 345.977 606.759 346.568 609.822 347.766
Lateral Weir Centerline= 6
       -610477.7     -1045392.73      -610401.53     -1045562.28
      -610469.36     -1045650.08       -610498.3     -1045665.85
      -610639.47     -1045650.25      -610697.93      -1045533.5
LW Div RC= 0 ,False,

Type RM Length L Ch R = 1 ,16711.55,25.25,25.95,28.78
XS GIS Cut Line= 6
-610364.63259999   -1045627.0364    -610377.2875   -1045602.5042
-610393.99859999   -1045577.0942    -610395.3159   -1045574.2261
    -610401.3596   -1045562.6079-610401.52658645 -1045562.282358
#Sta/Elev= 16
       0  358.55   11.42  357.93   16.23   357.9   24.38  356.88   26.34  356.18
   31.38  354.97   39.53  349.35   40.08  349.03   44.53  347.35   46.16  346.17
   53.25  345.98   54.11  345.99   55.32  347.27   55.84  347.68   61.13  347.85
   74.64  347.97
#Mann= 3 , 0 , 0
       0      .1       0   40.08     .05       0   55.84      .1       0
Bank Sta=40.08,55.84
XS Rating Curve= 0 ,0
Exp/Cntr=0.3,0.1

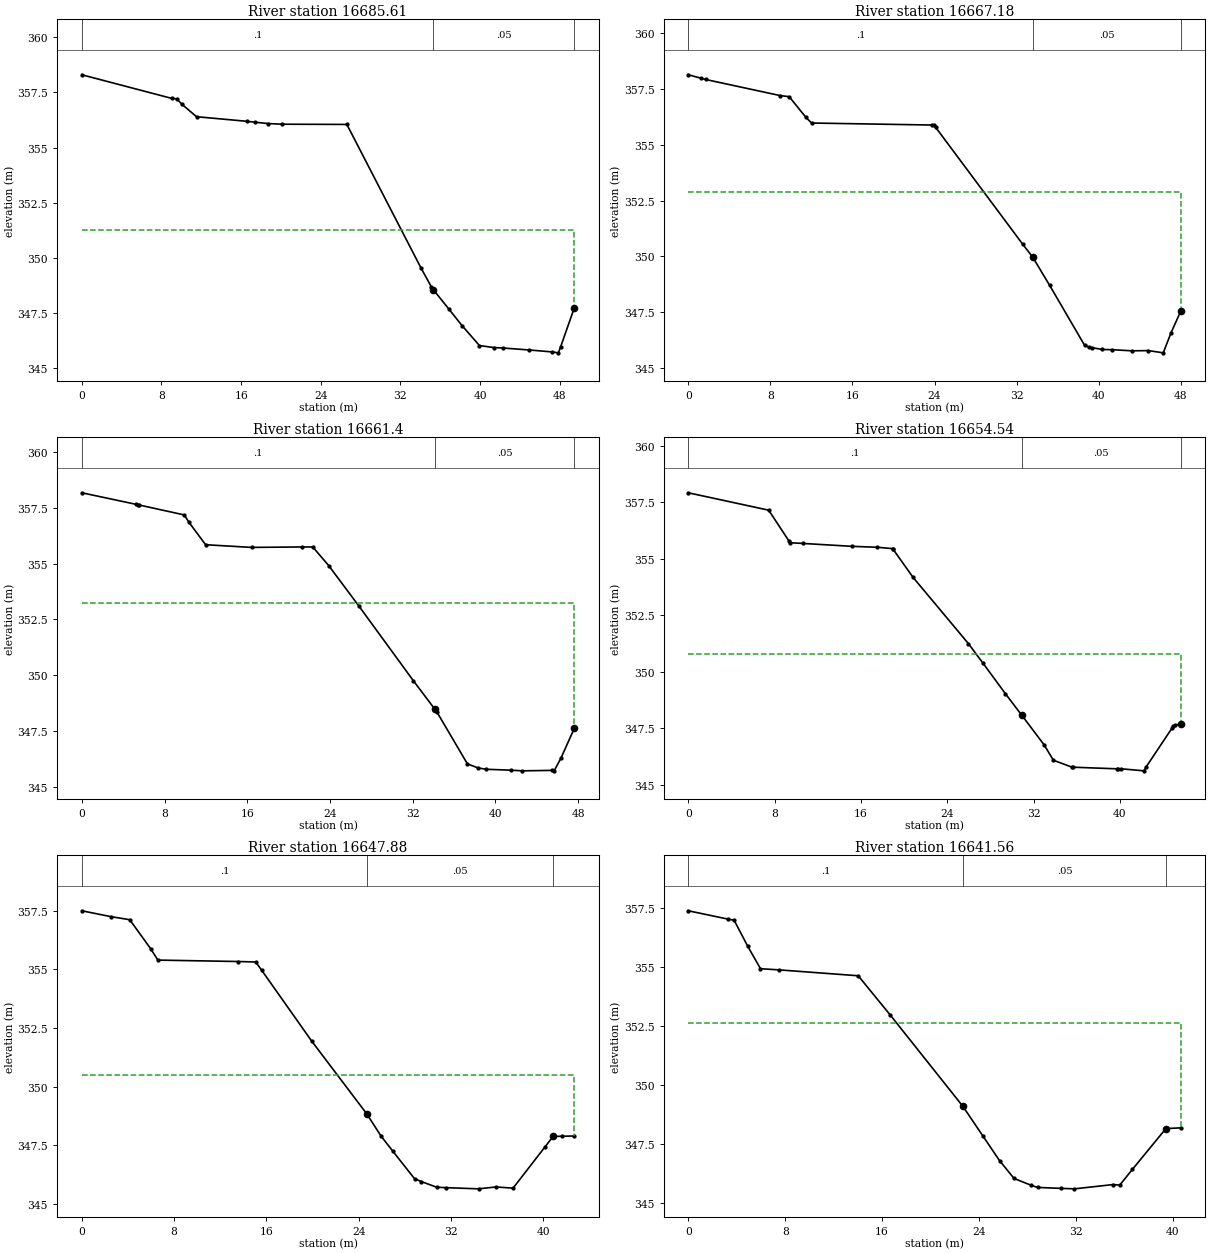
Type RM Length L Ch R = 1 ,16685.61,17.06,18.42,16.35
XS GIS Cut Line= 2
-610382.98559999   -1045633.4457-610413.84150779-1045594.7804906
#Sta/Elev= 23
       0   358.3    9.03  357.23    9.52  357.21   10.06  356.96   11.52   356.4
   16.62  356.19   17.43  356.15    18.7  356.09   20.13  356.06   26.62  356.05
   34.05  349.56   35.12  348.68   35.31  348.56   36.89  347.67    38.2  346.93
   39.94  346.03   41.38  345.94   42.27  345.92   44.93  345.83   47.27  345.74
   47.87   345.7    48.1  345.98   49.47  347.74
#Mann= 3 , 0 , 0
       0      .1       0   35.31     .05       0   49.47      .1       0
#XS Ineff= 2 , 0
                                          351.26
Permanent Ineff=
       F       F
Bank Sta=35.31,49.47
XS Rating Curve= 0 ,0
Exp/Cntr=0.3,0.1

Type RM Length L Ch R = 1 ,16667.18,6.2,5.78,6.81
XS GIS Cut Line= 3
    -610393.8158    -1045643.949-610416.82609999   -1045617.2862
-610426.76267826-1045609.2423331
#Sta/Elev= 23
       0  358.13    1.28  357.97    1.68  357.92    8.94   357.2    9.83  357.15
   11.45  356.23   12.01  355.97   23.73  355.88   23.98  355.89   24.12  355.77
   32.58  350.55   33.56  349.97   35.22   348.7   38.62  346.02   39.02  345.94
   39.38345.9102   40.35  345.83   41.33  345.82   43.26  345.77   44.85  345.78
   46.29  345.68   47.06  346.59      48  347.55
#Mann= 3 , 0 , 0
       0      .1       0   33.56     .05       0      48      .1       0
#XS Ineff= 2 , 0
                                          352.89
Permanent Ineff=
       F       F
Bank Sta=33.56,48
XS Rating Curve= 0 ,0
Exp/Cntr=0.3,0.1

Type RM Length L Ch R = 1 ,16661.4 ,5.64,6.86,5.9
XS GIS Cut Line= 3
    -610396.1494   -1045646.1225-610420.53339999   -1045622.2464
-610430.63452411-1045613.2908368
#Sta/Elev= 24
       0  358.16    5.28  357.64    5.39  357.63    5.48  357.62    9.91  357.17
   10.36  356.84   11.97  355.84   16.41  355.72   21.28  355.74   22.33  355.74
   23.87  354.91   26.78  353.11   32.07  349.76   34.13   348.5   34.35  348.36
   37.29  346.05   38.32  345.87   39.09  345.81   41.49  345.77   42.58  345.74
   45.45  345.76   45.69  345.75   46.33   346.3   47.63  347.64
#Mann= 3 , 0 , 0
       0      .1       0   34.13     .05       0   47.63      .1       0
#XS Ineff= 2 , 0
                                          353.25
Permanent Ineff=
       F       F
Bank Sta=34.13,47.63
XS Rating Curve= 0 ,0
Exp/Cntr=0.3,0.1

Type RM Length L Ch R = 1 ,16654.54,6.93,6.66,6.8
XS GIS Cut Line= 5
     -610399.919   -1045646.2163-610414.10069999   -1045633.6221
    -610423.8823   -1045626.7642    -610435.5652   -1045618.9463
-610435.89745156-1045618.3511481
#Sta/Elev= 27
       0  357.92    7.45  357.15    9.31   355.8    9.46  355.71   10.59  355.68
    15.2  355.55   17.51  355.51   18.93  355.45   18.97  355.43   20.83  354.18
   25.96  351.25   27.32  350.38   29.38  349.04   30.91  348.08   32.98  346.77
   33.84  346.09   35.52  345.79    35.7  345.78    39.7  345.71   39.83   345.7
   40.15  345.71   42.23  345.62   42.42  345.78   44.85  347.52   44.97  347.61
   45.13  347.63   45.65  347.71
#Mann= 3 , 0 , 0
       0      .1       0   30.91     .05       0   45.65      .1       0
#XS Ineff= 2 , 0
                                          350.79
Permanent Ineff=
       F       F
Bank Sta=30.91,45.65
XS Rating Curve= 0 ,0
Exp/Cntr=0.3,0.1

Type RM Length L Ch R = 1 ,16647.88,5.99,6.32,7.53
XS GIS Cut Line= 4
-610407.45239999   -1045648.6625    -610428.5344   -1045631.8985
-610441.36149999   -1045622.7545 -610441.3650268-1045622.7479753
#Sta/Elev= 23
       0  357.49    2.52  357.24    4.15  357.11    5.97  355.87    6.59  355.39
   13.51  355.33   15.07  355.31    15.6  354.95   19.91  351.95    24.7  348.84
   25.93   347.9   26.93  347.27   28.84  346.08   29.43  345.96   30.75  345.72
   31.58   345.7   34.39  345.65   35.89  345.73   37.38  345.68   40.17  347.45
   40.85  347.88    41.6  347.89   42.69   347.9
#Mann= 3 , 0 , 0
       0      .1       0    24.7     .05       0   40.85      .1       0
#XS Ineff= 2 , 0
                                          350.49
Permanent Ineff=
       F       F
Bank Sta=24.7,40.85
XS Rating Curve= 0 ,0
Exp/Cntr=0.3,0.1

Type RM Length L Ch R = 1 ,16641.56,17.07,15.6,12.26
XS GIS Cut Line= 3
-610413.30689999   -1045653.7066-610431.29479999   -1045637.3368
-610444.93612721 -1045628.331022
#Sta/Elev= 21
       0   357.4    3.24  357.05    3.78     357     4.9   355.9    5.96  354.94
    7.49  354.89   14.03  354.64   16.68  352.97   22.68  349.09   24.32  347.84
    25.7  346.79    26.9  346.03   28.32  345.74   28.84  345.65   30.77  345.61
   31.89  345.59   35.06  345.77   35.63  345.75   36.68  346.42   39.44  348.15
   40.67  348.18
#Mann= 3 , 0 , 0
       0      .1       0   22.68     .05       0   39.44      .1       0
#XS Ineff= 2 , 0
                                          352.63
Permanent Ineff=
       F       F
Bank Sta=22.68,39.44
XS Rating Curve= 0 ,0
Exp/Cntr=0.3,0.1

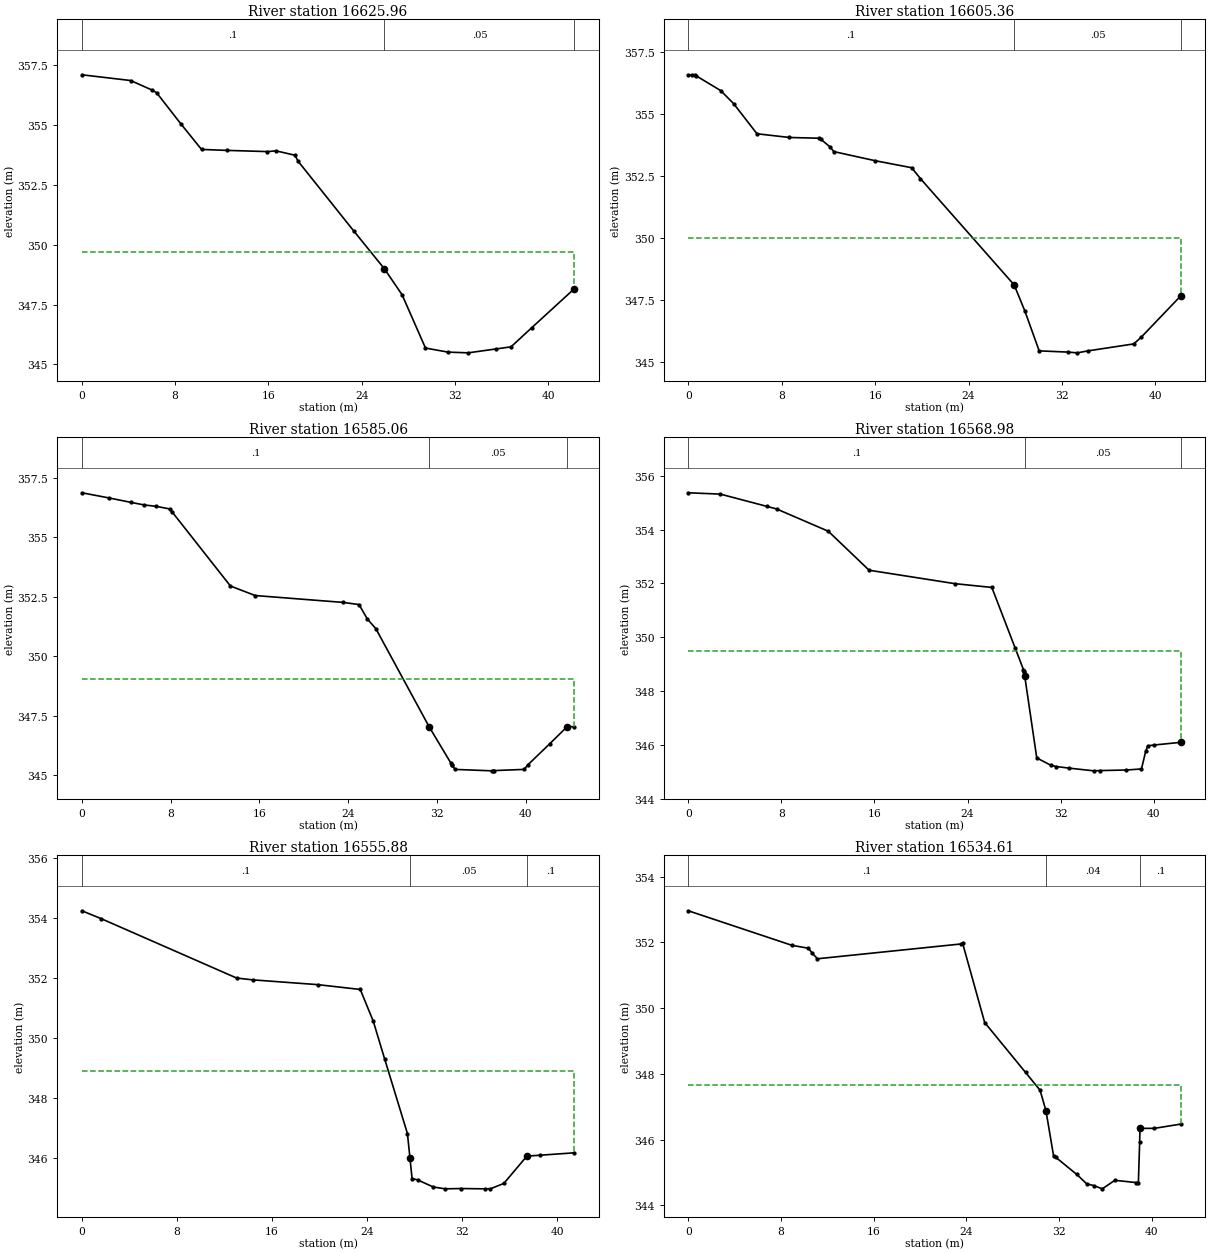
Type RM Length L Ch R = 1 ,16625.96,21.61,20.6,17.48
XS GIS Cut Line= 3
-610425.68789999   -1045669.8678     -610440.574   -1045651.9392
-610454.25009494-1045638.8687475
#Sta/Elev= 21
       0   357.1    4.18  356.86    5.98  356.47    6.41  356.35    8.47  355.06
   10.26  353.98   12.46  353.94   15.91  353.89   16.65  353.92   18.26  353.74
   18.55  353.48    23.3  350.58   25.94  348.99   27.45  347.91   29.46  345.68
   31.39  345.51   33.12  345.48   35.47  345.64   36.79  345.73   38.57  346.53
   42.22  348.16
#Mann= 3 , 0 , 0
       0      .1       0   25.94     .05       0   42.22      .1       0
#XS Ineff= 2 , 0
                                           349.7
Permanent Ineff=
       F       F
Bank Sta=25.94,42.22
XS Rating Curve= 0 ,0
Exp/Cntr=0.3,0.1

Type RM Length L Ch R = 1 ,16605.36,21.02,20.3,16.27
XS GIS Cut Line= 2
-610445.09629999   -1045684.5852-610469.36071481-1045650.0841442
#Sta/Elev= 24
       0  356.58     .29  356.59     .55  356.59     .63  356.56    2.78  355.95
    3.89  355.42    5.88  354.21    8.66  354.06   11.21  354.03   11.37  353.98
   12.16  353.67   12.46  353.49   16.03  353.12   19.13  352.84   19.88   352.4
   27.91  348.11   28.83  347.05   30.05  345.45   32.51   345.4   33.32  345.37
   34.24  345.45   38.15  345.73   38.79     346   42.18  347.67
#Mann= 3 , 0 , 0
       0      .1       0   27.91     .05       0   42.18      .1       0
#XS Ineff= 2 , 0
                                          349.99
Permanent Ineff=
       F       F
Bank Sta=27.91,42.18
XS Rating Curve= 0 ,0
Exp/Cntr=0.3,0.1

Type RM Length L Ch R = 1 ,16585.06,17.86,16.08,10.48
XS GIS Cut Line= 2
    -610464.0819   -1045699.0756-610485.82060305-1045660.3808059
#Sta/Elev= 26
       0  356.87    2.48  356.65    4.39  356.47     5.6  356.36     6.7   356.3
    7.92  356.19    8.11  356.08   13.39  352.95   15.62  352.55   23.57  352.26
   24.98  352.17   25.73  351.56   26.49  351.16    31.3  347.03   33.25  345.51
   33.37  345.41   33.38  345.41   33.63  345.24   36.97  345.18   37.02  345.18
   37.11  345.19   39.85  345.24   40.21  345.44   42.17  346.32   43.72  347.03
   44.38  347.04
#Mann= 3 , 0 , 0
       0      .1       0    31.3     .05       0   43.72      .1       0
#XS Ineff= 2 , 0
                                          349.04
Permanent Ineff=
       F       F
Bank Sta=31.3,43.72
XS Rating Curve= 0 ,0
Exp/Cntr=0.3,0.1

Type RM Length L Ch R = 1 ,16568.98,14.3,13.1,11.02
XS GIS Cut Line= 4
    -610486.8255   -1045706.5634-610495.14299999   -1045679.7281
    -610497.7888   -1045668.0863-610498.30436762-1045665.8467946
#Sta/Elev= 25
       0  355.37    2.76  355.32    6.79  354.86    7.58  354.77   12.03  353.94
   15.54  352.49   22.92  351.99   26.09  351.85   28.09   349.6   28.81  348.79
   28.84348.7563   28.89   348.7   28.92  348.54   29.95  345.51   31.19  345.23
   31.63  345.19   32.74  345.13   34.85  345.03   35.37  345.04   37.62  345.06
   38.95   345.1   39.31  345.75   39.49  345.96   40.03  345.99   42.33  346.09
#Mann= 3 , 0 , 0
       0      .1       0   28.92     .05       0   42.33      .1       0
#XS Ineff= 2 , 0
                                          349.48
Permanent Ineff=
       F       F
Bank Sta=28.92,42.33
XS Rating Curve= 0 ,0
Exp/Cntr=0.3,0.1

Type RM Length L Ch R = 1 ,16555.88,20.77,21.27,17.9
XS GIS Cut Line= 4
    -610504.2404   -1045706.1507    -610509.2146    -1045681.174
    -610509.4305   -1045668.0863-610510.03447263-1045665.2765263
#Sta/Elev= 21
       0  354.23    1.61  353.97   13.02  351.99   14.36  351.93   19.85  351.77
   23.42  351.61   24.51  350.56   25.47   349.3   27.39  346.81    27.6  346.01
   27.78  345.31   28.24  345.27   29.57  345.03   30.58  344.97   31.88  344.98
   33.95  344.97   34.36  344.97    35.5  345.15   37.44  346.06   38.56  346.09
   41.43  346.17
#Mann= 3 , 0 , 0
       0      .1       0    27.6     .05       0   37.44      .1       0
#XS Ineff= 2 , 0
                                          348.89
Permanent Ineff=
       F       F
Bank Sta=27.6,37.44
XS Rating Curve= 0 ,0
Exp/Cntr=0.3,0.1

Type RM Length L Ch R = 1 ,16534.61,4.61,4.56,4.51
XS GIS Cut Line= 4
-610529.54529999   -1045705.4184    -610529.8783    -1045676.323
-610530.17399999   -1045665.9981-610530.52020198-1045662.9564269
#Sta/Elev= 25
       0  352.96    8.93  351.91   10.36  351.82   10.67  351.68   11.14   351.5
   23.52  351.95   23.66  351.98   25.57  349.56    29.1  348.04   30.35   347.5
   30.86  346.87   31.52  345.49    31.7  345.46   33.51  344.94   34.38  344.65
   34.97   344.6   35.72   344.5    36.8  344.76   38.65  344.69   38.83  344.68
   38.94  345.92   38.97  346.35   39.06  346.34    40.2  346.34   42.49  346.47
#Mann= 3 , 0 , 0
       0      .1       0   30.86     .04       0   38.97      .1       0
#XS Ineff= 2 , 0
                                          347.66
Permanent Ineff=
       F       F
Bank Sta=30.86,38.97
XS Rating Curve= 0 ,0
Exp/Cntr=0.5,0.3

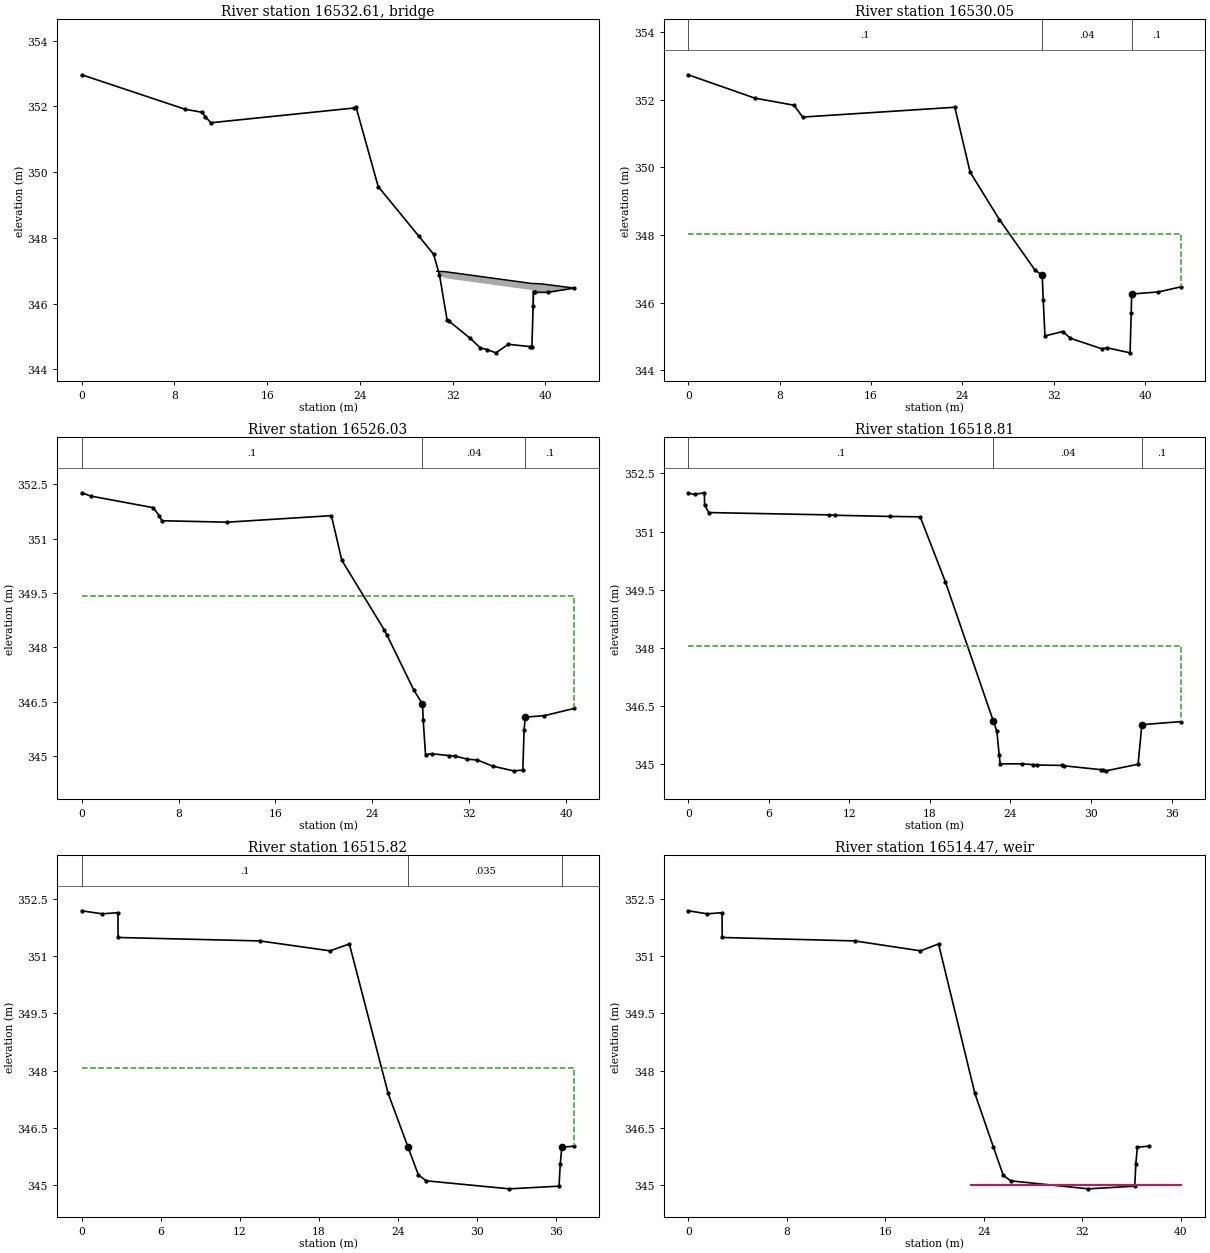
Type RM Length L Ch R = 3 ,16532.61,,,
Bridge Culvert--1,0,-1,-1, 0
Deck Dist Width WeirC Skew NumUp NumDn MinLoCord MaxHiCord MaxSubmerge Is_Ogee
1,1.6,1.4,0, 7, 7, , , 0.98, 0, 0,0,,
   30.63   31.33   31.33   38.83   38.83   39.63   42.49
  346.98  346.97  346.97  346.61  346.61   346.6  346.47
  346.78          346.77  346.41
   30.48   31.18   31.18   38.68   38.68   39.48   43.12
  346.98  346.97  346.97  346.61  346.61   346.6  346.47
  346.78          346.77  346.41
BR Coef=-1 , 0 , 0 ,, 0 ,,,0.8,-1,,0,
WSPro=,,,, 1 ,,,, 0 ,,,, 0 ,,,,-1 ,-1 ,-1 , 0 , 0 , 0 , 0 , 0
BC Design=,, 0 ,, 0 ,,,,,,
BC HTab HWMax=347.5
BC HTab TWMax=347.5
BC HTab MaxFlow=80
BC Use User HTab Curves=0
BC User HTab FreeFlow(D)= 0

Type RM Length L Ch R = 1 ,16530.05,3.73,4.02,4.32
XS GIS Cut Line= 4
    -610534.1055   -1045705.0639-610534.43849999   -1045675.9685
    -610534.7342   -1045665.6436-610535.15137876-1045661.9783369
#Sta/Elev= 21
       0  352.74    5.83  352.05    9.26  351.84   10.02  351.49   23.34  351.78
   24.68  349.86   27.24  348.46   30.35  346.97   30.99  346.81   31.08  346.08
   31.23  345.02   32.79  345.15   33.46  344.95    36.2  344.64   36.66  344.67
   38.68  344.52   38.78   345.7   38.82  346.25   38.85  346.26   41.16  346.32
   43.12  346.47
#Mann= 3 , 0 , 0
       0      .1       0   30.99     .04       0   38.85      .1       0
#XS Ineff= 2 , 0
                                          348.04
Permanent Ineff=
       F       F
Bank Sta=30.99,38.85
XS Rating Curve= 0 ,0
Exp/Cntr=0.5,0.3

Type RM Length L Ch R = 1 ,16526.03,7.85,7.22,5.99
XS GIS Cut Line= 3
    -610538.0693   -1045702.3362-610538.07229999    -1045677.112
-610539.30777144-1045661.7084898
#Sta/Elev= 26
       0  352.26     .74  352.17     5.9  351.85     6.4  351.63    6.62  351.49
   12.02  351.45   20.62  351.63   21.48   350.4   24.99  348.48   25.22  348.33
   27.42  346.83   28.14  346.44    28.2     346   28.39  345.05   28.96  345.07
   30.31  345.02   30.82  345.01   31.85  344.92   32.67   344.9   33.93  344.73
   35.66   344.6   36.43  344.62   36.53  345.72   36.63  346.08    38.2  346.12
   40.68  346.32
#Mann= 3 , 0 , 0
       0      .1       0   28.14     .04       0   36.63      .1       0
#XS Ineff= 2 , 0
                                          349.41
Permanent Ineff=
       F       F
Bank Sta=28.14,36.63
XS Rating Curve= 0 ,0
Exp/Cntr=0.3,0.1

Type RM Length L Ch R = 1 ,16518.81,3.46,2.99,2.85
XS GIS Cut Line= 2
    -610546.3568   -1045698.7429 -610545.6112536-1045662.0634616
#Sta/Elev= 25
       0  351.99     .48  351.96    1.21     352    1.22  351.69    1.53  351.49
   10.47  351.43   10.93  351.42   15.01  351.39   17.28  351.38   19.15  349.71
   22.73346.1114   22.99  345.85   23.16  345.25   23.24  345.01    24.9  345.01
   25.71  344.99   25.95  344.98   27.84  344.97   27.98  344.96   30.75  344.86
    30.9  344.84   31.12  344.83   33.51     345   33.79  346.02   36.69   346.1
#Mann= 3 , 0 , 0
       0      .1       0   22.73     .04       0   33.79      .1       0
#XS Ineff= 2 , 0
                                          348.06
Permanent Ineff=
       F       F
Bank Sta=22.73,33.79
XS Rating Curve= 0 ,0
Exp/Cntr=0.3,0.1

Type RM Length L Ch R = 1 ,16515.82,2.86,2.86,2.83
XS GIS Cut Line= 4
    -610549.2021   -1045701.0436    -610549.7798   -1045679.3474
    -610548.1328   -1045663.7179-610548.13310631-1045663.7151877
#Sta/Elev= 16
       0  352.19    1.55  352.11    2.75  352.14    2.76  351.49   13.52   351.4
   18.86  351.14   20.33  351.32   23.28   347.4   24.79  345.99   25.58  345.26
   26.18  345.11   32.48   344.9   36.26  344.97   36.35  345.55   36.47  345.99
   37.42  346.02
#Mann= 3 , 0 , 0
       0      .1       0   24.79    .035       0   36.47      .1       0
#XS Ineff= 2 , 0
                                          348.06
Permanent Ineff=
       F       F
Bank Sta=24.79,36.47
XS Rating Curve= 0 ,0
Exp/Cntr=0.3,0.1

Type RM Length L Ch R = 5 ,16514.47,,,
IW Pilot Flow=0
#Inline Weir SE= 2
      23     345      40     345
IW Dist,WD,Coef,Skew,MaxSub,Min_El,Is_Ogee,SpillHt,DesHd
0.5,0.5,1.4,0,0.98,, 0 ,,,0,0,
Inline Weir Flap Gates= 0

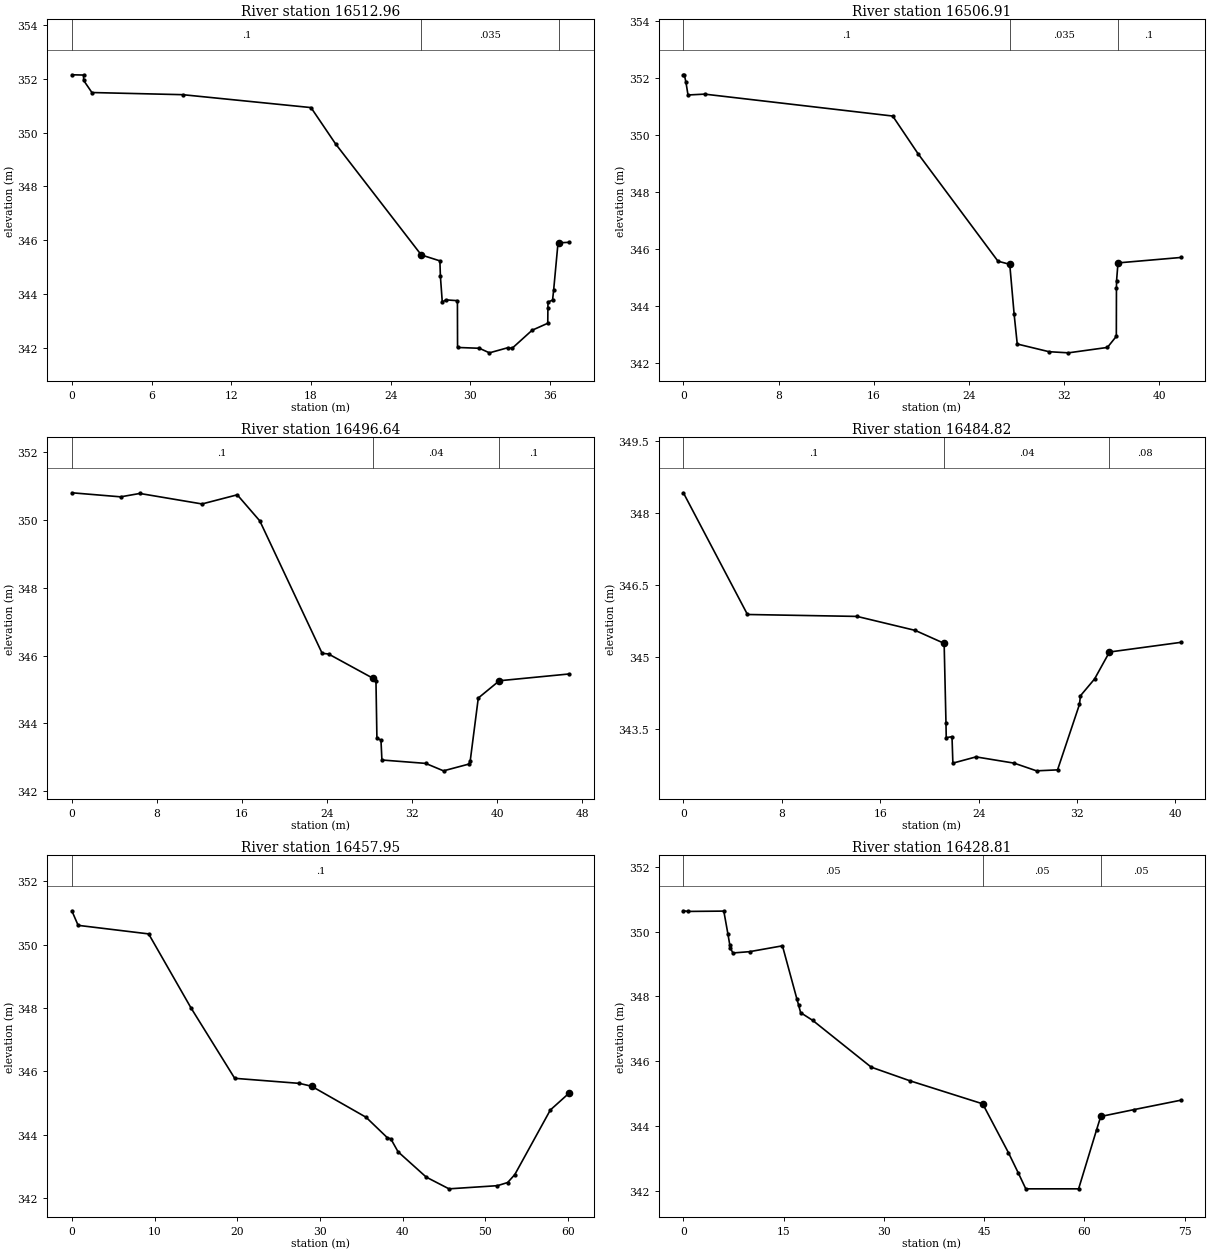
Type RM Length L Ch R = 1 ,16512.96,6.06,6.05,5.92
XS GIS Cut Line= 4
    -610552.0539   -1045700.8215    -610552.6316   -1045679.1253
    -610550.9846   -1045663.4958-610550.98469973-1045663.4949169
#Sta/Elev= 27
       0  352.15     .88  352.14     .89  351.94    1.51  351.49    8.34  351.41
      18  350.93   19.85  349.58    26.3  345.45    27.7  345.23   27.74  344.65
   27.88   343.7   28.15  343.78   29.02  343.75   29.03  342.01   30.67  341.98
   31.43  341.81   32.81     342   33.14  341.98   34.64  342.65   35.82  342.91
   35.83  343.49   35.84   343.7   36.18  343.77   36.26  344.13   36.59  345.89
   36.64   345.9   37.42  345.92
#Mann= 3 , 0 , 0
       0      .1       0    26.3    .035       0   36.64      .1       0
Bank Sta=26.3,36.64
XS Rating Curve= 0 ,0
Exp/Cntr=0.3,0.1

Type RM Length L Ch R = 1 ,16506.91,10.74,10.26,7.39
XS GIS Cut Line= 4
    -610558.0583   -1045700.0491     -610558.636   -1045678.3529
     -610556.989   -1045662.7234-610557.48063718-1045658.3701842
#Sta/Elev= 19
       0  352.11     .08  352.11     .22  351.84     .39   351.4    1.79  351.43
    17.6  350.66   19.74  349.33   26.45  345.56   27.44  345.45   27.81  343.69
   28.07  342.65   30.74  342.38   32.37  342.34   35.65  342.53    36.4  342.92
   36.41  344.61   36.42  344.87   36.54   345.5    41.8  345.69
#Mann= 3 , 0 , 0
       0      .1       0   27.44    .035       0   36.54      .1       0
Bank Sta=27.44,36.54
XS Rating Curve= 0 ,0
Exp/Cntr=0.3,0.1

Type RM Length L Ch R = 1 ,16496.64,11.84,11.82,12.2
XS GIS Cut Line= 4
-610568.93389999   -1045699.5274-610569.01029999   -1045673.3139
    -610566.1424   -1045658.7355-610566.08942479-1045653.0649175
#Sta/Elev= 20
       0  350.81    4.59  350.69    6.39  350.79   12.24  350.48   15.55  350.75
   17.67  349.98   23.53  346.07   24.13  346.05   28.27  345.34   28.59  345.26
   28.68  343.56   29.06  343.51   29.15  342.92   33.26  342.82   34.94   342.6
   37.33   342.8   37.45  342.89   38.21  344.75   40.19  345.26   46.74  345.46
#Mann= 3 , 0 , 0
       0      .1       0   28.27     .04       0   40.19      .1       0
Bank Sta=28.27,40.19
XS Rating Curve= 0 ,0
Exp/Cntr=0.3,0.1

Type RM Length L Ch R = 1 ,16484.82,24.61,26.87,29.73
XS GIS Cut Line= 4
    -610578.8018   -1045690.2112    -610580.5927   -1045670.9478
    -610577.7248   -1045656.3694-610578.09960674-1045650.1623162
#Sta/Elev= 18
       0  348.42    5.21  345.89   14.12  345.85   18.84  345.56    21.2  345.29
   21.35  343.63   21.37  343.33   21.84  343.35   21.91   342.8   23.79  342.93
   26.89   342.8   28.71  342.64   30.42  342.66    32.2  344.02   32.28   344.2
   33.43  344.55   34.64  345.11   40.42  345.31
#Mann= 3 , 0 , 0
       0      .1       0    21.2     .04       0   34.64     .08       0
Bank Sta=21.2,34.64
XS Rating Curve= 0 ,0
Exp/Cntr=0.3,0.1

Type RM Length L Ch R = 1 ,16457.95,27.86,29.15,31.23
XS GIS Cut Line= 4
    -610600.4112   -1045709.3366    -610604.6319   -1045671.6896
    -610607.2707   -1045651.8644-610607.72091472-1045649.6558399
#Sta/Elev= 18
       0  351.07     .76  350.61    9.29  350.34   14.42     348    19.7  345.78
   27.53  345.62      29  345.53   35.59  344.55   38.18   343.9   38.58  343.87
   39.46  343.46   42.87  342.66   45.62  342.29   51.48  342.39   52.72  342.49
   53.58  342.74   57.88  344.78   60.14  345.31
#Mann= 1 ,-1 , 0
       0      .1       0
Bank Sta=29,60.14
XS Rating Curve= 0 ,0
Exp/Cntr=0.3,0.1

Type RM Length L Ch R = 1 ,16428.81,27.35,26.86,24.82
XS GIS Cut Line= 2
    -610619.1772   -1045721.7966-610639.46888057-1045650.2483352
#Sta/Elev= 24
       0  350.64     .71  350.62    6.05  350.63    6.66  349.93    6.95  349.58
    7.04  349.48    7.42  349.34    9.91  349.38   14.82  349.56   16.97  347.93
   17.23  347.74   17.54   347.5   19.36  347.26    28.1  345.82   33.89   345.4
   44.77  344.69   48.61  343.19   50.12  342.55   51.22  342.07   59.12  342.07
   61.81  343.89   62.43   344.3   67.36  344.51   74.37   344.8
#Mann= 3 , 0 , 0
       0     .05       0   44.77     .05       0   62.43     .05       0
Bank Sta=44.77,62.43
XS Rating Curve= 0 ,0
Exp/Cntr=0.3,0.1

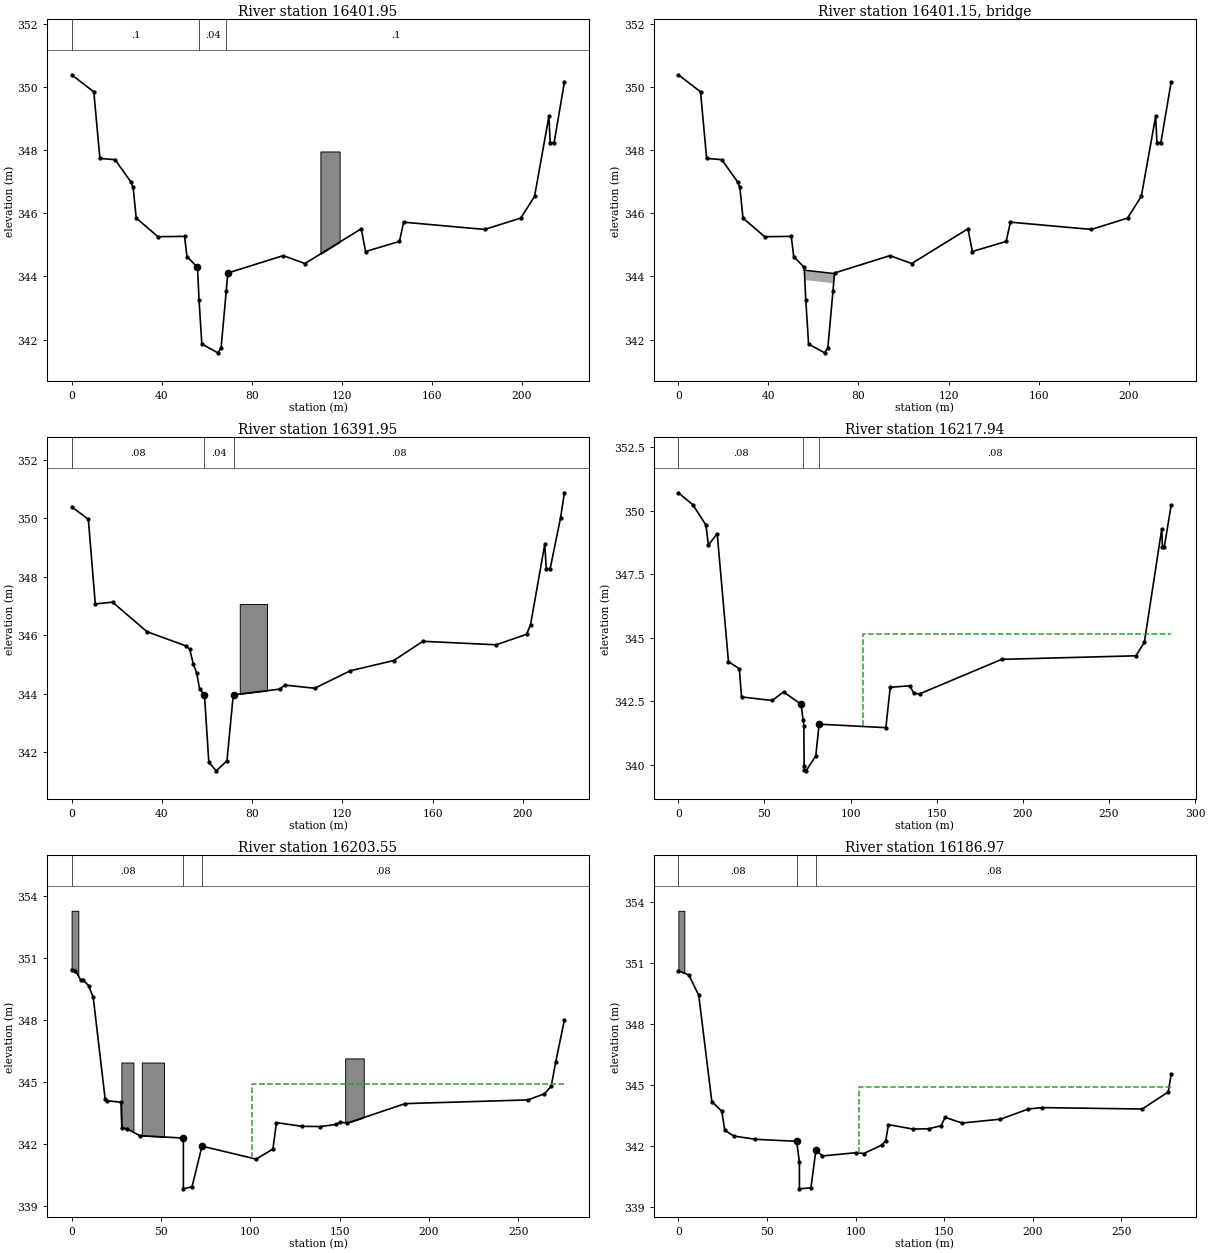
Type RM Length L Ch R = 1 ,16401.95,1.88,1.88,1.88
XS GIS Cut Line= 6
    -610643.0462   -1045735.4757    -610657.9483   -1045686.2902
-610661.88529999   -1045666.6815-610664.87119999    -1045645.638
-610675.02239999   -1045602.4955-610708.26749999   -1045527.6306
#Sta/Elev= 30
       0  350.39    9.85  349.85   12.56  347.74   19.29   347.7   26.28     347
   27.32  346.82    28.7  345.85   38.33  345.26   50.16  345.27   51.22  344.63
    55.9  344.29   56.59343.2583   57.83  341.86   64.94  341.58   66.39  341.74
   68.65343.5249   69.38  344.11   93.96  344.66  103.63  344.41  128.62  345.51
  130.57  344.79  145.58  345.11  147.47  345.72  183.43  345.49  199.49  345.85
  205.61  346.54  211.97  349.07  212.55  348.24   214.3  348.24  218.88  350.17
#Mann= 3 ,-1 , 0
       0      .1       0   56.59     .04       0   68.65      .1       0
#Block Obstruct= 1 ,-1
  110.49  119.04347.9603
Bank Sta=55.9,69.38
XS Rating Curve= 0 ,0
Exp/Cntr=0.5,0.3

Type RM Length L Ch R = 3 ,16401.15,,,
BEGIN DESCRIPTION:
16595.9  PF 211 ŽELEZNÁ LÁVKA PRO PÌŠÍ V
END DESCRIPTION:
Bridge Culvert--1,0,-1,-1, 0
Deck Dist Width WeirC Skew NumUp NumDn MinLoCord MaxHiCord MaxSubmerge Is_Ogee
0.5,1.3,1.4,0, 2, 2, , , 0.98, 0, 0,0,,
    55.8   69.52
   344.2  344.09
  343.89  343.78
    55.8   69.52
   344.2  344.09
  343.89  343.78
BR Coef=-1 , 0 , 0 ,, 0 ,,,0.8,-1,,0,
WSPro=,,,, 1 ,,,, 0 ,,,, 0 ,,,,-1 ,-1 ,-1 , 0 , 0 , 0 , 0 , 0
BC Design=,, 0 ,, 0 ,,,,,,
BC HTab HWMax=345.1
BC HTab TWMax=345
BC HTab MaxFlow=80
BC Use User HTab Curves=0
BC User HTab FreeFlow(D)= 0

Type RM Length L Ch R = 1 ,16391.95,18.23,18.4,18.11
XS GIS Cut Line= 6
    -610650.4058   -1045738.2674    -610658.0192   -1045723.5482
     -610669.287   -1045687.5937     -610674.261   -1045646.3993
    -610688.4727    -1045603.003-610717.91099999   -1045531.9448
#Sta/Elev= 30
       0   350.4    7.41  349.97   10.49  347.07   18.16  347.13   33.37  346.12
   50.73  345.63   52.36  345.51   53.89  345.02   55.45   344.7   56.67  344.17
   58.88343.9468   60.79  341.65   64.07  341.35   68.83  341.69   71.64  343.96
   71.91  343.96   92.16  344.15   94.48  344.29  107.73  344.18  123.49  344.78
  142.72  345.13  155.66  345.79  188.15  345.67  201.62  346.03  203.37  346.36
  209.67  349.11  210.34  348.28  212.07  348.28  216.69  350.03   218.4  350.88
#Mann= 3 ,-1 , 0
       0     .08       0   58.88     .04       0   71.91     .08       0
#Block Obstruct= 1 ,-1
   74.51    86.6347.0706
Bank Sta=58.88,71.91
XS Rating Curve= 0 ,0
Exp/Cntr=0.3,0.1

Type RM Length L Ch R = 1 ,16217.94,17.82,14.38,10.85
XS GIS Cut Line= 6
    -610749.3409   -1045804.8633    -610792.0326   -1045754.9198
    -610808.2784   -1045743.2547    -610827.6222   -1045711.1307
    -610872.3427   -1045570.3783    -610872.3427   -1045555.1515
#Sta/Elev= 30
       0  350.71    8.39  350.24   16.02  349.44   17.41  348.65   22.55   349.1
   29.09  344.06   35.38  343.78   36.67  342.67   54.49  342.53   61.05  342.87
   71.24  342.38   72.44341.7539   72.85  341.54   73.02  339.95    73.1  339.81
   74.14  339.76   79.78  340.35   81.72341.5977  120.46  341.46     123  343.05
  134.37  343.11  136.79  342.81  140.02  342.79  187.68  344.15  265.62  344.29
  270.54  344.82  280.67   349.3  281.02  348.59  282.12  348.58  286.12  350.23
#Mann= 3 ,-1 , 0
       0     .08       0   72.44     .04       0   81.72     .08       0
#XS Ineff= 2 , 0
                          107.39          345.13
Permanent Ineff=
       F       F
Bank Sta=71.24,81.72
XS Rating Curve= 0 ,0
Exp/Cntr=0.3,0.1

Type RM Length L Ch R = 1 ,16203.55,16.98,16.59,13.12
XS GIS Cut Line= 5
    -610769.6559   -1045808.4823    -610808.1264   -1045763.0171
    -610815.1211   -1045751.5259    -610847.5962   -1045700.0653
    -610890.0638   -1045564.6689
#Sta/Elev= 30
       0  350.46    2.07   350.4    4.97  349.97    6.36  349.96    9.56  349.67
   12.09  349.11   18.75  344.19   19.58   344.1   27.59  344.03    28.1  342.77
   30.81  342.75   38.12  342.41   62.52  342.29   62.53  339.83   67.37  339.93
   72.94   341.9  103.27  341.27  112.63  341.76  114.61  343.04  128.88  342.86
  139.06  342.85  148.15  342.95  150.27  343.06  154.36  343.02  186.61  343.96
  255.33  344.14  264.57  344.44  268.36   344.8  270.82  345.96  275.76  348.03
#Mann= 3 , 0 , 0
       0     .08       0   62.52     .04       0   72.94     .08       0
#XS Ineff= 2 , 0
                          101.15          344.89
Permanent Ineff=
       F       F
#Block Obstruct= 4 ,-1
  153.07  163.46346.1526       0    3.74353.3066   27.86   34.56 345.952
   39.28   51.69 345.952
Bank Sta=62.52,72.94
XS Rating Curve= 0 ,0
Exp/Cntr=0.3,0.1

Type RM Length L Ch R = 1 ,16186.97,23.06,21.77,16.29
XS GIS Cut Line= 5
    -610779.6482   -1045816.9759    -610825.1134   -1045768.5129
    -610828.6108   -1045757.0217-610860.08659999   -1045702.5634
    -610908.5496   -1045574.6612
#Sta/Elev= 30
       0  350.62    5.89  350.41   11.51  349.41    18.9  344.17   24.48  343.71
   26.19  342.77   31.27  342.48   43.49  342.32   66.78  342.22   68.32  341.18
   68.33  339.88   74.81  339.93   77.62  341.78   81.26   341.5  100.37  341.66
  104.66  341.62   114.7  342.03     117  342.24  118.59  343.04   132.6  342.82
  141.36  342.84  148.28  342.99  150.56   343.4  160.08  343.12  181.77  343.31
  197.52  343.81  205.12  343.88  261.78  343.81  276.45  344.65  278.14  345.52
#Mann= 3 , 0 , 0
       0     .08       0   66.78     .04       0   77.62     .08       0
#XS Ineff= 2 , 0
                          102.02          344.89
Permanent Ineff=
       F       F
#Block Obstruct= 1 ,-1
       0    3.38 353.571
Bank Sta=66.78,77.62
XS Rating Curve= 0 ,0
Exp/Cntr=0.3,0.1