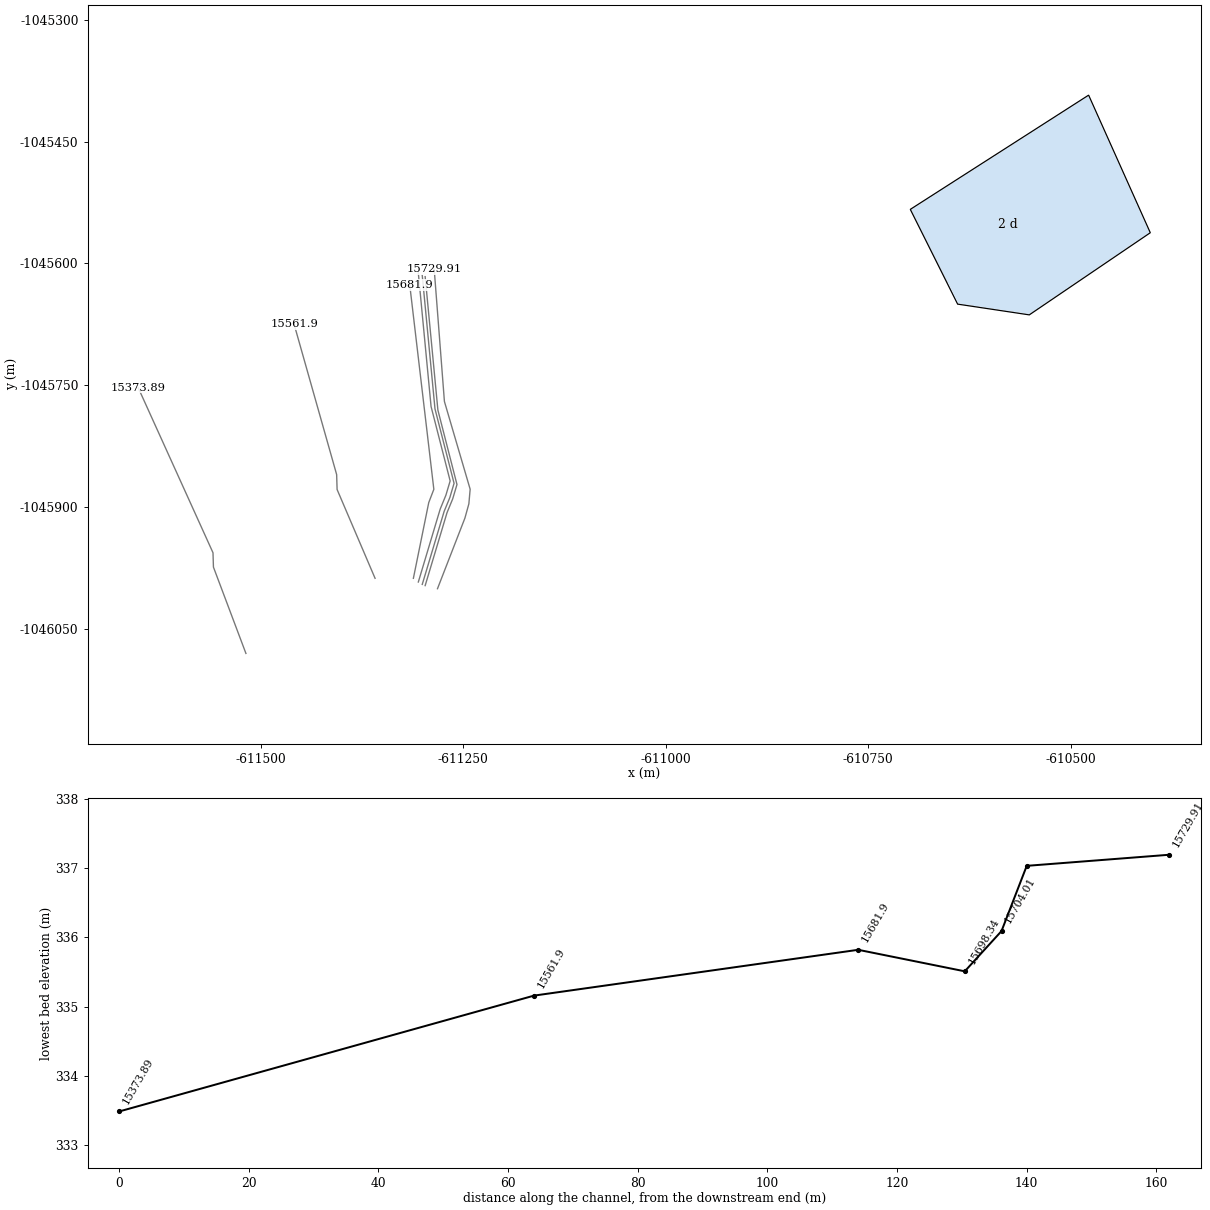
HEC-RAS study PPO_Kvasiny_efektiv.prj: PPO_Kvasiny_efektivita

--- PPO_Kvasiny_efektiv.g05 (geometry) --- (continued)

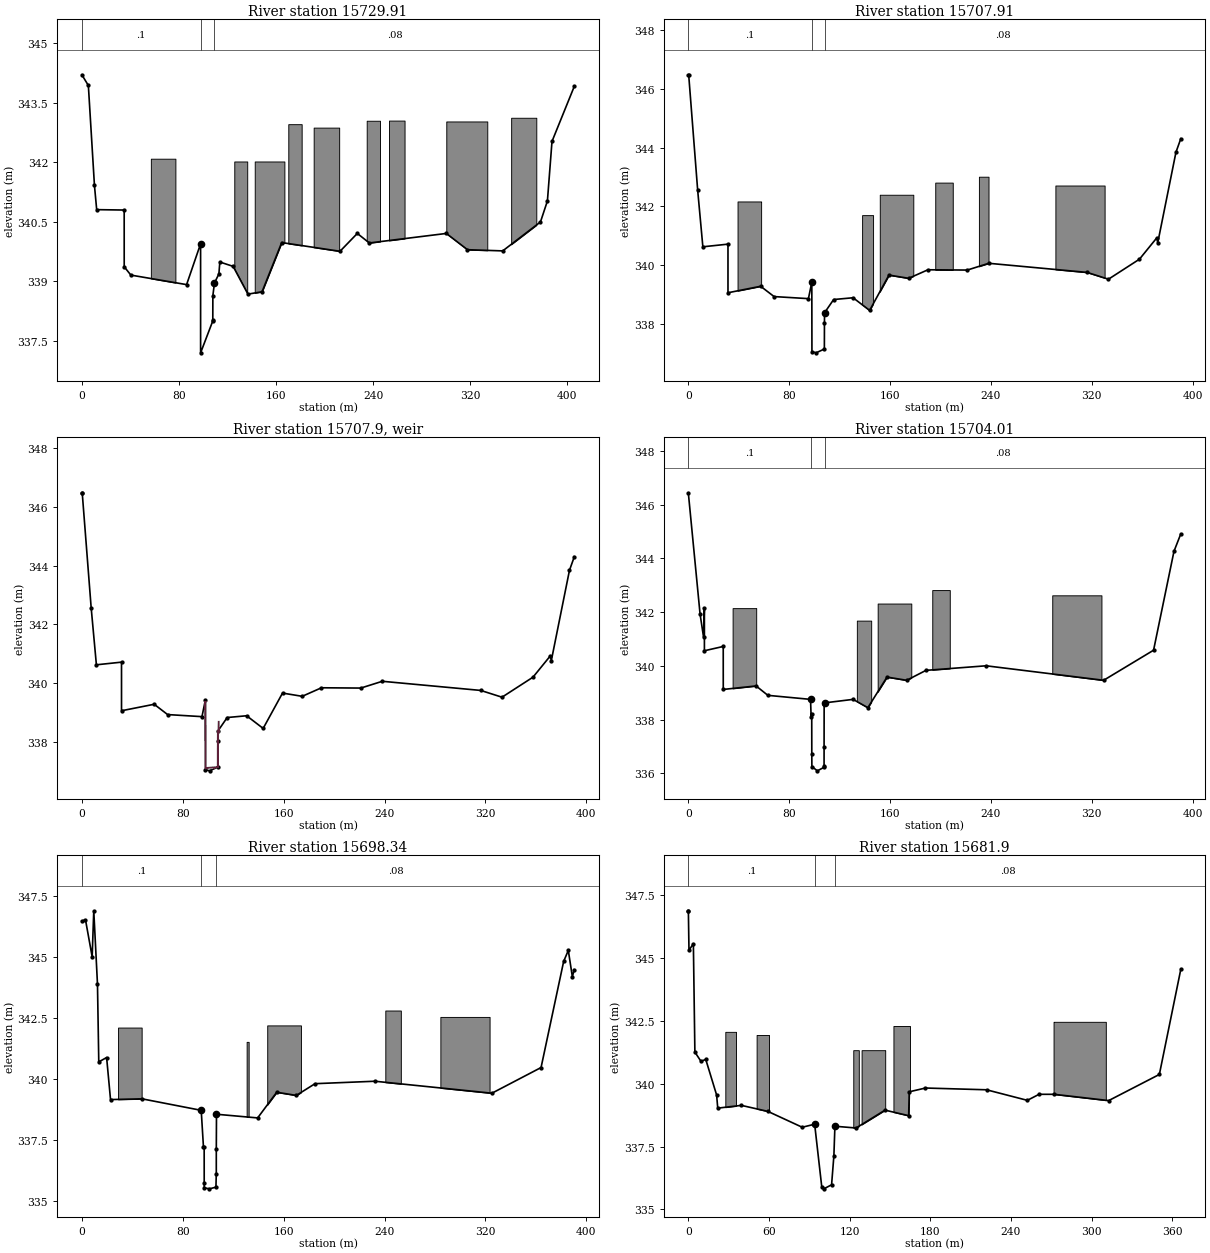
Type RM Length L Ch R = 1 ,15729.91,23.06,22.01,19.38
XS GIS Cut Line= 6
    -611281.7885   -1046000.8759-611247.89779999   -1045913.8258
    -611243.0385   -1045896.2879    -611241.4543   -1045878.3214
    -611273.2296   -1045770.2109    -611285.8491   -1045607.2642
#Sta/Elev= 30
       0   344.2    5.36  343.93   10.38  341.41   12.22   340.8   34.88  340.79
    34.9  339.36   40.38  339.15    86.3  338.91   97.84  339.94   97.85  337.19
  107.83  337.99  107.89  338.03  107.94  338.63  109.25  338.95  112.92  339.18
  113.68  339.48  124.63  339.37  136.84  338.67  148.48  338.73  164.67  339.97
  212.71  339.75  226.96   340.2  236.88  339.96   300.3   340.2  317.72  339.79
  346.77  339.76  377.88  340.49   383.6  341.02  387.37  342.52  405.77  343.91
#Mann= 3 , 0 , 0
       0      .1       0   97.84    .035       0  109.25     .08       0
#Block Obstruct= 9 ,-1
  125.59  136.26342.0143  142.44  166.88342.0143     191  212.02 342.868
   56.85   77.08342.0844  300.27  334.05343.0232  253.06  265.89343.0455
  353.72  374.44343.1166  170.09  181.11342.9549   234.7  245.66343.0414
Bank Sta=97.84,109.25
XS Rating Curve= 0 ,0
Exp/Cntr=0.3,0.1

Type RM Length L Ch R = 1 ,15707.91,3.89,3.89,3.9
XS GIS Cut Line= 6
    -611297.0154   -1045997.0692-611269.98739999   -1045907.1252
    -611262.9829    -1045890.143    -611257.7215   -1045872.5269
    -611281.2811   -1045780.8493    -611297.0154   -1045616.4002
#Sta/Elev= 30
       0  346.46     .29  346.47     7.4  342.56   11.53  340.63   31.45  340.72
   31.46  339.07   57.35  339.29   68.02  338.94   95.25  338.87   97.93  339.43
   98.03  337.07   101.3  337.03  107.88  337.16  107.95  338.03  108.02  338.39
  115.25  338.84  130.67   338.9  143.77  338.47  159.13  339.67  174.73  339.56
  190.03  339.85  221.21  339.84  238.26  340.07  316.29  339.76  333.17  339.53
  357.76  340.21  371.62  340.94  372.23  340.76  386.69  343.84  390.53   344.3
#Mann= 3 , 0 , 0
       0      .1       0   97.93    .035       0  108.02     .08       0
#Block Obstruct= 6 ,-1
   39.03   57.74342.1694  291.09  330.12342.7108  195.81   209.7342.8094
  151.82  178.41342.3976  137.81  146.51341.7051  230.44  238.06343.0097
Bank Sta=97.93,108.02
XS Rating Curve= 0 ,0
Exp/Cntr=0.3,0.1

Type RM Length L Ch R = 5 ,15707.9 ,,,
IW Pilot Flow=0
#Inline Weir SE= 8
   97.93  339.36      98  337.62   98.07  337.12  107.87  337.16  107.88  337.57
  107.97  338.38  108.33  338.34   108.6  338.69
IW Dist,WD,Coef,Skew,MaxSub,Min_El,Is_Ogee,SpillHt,DesHd
0.1,1,1.4,0,0.98,, 0 ,,,0,0,
Inline Weir Flap Gates= 0

Type RM Length L Ch R = 1 ,15704.01,5.49,5.67,5.52
XS GIS Cut Line= 6
    -611300.6086    -1045995.581    -611273.5806   -1045905.6369
-611266.57609999   -1045888.6548    -611261.3147   -1045871.0387
    -611284.8744   -1045779.3611    -611300.6086    -1045614.912
#Sta/Elev= 30
       0  346.44    9.31  341.93   12.04  341.08   12.75  342.14   12.76  340.56
   27.69  340.72   27.71  339.12   53.73  339.25   63.09   338.9   96.92  338.75
   97.39  338.08   97.86  338.22   97.92   336.7   97.99  336.25  102.33  336.09
  107.55  336.22  107.65  336.28  107.66  336.99  107.71  338.56   108.6338.6232
  130.67  338.75  142.36  338.44  157.56  339.58  173.15  339.46  188.47  339.83
  236.17     340  329.33  339.46  368.94  340.58  385.12  344.26  390.53  344.91
#Mann= 3 , 0 , 0
       0      .1       0   96.92    .035       0   108.6     .08       0
#Block Obstruct= 5 ,-1
   35.12   53.83342.1467  288.59  327.61342.6234  193.44  207.33342.8185
  150.16  176.82342.3174  133.64  145.02341.6818
Bank Sta=96.92,108.6
XS Rating Curve= 0 ,0
Exp/Cntr=0.3,0.1

Type RM Length L Ch R = 1 ,15698.34,15.5,16.44,16.98
XS GIS Cut Line= 6
-611305.45039999   -1045992.6441-611278.42249999      -1045902.7
    -611271.4179   -1045885.7179    -611266.1565   -1045868.1018
    -611289.7162   -1045776.4242-611305.45039999   -1045611.9751
#Sta/Elev= 30
       0  346.46    2.89  346.51    8.18     345    9.45  346.88   12.39  343.88
   13.42   340.7   19.64  340.88   22.74  339.16   47.73  339.19   94.65  338.72
   96.42  337.23      97  337.23   97.03  335.75   97.05  335.55  101.17  335.51
  106.33  335.58  106.61  336.13  106.62  337.12  106.77  338.56   139.4  338.41
  154.52  339.46  170.07  339.33  184.92  339.81  232.43  339.91  325.16  339.42
  364.15  340.47  382.07  344.81  385.76  345.26  388.95  344.19  390.53  344.47
#Mann= 3 , 0 , 0
       0      .1       0   94.65    .035       0  106.77     .08       0
#Block Obstruct= 5 ,-1
   28.71   47.42342.1049  284.31  323.33  342.54  240.64  252.95342.8019
     147  173.73342.1931  130.67  132.27  341.52
Bank Sta=94.65,106.77
XS Rating Curve= 0 ,0
Exp/Cntr=0.3,0.1

Type RM Length L Ch R = 1 ,15681.9 ,45.84,50,51.56
XS GIS Cut Line= 4
-611311.56309999   -1045988.0799    -611292.5808   -1045894.7576
-611286.29859999   -1045878.4296-611316.05409999   -1045626.6029
#Sta/Elev= 30
       0  346.88     .04  346.88     .49  345.31    3.76  345.57    4.88  341.26
    9.43  340.89   12.96  340.97   21.06  339.55   21.88  339.03   39.45  339.14
    59.2   338.9   84.71  338.27   93.97  338.39   99.23  335.91  100.76  335.82
  106.56  335.98  108.28  337.14  109.04  338.31  124.79  338.24  146.31  338.95
   163.9  338.73  164.34  339.68  176.38  339.83   221.8  339.76  252.17  339.34
  260.89  339.58  272.13  339.58  312.67  339.33  350.37  340.37  366.31  344.55
#Mann= 3 , 0 , 0
       0      .1       0   93.97    .035       0  109.04     .08       0
#Block Obstruct= 6 ,-1
   27.52   35.49342.0646  271.67  310.54342.4639  152.57  164.87342.2979
    50.8   60.03341.9404  122.69  126.81341.3354  128.89  146.45341.3354
Bank Sta=93.97,109.04
XS Rating Curve= 0 ,0
Exp/Cntr=0.3,0.1

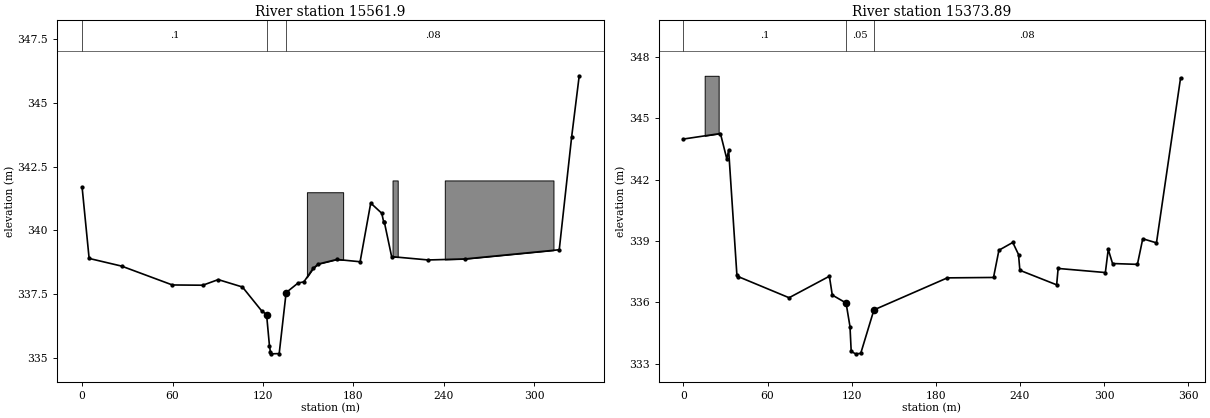
Type RM Length L Ch R = 1 ,15561.9 ,53.46,64.01,67.42
XS GIS Cut Line= 4
    -611358.8707   -1045988.0799    -611405.7524    -1045878.675
    -611406.3202   -1045860.2644    -611458.7895   -1045675.2631
#Sta/Elev= 30
       0   341.7    4.67   338.9   26.16   338.6   59.88  337.86   80.08  337.85
   90.31  338.07  106.36  337.78  119.03  336.85  122.37   336.7  124.27  335.48
  124.95  335.22  125.54  335.16  130.74  335.17  135.33  337.56  143.34  337.94
  147.09  337.98  153.27  338.51  156.65  338.68  168.99  338.86  184.41  338.77
  191.45  341.07  198.78  340.67  200.07  340.32   200.5  340.32  205.32  338.97
  229.63  338.84  253.98  338.88  316.49  339.24  324.73  343.67  329.74  346.06
#Mann= 3 , 0 , 0
       0      .1       0  122.37     .05       0  135.33     .08       0
#Block Obstruct= 3 ,-1
  205.92  209.34341.9575  240.57  312.66341.9575  149.11  173.16341.4943
Bank Sta=122.37,135.33
XS Rating Curve= 0 ,0
Exp/Cntr=0.3,0.1

Type RM Length L Ch R = 1 ,15373.89,10.94,373.89,55.99
XS GIS Cut Line= 4
    -611518.3532   -1046080.6446    -611558.4674   -1045974.2846
    -611559.0168   -1045956.5783    -611651.2961   -1045753.4009
#Sta/Elev= 30
       0  343.98   26.39  344.25   30.94  343.01   32.25  343.44   38.14  337.33
   39.14  337.26   75.35  336.23  104.09  337.28  106.16  336.36  115.99335.9734
  118.79  334.82  119.65  333.61  122.73  333.49  126.44  333.51  135.86335.6363
  188.19   337.2  221.15  337.22     225  338.55  234.88  338.93  238.98  338.34
  239.94  337.57  266.18  336.86  267.23  337.66  300.91  337.46  302.96  338.59
  306.04   337.9  323.77  337.86  327.58  339.11  337.36  338.91  354.54  346.96
#Mann= 3 , 0 , 0
       0      .1       0  115.99     .05       0  135.86     .08       0
#Block Obstruct= 1 ,-1
   15.15   25.12347.0693
Bank Sta=115.99,135.86
XS Rating Curve= 0 ,0
Exp/Cntr=0.3,0.1

Storage Area=2 d             ,-610540.495235,-1045544.7045207
Storage Area Surface Line= 6
      -610697.93      -1045533.5
      -610639.47     -1045650.25
      -610550.98     -1045663.49
      -610401.53     -1045562.28
       -610477.7     -1045392.73
      -610697.93      -1045533.5
Storage Area Type= 0
Storage Area Is2D=-1
Storage Area Point Generation Data=0,0,10,10
Storage Area 2D Points= 704
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Storage Area Mannings=0.08
2D Cell Volume Filter Tolerance=0.003
2D Face Profile Filter Tolerance=0.003
2D Face Area Elevation Profile Filter Tolerance=0.003
2D Face Area Elevation Conveyance Ratio=0.02

Connection=levee_orient    ,-610466.0997415,-1045594.3095341
Connection Line= 3
-610427.33971555-1045605.0687464-610453.91702174-1045570.4818411
-610553.30886543-1045631.6460526
Conn CellSize Min=2
Conn CellSize Max=8
Connection Up SA=2 d
Connection Dn SA=2 d
Conn Routing Type= 1
Conn Use RC Family=True
Conn OverFlow Method 2D=True
Conn Weir WD=2
Conn Weir Coef=1.66
Conn Weir Is Ogee= 0
Conn Simple Spill Pos Coef=0.05
Conn Simple Spill Neg Coef=0.05
Conn Weir SE= 2
       0     350 160.323     350
LCMann Table=0

--- PPO_Kvasiny_efektiv.g06 (geometry) ---

Geom Title=S-Q5
Program Version=5.03

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
River Reach=Bela            ,Bela_reach

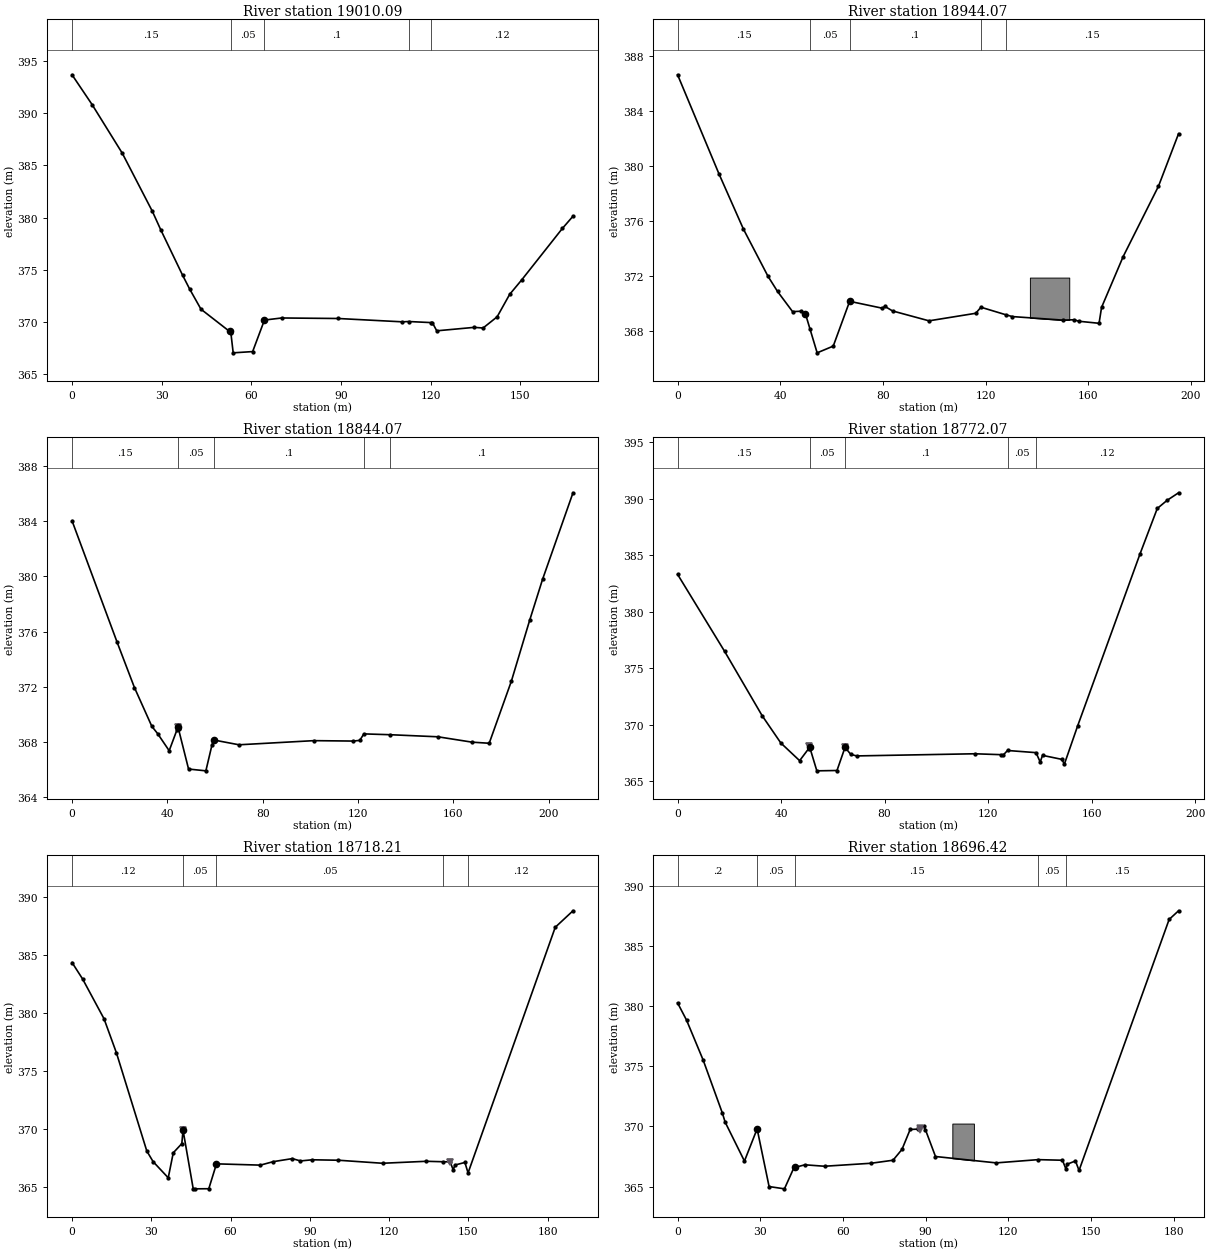
Type RM Length L Ch R = 1 ,19010.09,63.81,66.01,58.86
XS GIS Cut Line= 5
-608502.66209999   -1044593.6857    -608536.6251   -1044560.8986
     -608549.118   -1044545.2805    -608586.5786   -1044508.0775
     -608607.896   -1044465.4426
#Sta/Elev= 27
       0  393.68    6.75  390.81   16.83  386.16    26.9  380.59   29.66  378.85
   36.98  374.49   39.39  373.14   43.16  371.22   52.73  369.09   53.15 368.985
   53.94  367.04   60.45  367.16    64.4370.1805   70.18  370.38   89.09  370.33
   110.6  370.01  112.68  370.04     120  369.94  120.58  369.94  122.07  369.15
  134.59  369.48  137.58  369.42  142.28  370.49  146.47  372.64  150.45  374.01
  164.12  378.96  167.67  380.13
#Mann= 5 ,-1 , 0
       0     .15       0   53.15     .05       0    64.4      .1       0
  112.68     .05       0     120     .12       0
Bank Sta=52.73,64.4
XS Rating Curve= 0 ,0
Exp/Cntr=0.3,0.1

Type RM Length L Ch R = 1 ,18944.07,107.06,100,81.52
XS GIS Cut Line= 5
    -608546.4782   -1044642.7763-608578.86259999   -1044608.0005
     -608594.864   -1044596.0024    -608642.9144   -1044514.1948
    -608653.0656   -1044483.0645
#Sta/Elev= 29
       0  386.63   16.09  379.43   25.66  375.39   35.22  371.96   38.92  370.86
   44.79  369.39   48.23  369.42    49.8  369.23   51.56368.1339   54.36  366.39
   60.63  366.88   67.02  370.14   67.03370.1393   79.71  369.64   80.76  369.77
   83.72  369.44   97.93  368.72  116.15  369.27  118.16  369.71   127.9369.1595
  130.38  369.03  150.14  368.77  154.47   368.8  156.24  368.69  164.17  368.54
  165.15   369.7  173.57   373.4  187.32  378.52  195.14  382.34
#Mann= 5 ,-1 , 0
       0     .15       0   51.56     .05       0   67.03      .1       0
  118.16     .05       0   127.9     .15       0
#Block Obstruct= 1 ,-1
  137.23  152.56371.8682
Bank Sta=49.8,67.02
XS Rating Curve= 0 ,0
Exp/Cntr=0.3,0.1

Type RM Length L Ch R = 1 ,18844.07,72.16,72,73.34
XS GIS Cut Line= 6
-608649.34349999   -1044712.1427    -608661.1943   -1044671.2681
    -608666.6842   -1044652.0363-608687.57959999     -1044587.96
    -608711.2657   -1044551.4157    -608740.0273   -1044528.7448
#Sta/Elev= 27
       0  384.04   18.89  375.24   26.18  371.94   33.47  369.13    35.9   368.6
   40.75  367.36   44.03  368.88   44.35  369.09   44.67  368.93   48.88  366.03
   56.14   365.9   58.65  367.74   59.34  368.14   59.46368.1367   70.03  367.79
  101.43  368.09     118  368.06  120.69  368.11  122.41  368.58  133.48  368.52
  153.46  368.37  167.81  367.98  174.98   367.9  184.29  372.41  191.95  376.82
  197.36  379.79  210.13  386.07
#Mann= 5 ,-1 , 0
       0     .15       0   44.35     .05       0   59.46      .1       0
  122.41     .05       0  133.48      .1       0
Levee=-1,44.3,369.1,0,,,,
Bank Sta=44.35,59.46
XS Rating Curve= 0 ,0
Exp/Cntr=0.3,0.1

Type RM Length L Ch R = 1 ,18772.07,49.5,53.87,46.34
XS GIS Cut Line= 5
-608717.01799999   -1044739.5508    -608729.3973    -1044693.413
    -608735.3242   -1044674.3114    -608762.3599   -1044598.1112
    -608783.6774   -1044558.5216
#Sta/Elev= 27
       0  383.29   18.17  376.48   32.67  370.79   39.91  368.37   47.16  366.81
   50.67  367.88   50.91  368.11   50.99368.0506   53.81  365.91    61.6  365.94
    64.7367.9844   66.95  367.36   69.23  367.23  114.85  367.42     125  367.34
  125.72  367.28   127.5  367.71  138.51  367.52  140.12  366.69  141.02  367.28
  148.38  366.93  149.49  366.52  154.63  369.91  178.71  385.11  185.36  389.12
  189.15  389.84  193.59  390.51
#Mann= 5 ,-1 , 0
       0     .15       0   50.99     .05       0    64.7      .1       0
   127.5     .05       0  138.51     .12       0
Levee=-1,50.87,368.11,-1,64.69,367.98,,
Bank Sta=50.99,64.7
XS Rating Curve= 0 ,0
Exp/Cntr=0.3,0.1

Type RM Length L Ch R = 1 ,18718.21,29.06,21.79,6.52
XS GIS Cut Line= 5
-608753.54699999   -1044753.4637     -608781.487   -1044705.5211
    -608789.4245   -1044670.2786    -608798.9496    -1044622.336
-608821.80959999   -1044578.8384
#Sta/Elev= 30
       0  384.35    4.01  382.93   12.11  379.51   16.79  376.59   28.31  368.13
   30.69  367.22   36.42  365.83   38.32  367.98   41.56  368.77   42.02  369.93
   45.86   364.9   46.37  364.88   51.77  364.89   54.68  367.03   71.29  366.92
    76.2  367.22   83.37  367.48   86.48  367.28   90.94  367.38  100.86  367.34
  117.53  367.08  134.11  367.25  140.49  367.21  143.13   367.2  144.27  366.52
  144.99  366.93  148.71  367.15  149.91  366.25  182.91  387.38  189.63   388.8
#Mann= 5 ,-1 , 0
       0     .12       0   42.02     .05       0   54.68     .05       0
  140.49     .05       0  149.91     .12       0
Levee=-1,42.02,369.93,-1,142.96,367.15,,
Bank Sta=42.02,54.68
XS Rating Curve= 0 ,0
Exp/Cntr=0.3,0.1

Type RM Length L Ch R = 1 ,18696.42,50.22,38.35,4.09
XS GIS Cut Line= 4
-608796.05849999    -1044760.252    -608795.7939   -1044693.8414
    -608803.2023   -1044622.1392    -608824.1044   -1044584.3037
#Sta/Elev= 30
       0  380.28    3.25  378.85    9.27  375.53   16.25  371.11   17.25  370.36
   24.25  367.12   28.85   369.8   33.19     365   38.76  364.81   42.24  366.59
    42.5  366.59   46.19  366.81   53.31  366.69   70.21  366.94   78.14  367.19
   81.39  368.09   84.36  369.75   87.08  369.78   89.29     370   89.92  369.72
   93.55   367.5  115.58  366.97  130.78  367.24  139.61  367.19  140.83  366.48
  141.43  366.87  144.32  367.13  145.62  366.34   178.3  387.23  181.72  387.95
#Mann= 5 ,-1 , 0
       0      .2       0   28.85     .05       0    42.5     .15       0
  130.78     .05       0  140.83     .15       0
Levee=0,,,-1,87.99,369.73,,
#Block Obstruct= 1 ,-1
   99.66  107.48370.2419
Bank Sta=28.85,42.5
XS Rating Curve= 0 ,0
Exp/Cntr=0.3,0.1

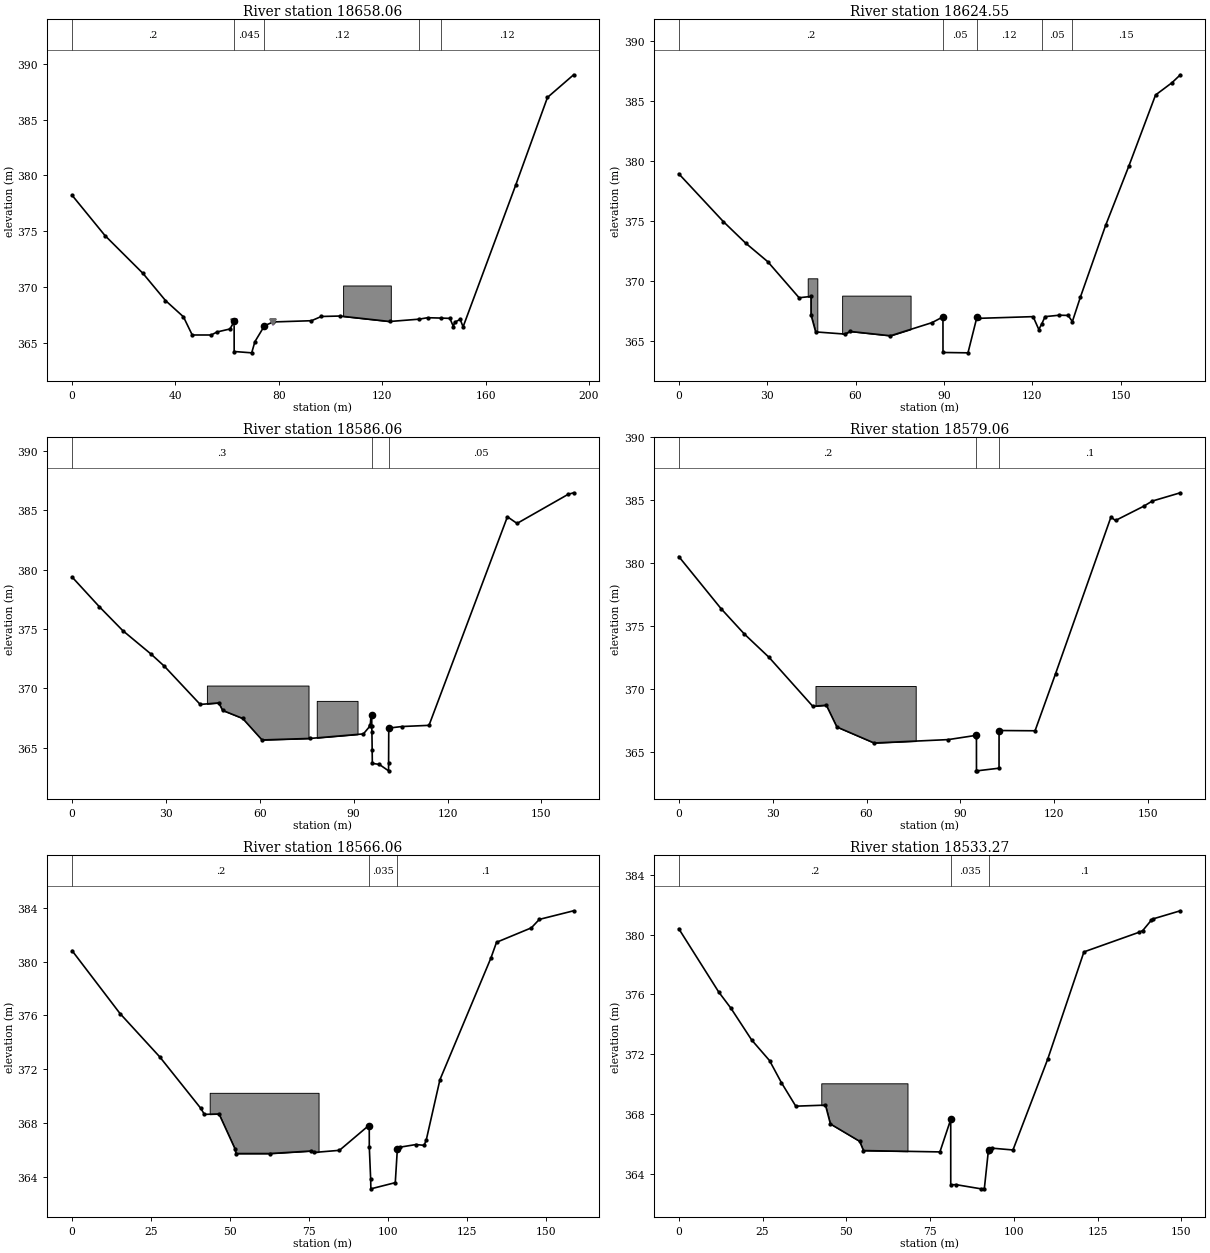
Type RM Length L Ch R = 1 ,18658.06,22,33.51,26.87
XS GIS Cut Line= 6
-608811.08549999    -1044755.116     -608825.589   -1044701.0257
    -608807.8792   -1044691.7325-608803.30299999   -1044664.7705
    -608806.6867   -1044622.1356-608834.09479999   -1044582.8844
#Sta/Elev= 30
       0  378.22   12.72  374.61   27.41  371.22   36.15  368.78    43.1  367.32
    46.5  365.69   53.84  365.69   56.09  365.96   61.11  366.23   62.71   366.9
   62.73  364.21   69.51  364.09   70.75  365.09   74.46366.5206   77.86  366.86
   92.64  366.97   96.45  367.35  103.66  367.39  122.92   366.9  134.34  367.11
  137.58  367.24   142.8367.2064  146.19  367.18  147.55  366.45  148.03  366.83
  150.17  367.09  151.31  366.42  171.67  379.13  183.96  386.99  194.08  389.02
#Mann= 5 ,-1 , 0
       0      .2       0   62.71    .045       0   74.46     .12       0
  134.34     .05       0   142.8     .12       0
Levee=-1,62.62,366.83,-1,77.85,366.86,,
#Block Obstruct= 1 ,-1
  104.88  123.34370.1295
Bank Sta=62.71,74.46
XS Rating Curve= 0 ,0
Exp/Cntr=0.3,0.1

Type RM Length L Ch R = 1 ,18624.55,27.54,38.49,47.2
XS GIS Cut Line= 6
    -608813.3292   -1044757.0751-608830.65819999   -1044713.3605
     -608838.708   -1044671.6675    -608829.9133   -1044663.7088
    -608830.5483   -1044653.6758    -608851.3869   -1044598.6741
#Sta/Elev= 30
       0  378.92   15.14  374.94   22.67  373.16    30.2  371.61   40.84  368.61
   44.87  368.72   44.88  367.19   46.46  365.77   56.35  365.59   58.15  365.81
   71.85  365.45   85.93  366.54   89.66  367.02   89.67  364.06   98.15  364.03
   101.2  367.01  101.96   366.9  120.26  367.04  122.19  365.97  123.18  366.43
  124.31  367.04  129.18  367.16  132.12  367.14  133.58  366.63  136.31  368.67
  144.85  374.62  152.76  379.57  161.81  385.47  167.38  386.49  170.22  387.15
#Mann= 5 ,-1 , 0
       0      .2       0   89.66     .05       0   101.2     .12       0
  123.18     .05       0  133.58     .15       0
#Block Obstruct= 2 ,-1
   43.76   47.02 370.226   55.44   78.67368.7872
Bank Sta=89.66,101.2
XS Rating Curve= 0 ,0
Exp/Cntr=0.3,0.1

Type RM Length L Ch R = 1 ,18586.06,7.01,7,6.98
XS GIS Cut Line= 5
-608816.16099999   -1044758.1613-608829.69599999   -1044721.9555
-608861.31879999   -1044682.8263    -608874.4763   -1044667.7636
    -608911.2437   -1044631.9484
#Sta/Elev= 30
       0  379.37    8.71  376.87   16.19  374.86   25.24  372.88   29.53  371.85
   40.95  368.64   46.89  368.77   48.11  368.14   54.53  367.46   60.71  365.65
    76.2  365.78   93.11  366.16   95.27  366.84   95.31  366.91   95.55  367.76
   95.77  367.75   95.78  366.84   95.83  366.33   95.91   364.8   95.96  363.68
   98.19  363.59  101.15  363.05  101.16   363.7  101.21  366.65  105.39  366.78
  114.07  366.88  139.13  384.44  142.21  383.88  158.54  386.33  160.29  386.46
#Mann= 3 , 0 , 0
       0      .3       0   95.77    .035       0  101.21     .05       0
#Block Obstruct= 2 ,-1
    78.2   91.23368.9392   43.09   75.57370.2309
Bank Sta=95.77,101.21
XS Rating Curve= 0 ,0
Exp/Cntr=0.3,0.1

Type RM Length L Ch R = 1 ,18579.06,11.58,13.01,14.24
XS GIS Cut Line= 5
-608821.51799999    -1044762.635    -608835.0529   -1044726.4292
    -608866.6757      -1044687.3    -608879.8332   -1044672.2374
-608916.60069999   -1044636.4221
#Sta/Elev= 22
       0  380.53   13.49   376.4   20.96  374.38   28.84  372.53   42.84  368.64
   47.15  368.73   50.53     367   62.43  365.73   86.13     366   95.11  366.34
   95.13  366.19   95.14  363.53    95.3  363.52  102.35  363.73  102.36  366.72
  113.86   366.7   120.4  371.22  138.11  383.66  139.57  383.39  148.64  384.53
  151.29  384.93  160.29  385.59
#Mann= 3 , 0 , 0
       0      .2       0   95.11    .035       0  102.36      .1       0
#Block Obstruct= 1 ,-1
   43.69   75.72 370.257
Bank Sta=95.11,102.36
XS Rating Curve= 0 ,0
Exp/Cntr=0.3,0.1

Type RM Length L Ch R = 1 ,18566.06,31.65,32.78,32.95
XS GIS Cut Line= 5
-608821.57499999   -1044763.5753    -608827.6657   -1044750.7171
-608875.58549999   -1044694.5559    -608890.8203   -1044681.5982
-608930.53099999   -1044650.2205
#Sta/Elev= 29
       0  380.81   15.17  376.14   27.74  372.92   40.72   369.1   41.86  368.65
    46.5  368.68   51.51  366.11   51.86  365.74    62.5  365.74   75.63  365.93
   76.44  365.82   84.59  365.98   93.69  367.79   94.02  367.78   94.03  366.24
   94.46  363.86   94.53  363.12  102.25  363.58  102.91  366.09  103.89  366.22
  108.79  366.41  111.38  366.35  112.06  366.76  116.37  371.22  132.52  380.27
  134.28  381.43  145.28   382.5  147.82  383.13  158.67  383.77
#Mann= 3 , 0 , 0
       0      .2       0   94.02    .035       0  102.91      .1       0
#Block Obstruct= 1 ,-1
   43.54   77.98370.2509
Bank Sta=94.02,102.91
XS Rating Curve= 0 ,0
Exp/Cntr=0.3,0.1

Type RM Length L Ch R = 1 ,18533.27,12.87,12.37,12.43
XS GIS Cut Line= 4
    -608836.7278   -1044771.9928-608886.99879999   -1044726.4844
    -608909.2238   -1044709.0218    -608949.4406   -1044673.5676
#Sta/Elev= 28
       0   380.4   11.91  376.17   15.57  375.08   21.75  372.96   27.09  371.58
   30.64   370.1   34.92  368.53   43.78   368.6   45.25  367.34   53.98  366.18
   55.12  365.56   77.94  365.47   81.16  367.64   81.17  363.27   82.75  363.28
   90.22     363    91.2  363.02   92.37  365.49   92.53   365.6   93.52  365.72
   99.74   365.6   110.1  371.67  120.92  378.85  137.46  380.17  138.48  380.28
  141.03  380.97  141.59  381.06  149.69   381.6
#Mann= 3 , 0 , 0
       0      .2       0   81.16    .035       0   92.53      .1       0
#Block Obstruct= 1 ,-1
   42.53   68.26370.0591
Bank Sta=81.16,92.53
XS Rating Curve= 0 ,0
Exp/Cntr=0.3,0.1

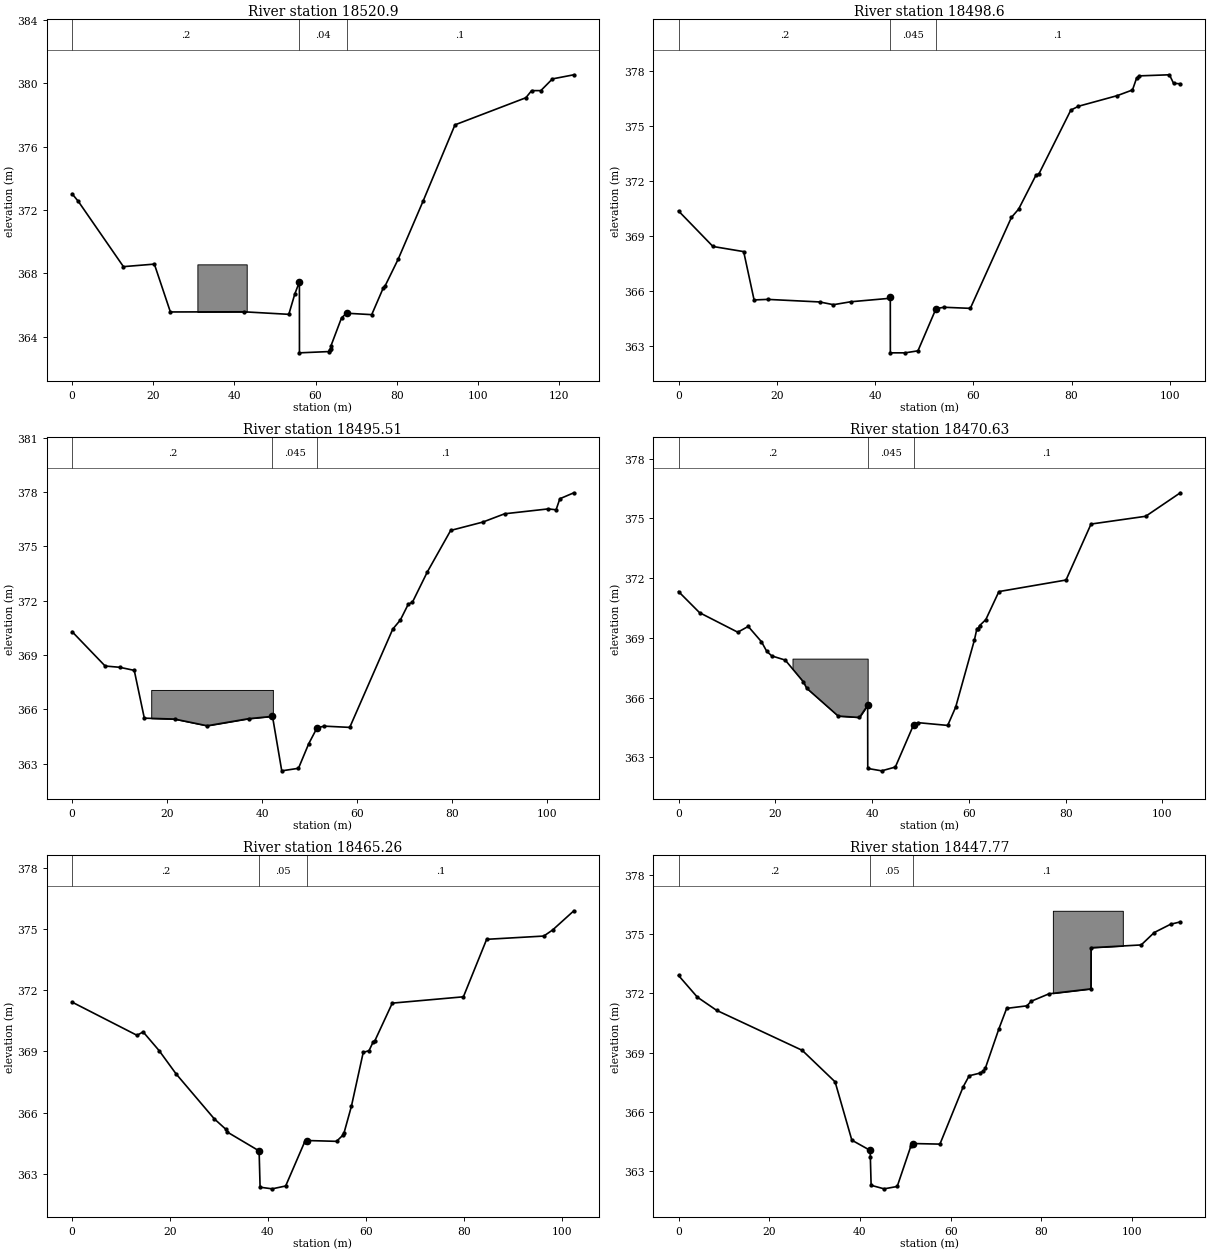
Type RM Length L Ch R = 1 ,18520.9 ,21.89,22.29,22.52
XS GIS Cut Line= 4
    -608863.4842   -1044765.4406-608906.08109999   -1044727.1808
-608921.42689999     -1044715.01    -608957.6926   -1044685.3842
#Sta/Elev= 27
       0  373.03    1.54  372.55   12.66  368.43   20.28  368.59   24.23  365.57
   42.35  365.58   53.42  365.42   54.89   366.7   56.03  367.47   56.04  362.99
   63.28  363.07   63.48   363.2   63.73  363.25   63.82  363.44   66.43  365.21
   67.69  365.49   73.85   365.4   76.67  367.07   77.16  367.22   80.37   368.9
    86.5  372.56   94.37  377.38  111.84  379.09  113.26  379.54  115.53  379.54
  118.39  380.28  123.67  380.54
#Mann= 3 , 0 , 0
       0      .2       0   56.03     .04       0   67.69      .1       0
#Block Obstruct= 1 ,-1
   30.89   43.04368.5746
Bank Sta=56.03,67.69
XS Rating Curve= 0 ,0
Exp/Cntr=0.3,0.1

Type RM Length L Ch R = 1 ,18498.6 ,2.83,3.09,3.31
XS GIS Cut Line= 4
    -608885.6669   -1044772.6373    -608919.2351   -1044745.1325
    -608935.1101   -1044732.9616    -608964.8046   -1044708.0749
#Sta/Elev= 29
       0  370.37    7.01  368.43   13.26  368.15   15.38  365.51   18.15  365.54
   28.73   365.4   31.54  365.25   35.05  365.41   43.04   365.6   43.11  365.66
   43.12  362.62   46.14  362.62   48.74  362.73   52.41  365.03   53.99  365.11
    59.4  365.05   67.77  370.02   69.23  370.47   72.79  372.34   73.35  372.39
   79.86  375.88   81.41  376.09    89.3  376.67   92.41  376.98   93.25  377.63
   93.77  377.75   99.93  377.81  100.78  377.34  102.15  377.32
#Mann= 3 , 0 , 0
       0      .2       0   43.11    .045       0   52.41      .1       0
Bank Sta=43.11,52.41
XS Rating Curve= 0 ,0
Exp/Cntr=0.3,0.1

Type RM Length L Ch R = 1 ,18495.51,25.6,24.88,23.57
XS GIS Cut Line= 4
    -608887.9529   -1044774.1613    -608917.6792   -1044750.0879
    -608934.0835    -1044737.917    -608970.0669   -1044707.7544
#Sta/Elev= 27
       0  370.29    6.96  368.39   10.03  368.32   13.09  368.15   15.21  365.51
   21.57  365.46   28.43  365.09   37.14  365.48   42.19  365.61   44.14   362.6
   47.66  362.74   49.82   364.1   51.54  364.96   53.01  365.07   58.45     365
   67.51  370.43    69.1  370.93    70.8  371.82   71.62   371.9   74.81   373.6
    79.7  375.88   86.45  376.34   91.06   376.8  100.25  377.07  101.89  377.02
  102.68  377.63  105.63  377.96
#Mann= 3 , 0 , 0
       0      .2       0   42.19    .045       0   51.54      .1       0
#Block Obstruct= 1 ,-1
   16.66   42.27367.0693
Bank Sta=42.19,51.54
XS Rating Curve= 0 ,0
Exp/Cntr=0.3,0.1

Type RM Length L Ch R = 1 ,18470.63,5.16,5.37,5.75
XS GIS Cut Line= 4
-608906.65179999   -1044793.0242    -608930.3372   -1044772.7807
-608945.32779999   -1044759.5411    -608983.9917   -1044723.9844
#Sta/Elev= 30
       0  371.32    4.35  370.26   12.24  369.28    14.4  369.57   17.14   368.8
   18.23  368.32   19.27  368.09   22.05  367.88   25.79  366.79   26.47  366.47
   32.99  365.07   37.38     365   39.08  365.61    39.1  362.44   41.97  362.32
    44.8  362.51   48.59  364.64   49.46  364.74   55.62   364.6   57.27  365.52
   61.13  368.88   61.66  369.46   61.92  369.46   62.21  369.61   63.49  369.91
    66.2  371.32   80.07   371.9   85.24  374.71   96.53   375.1  103.69  376.28
#Mann= 3 , 0 , 0
       0      .2       0   39.08    .045       0   48.59      .1       0
#Block Obstruct= 1 ,-1
   23.55   39.08 367.954
Bank Sta=39.08,48.59
XS Rating Curve= 0 ,0
Exp/Cntr=0.3,0.1

Type RM Length L Ch R = 1 ,18465.26,17.65,17.49,17.14
XS GIS Cut Line= 2
    -608910.5632   -1044796.3117    -608988.7089   -1044730.0063
#Sta/Elev= 28
       0  371.42   13.27  369.79   14.51  369.96   17.78  369.04   21.24   367.9
   29.02   365.7   31.41  365.18   31.74  365.04    38.2  364.12    38.4  362.34
   40.87  362.26   43.62   362.4    47.5  364.56   48.04  364.63   54.01  364.59
    55.3  364.89   55.55  365.01   57.04   366.3   59.46  368.95   60.65  369.04
   61.48  369.46   61.85  369.53    65.4  371.37   79.92  371.68   84.67   374.5
   96.34  374.66   98.15  374.96  102.48   375.9
#Mann= 3 , 0 , 0
       0      .2       0    38.2     .05       0   48.04      .1       0
Bank Sta=38.2,48.04
XS Rating Curve= 0 ,0
Exp/Cntr=0.3,0.1

Type RM Length L Ch R = 1 ,18447.77,15.66,15.93,16.64
XS GIS Cut Line= 4
-608918.60229999   -1044812.6923-608948.38219999   -1044787.3387
    -608962.1406   -1044775.1678    -609000.7698   -1044738.6552
#Sta/Elev= 30
       0  372.91    4.15  371.81     8.4  371.14   27.27  369.11   34.52  367.51
   38.21  364.55   42.26  364.03   42.29  363.69   42.46  362.26   45.32  362.08
   48.21   362.2   51.24  364.26   51.65  364.38   57.63  364.35   62.76  367.26
   64.08  367.82   66.39  367.95    67.2  368.05   67.64   368.2   70.61  370.19
   72.34  371.24   76.82  371.37   77.73   371.6   81.68  371.98   90.92  372.23
   90.94  374.32     102  374.46  104.88  375.09  108.48  375.51  110.63  375.63
#Mann= 3 , 0 , 0
       0      .2       0   42.26     .05       0   51.65      .1       0
#Block Obstruct= 1 ,-1
   82.53   97.95376.1941
Bank Sta=42.26,51.65
XS Rating Curve= 0 ,0
Exp/Cntr=0.3,0.1

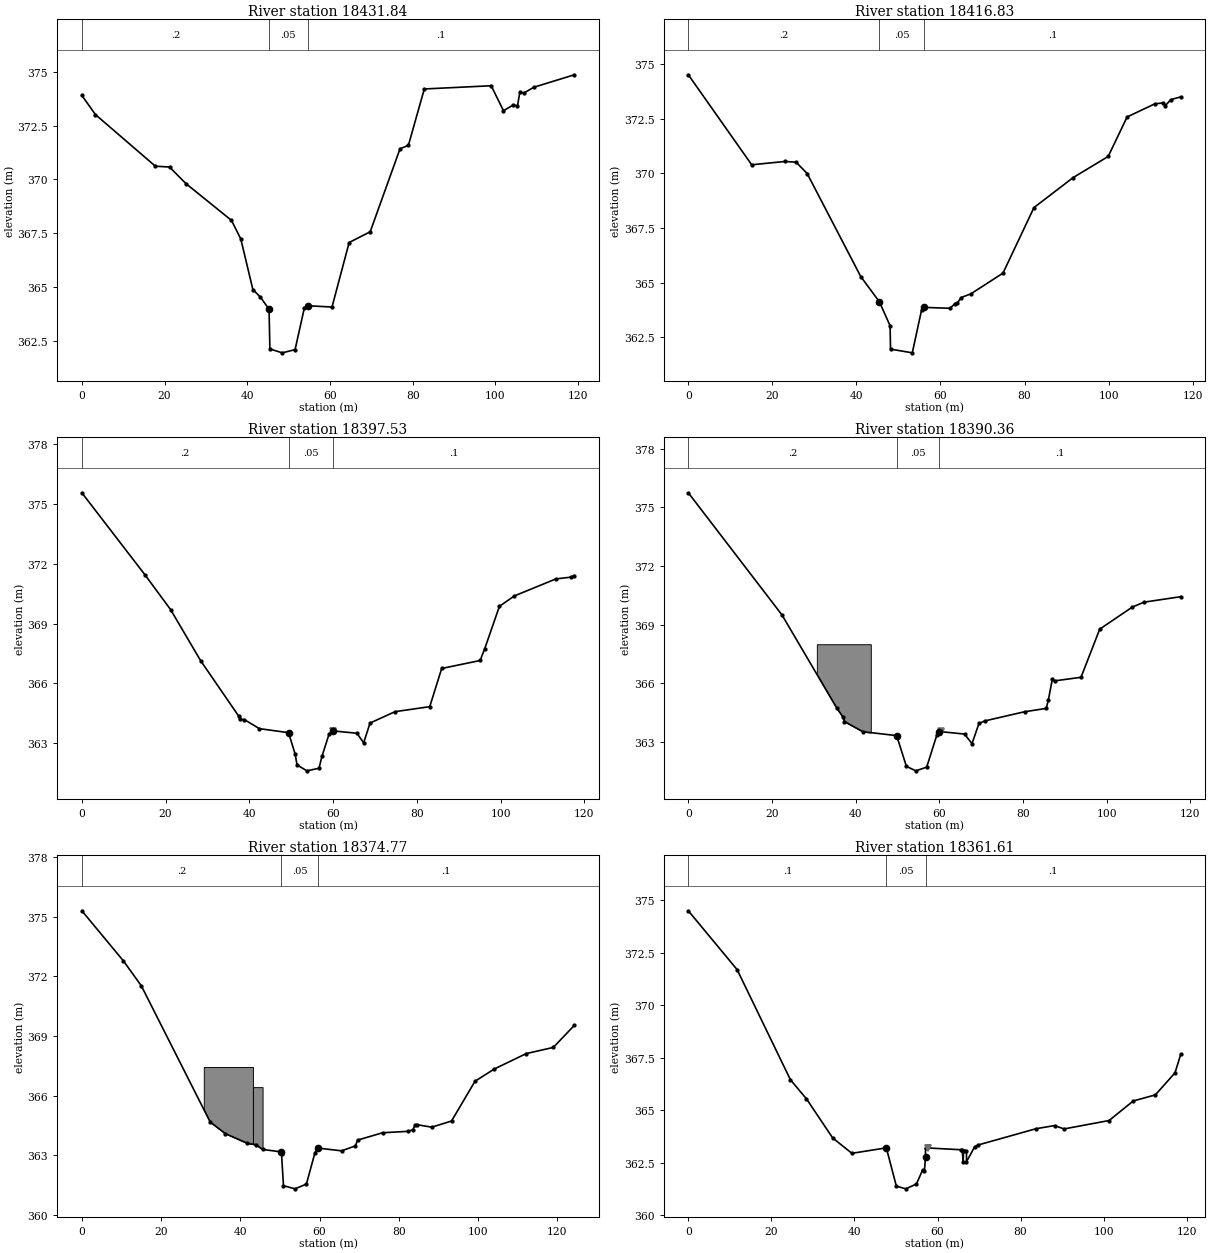
Type RM Length L Ch R = 1 ,18431.84,14.94,15.01,15.06
XS GIS Cut Line= 4
-608926.42619999   -1044827.1558    -608957.9395   -1044799.6768
-608973.81459999   -1044786.9768    -609015.6187   -1044748.3474
#Sta/Elev= 30
       0   373.9    3.28  373.01   17.77  370.61    21.2  370.57   25.16   369.8
   36.17  368.09   38.42  367.23   41.35  364.87   43.18  364.52   45.17  363.98
   45.26  363.94   45.46  362.11   48.45  361.93   51.55  362.08   53.78  364.01
   54.56  364.12   60.48  364.06   64.62  367.06   69.71  367.56   76.92  371.42
   78.95  371.58   82.79   374.2   98.96  374.35  101.93  373.19  104.34  373.46
  105.32  373.41  105.89  374.06  106.87  374.01  109.27  374.28  119.06  374.86
#Mann= 3 , 0 , 0
       0      .2       0   45.17     .05       0   54.56      .1       0
Bank Sta=45.17,54.56
XS Rating Curve= 0 ,0
Exp/Cntr=0.3,0.1

Type RM Length L Ch R = 1 ,18416.83,19.51,19.31,18.8
XS GIS Cut Line= 4
    -608933.7448   -1044840.0106    -608967.9937   -1044810.7893
-608985.98539999   -1044796.5017    -609023.5562   -1044764.7517
#Sta/Elev= 27
       0  374.51   15.08  370.39   22.91  370.54   25.64  370.51   28.28  369.99
   41.04  365.27   45.46  364.12   48.01  363.02   48.12  361.95    53.3  361.78
   55.49  363.73   56.19  363.86   62.29  363.82   63.37  364.02   64.02  364.06
   64.91  364.31   67.23  364.48   74.88  365.43   82.25  368.43   91.55   369.8
   99.91  370.77  104.42  372.58  111.02  373.18  112.87  373.22  113.53   373.1
   114.8  373.37  117.19   373.5
#Mann= 3 , 0 , 0
       0      .2       0   45.46     .05       0   56.19      .1       0
Bank Sta=45.46,56.19
XS Rating Curve= 0 ,0
Exp/Cntr=0.3,0.1

Type RM Length L Ch R = 1 ,18397.53,7.24,7.17,6.9
XS GIS Cut Line= 4
-608943.77299999   -1044858.6939-608978.04789999   -1044827.7227
    -608998.6854   -1044810.2602    -609033.0813   -1044782.2143
#Sta/Elev= 29
       0  375.54   15.13  371.42   21.18   369.7   28.37  367.14   37.48  364.36
   37.74   364.2   38.84  364.19   42.41  363.74   49.36  363.54   50.95  362.46
   51.38  361.93   53.74  361.63   56.63  361.76   57.34  362.35   59.02  363.46
   59.91  363.63    65.7  363.51    67.3  363.03   68.82  364.02   74.78  364.59
   83.08  364.84   85.93  366.75   95.12  367.15   96.23  367.75   99.72  369.86
  103.29  370.38   113.2  371.23  116.84  371.32  117.61   371.4
#Mann= 3 , 0 , 0
       0      .2       0   49.36     .05       0   59.91      .1       0
Levee=0,,,-1,59.93,363.63,,
Bank Sta=49.36,59.91
XS Rating Curve= 0 ,0
Exp/Cntr=0.3,0.1

Type RM Length L Ch R = 1 ,18390.36,15.99,15.59,15.07
XS GIS Cut Line= 2
    -608947.5425   -1044864.1187-609036.10399999   -1044786.5639
#Sta/Elev= 26
       0  375.74   22.38   369.5    35.5  364.73   36.92  364.29   37.32  364.05
   41.73  363.53    49.8  363.33   52.13  361.76   54.39  361.53   56.98  361.72
   59.42  363.37   59.95  363.54   66.02  363.41   67.81  362.92   69.47  363.95
   70.84  364.08   80.38  364.55   85.55  364.72   86.08  365.17      87   366.2
   87.62  366.13   93.87  366.31   98.34  368.77  106.14   369.9  108.95  370.15
  117.72  370.43
#Mann= 3 , 0 , 0
       0      .2       0    49.8     .05       0   59.95      .1       0
Levee=0,,,-1,60.42,363.55,,
#Block Obstruct= 1 ,-1
   30.72   43.62368.0001
Bank Sta=49.8,59.95
XS Rating Curve= 0 ,0
Exp/Cntr=0.3,0.1

Type RM Length L Ch R = 1 ,18374.77,12.72,13.16,13.09
XS GIS Cut Line= 3
-608959.05689999   -1044877.1776-609013.50209999   -1044826.1352
-609048.81949999   -1044791.2347
#Sta/Elev= 30
       0   375.3   10.49  372.78      15  371.53   32.38  364.68   36.18   364.1
   41.76  363.61   43.91  363.54   45.61   363.3   50.25  363.18    50.4  363.05
   50.88  361.48   53.79  361.32   56.67  361.56   58.83  363.14   59.59  363.37
   65.56  363.23   69.04  363.48   69.57  363.77   75.91  364.14   82.26  364.21
   83.54  364.29   84.04  364.51   84.48  364.55    88.3  364.42   93.29  364.73
   99.22  366.73  104.13  367.35  112.15  368.12  118.98  368.43  124.28  369.54
#Mann= 3 , 0 , 0
       0      .2       0   50.25     .05       0   59.59      .1       0
#Block Obstruct= 2 ,-1
   30.77   43.17367.4476   43.17   45.61366.4337
Bank Sta=50.25,59.59
XS Rating Curve= 0 ,0
Exp/Cntr=0.3,0.1

Type RM Length L Ch R = 1 ,18361.61,12.22,11.56,10.47
XS GIS Cut Line= 3
    -608967.6932   -1044884.2694     -609015.221   -1044843.1214
-609052.62759999   -1044801.8585
#Sta/Elev= 30
       0  374.49   11.75  371.69   24.58  366.45   28.45  365.54   34.76  363.68
   39.38  362.95   47.67  363.21   50.08  361.39   52.34  361.26   54.92  361.49
   56.46  362.18   56.84   362.1    57.1  362.77    57.1  363.21   65.69  363.12
   65.93  363.09   66.18  362.54   66.26  363.08   66.97  363.08   66.97  362.55
   68.93  363.26   69.65  363.34   83.69  364.12   88.17  364.27   90.45  364.11
  101.29  364.51  107.11  365.44  112.43  365.73  117.17  366.78  118.56  367.67
#Mann= 3 , 0 , 0
       0      .1       0   47.67     .05       0    57.1      .1       0
Levee=0,,,-1,57.79,363.21,,
Bank Sta=47.67,57.1
XS Rating Curve= 0 ,0
Exp/Cntr=0.3,0.1