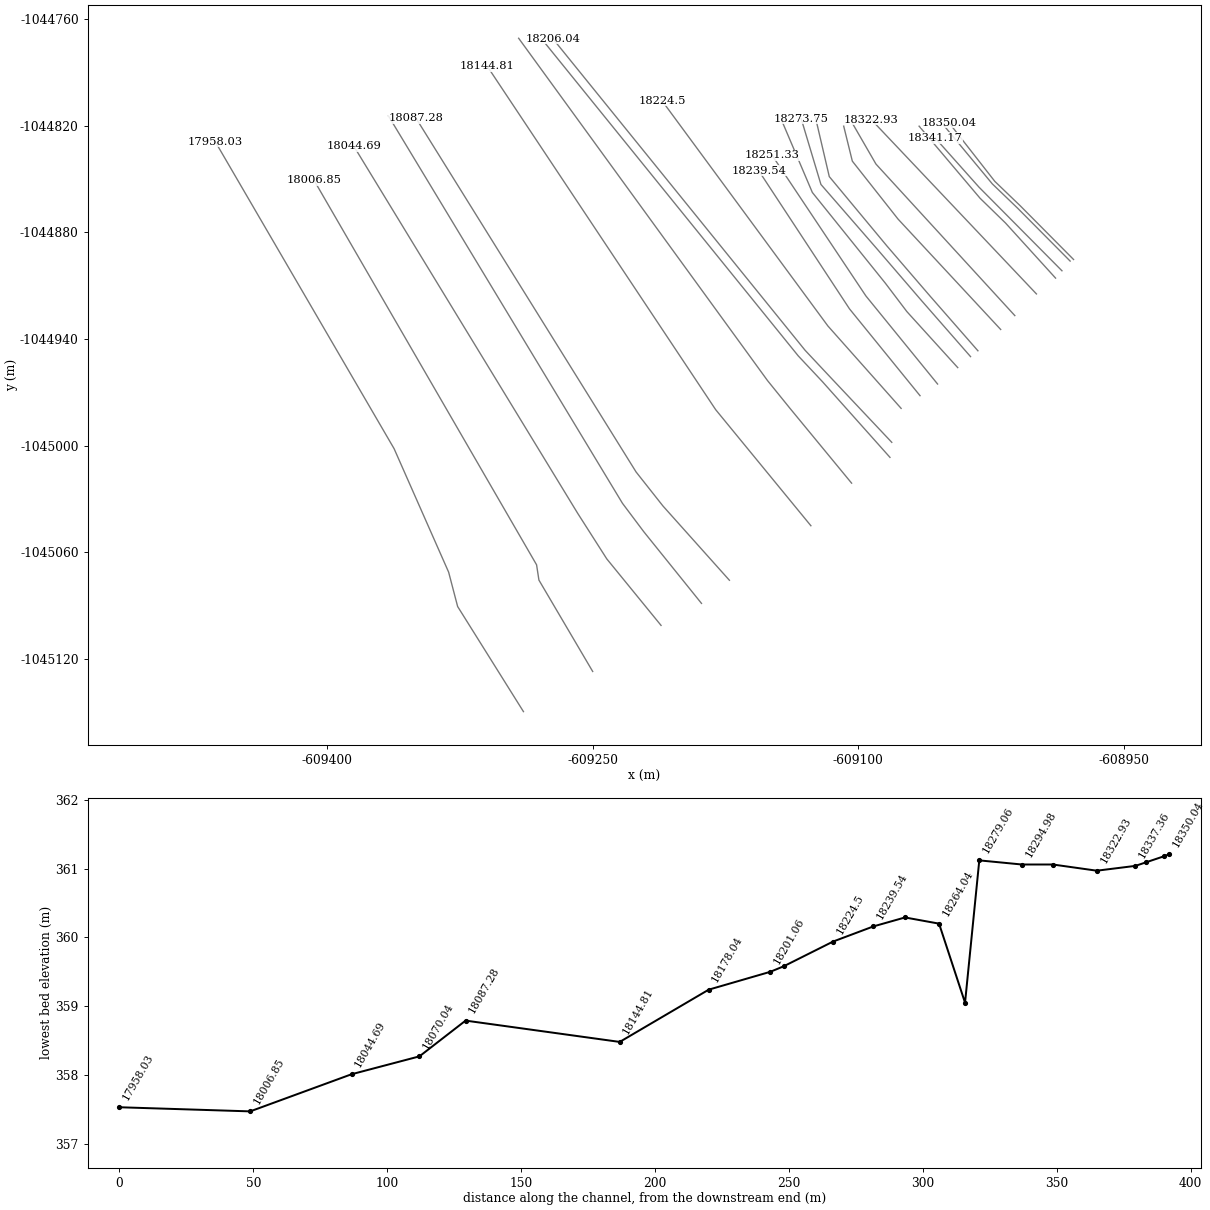
HEC-RAS study PPO_Kvasiny_efektiv.prj: PPO_Kvasiny_efektivita

--- PPO_Kvasiny_efektiv.g06 (geometry) --- (continued)

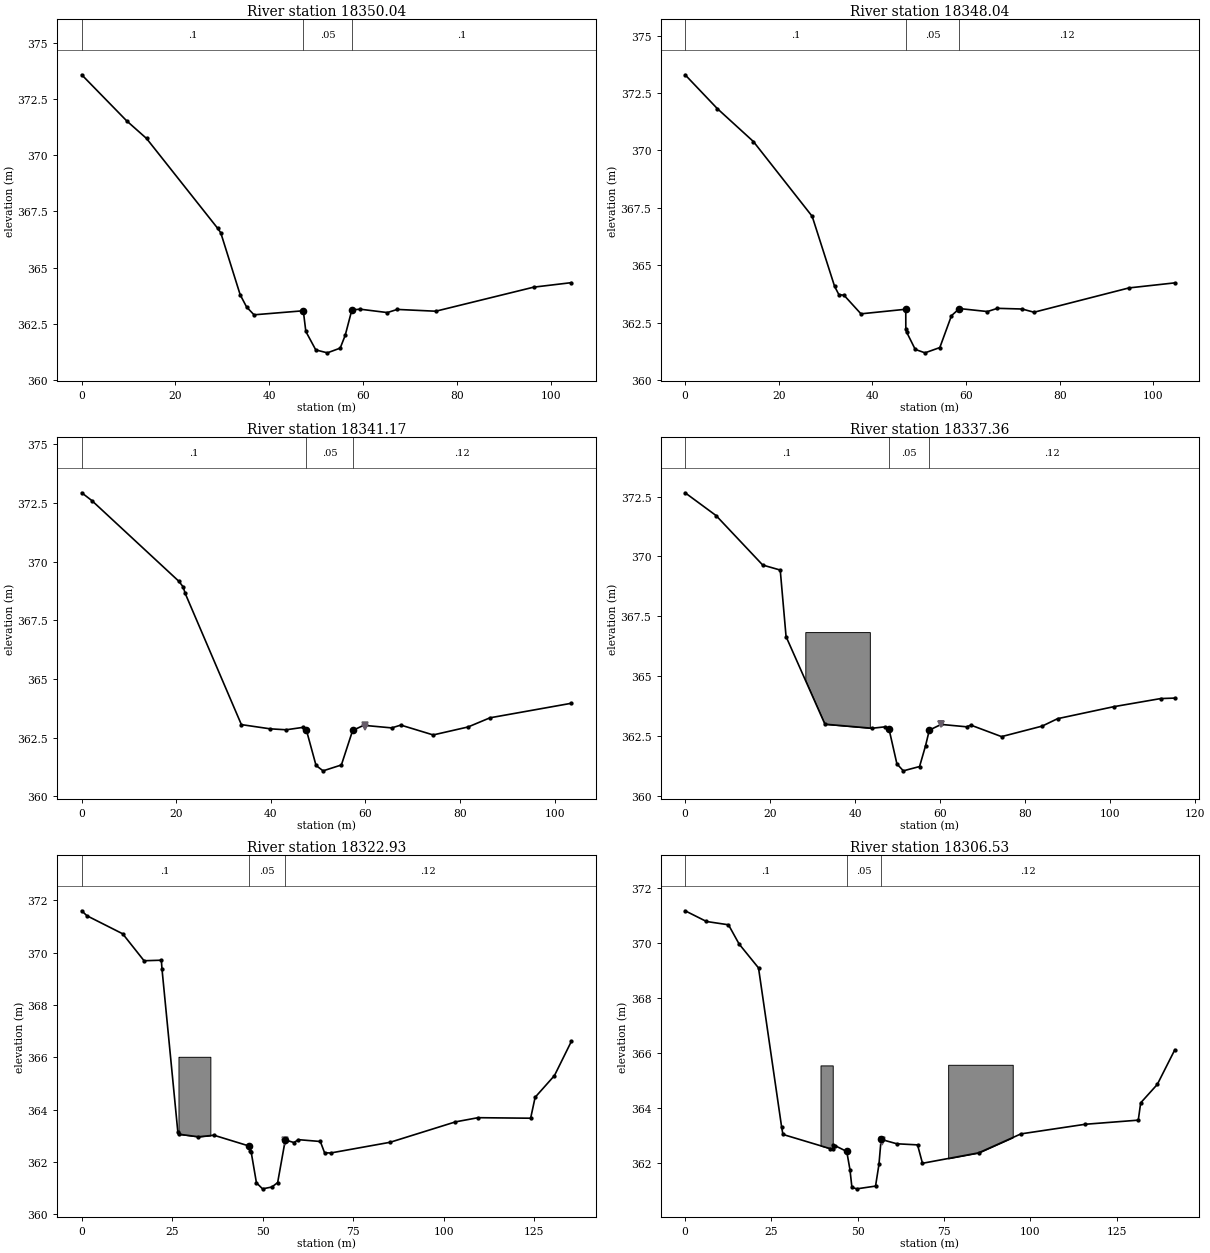
Type RM Length L Ch R = 1 ,18350.04,2,2,2.21
XS GIS Cut Line= 4
    -608978.2241   -1044895.2065    -609008.2817   -1044865.0536
-609022.72899999   -1044851.2234-609048.56549999   -1044818.2857
#Sta/Elev= 22
       0  373.57     9.6  371.52   13.82  370.74   28.98  366.75   29.65  366.55
    33.8  363.79   35.16  363.25   36.75   362.9   47.26  363.08    47.8  362.16
   49.92  361.34   52.39  361.21   55.13  361.42    56.2  361.99   57.62  363.12
   57.71  363.12   59.38  363.15   65.19     363    67.3  363.14   75.51  363.06
   96.41  364.13  104.44  364.33
#Mann= 3 , 0 , 0
       0      .1       0   47.26     .05       0   57.71      .1       0
Bank Sta=47.26,57.71
XS Rating Curve= 0 ,0
Exp/Cntr=0.3,0.1

Type RM Length L Ch R = 1 ,18348.04,7.11,6.87,7.11
XS GIS Cut Line= 4
    -608980.1664   -1044896.0904     -609009.671   -1044866.4922
-609024.11829999    -1044852.662-609051.48649999   -1044819.8097
#Sta/Elev= 22
       0   373.3    6.85  371.83   14.58  370.39   27.13  367.13   31.91  364.08
   32.82  363.72   33.93  363.69   37.54  362.88   47.11  363.08   47.12  362.22
    47.3  362.08   49.13  361.33   51.22  361.18   54.38  361.41   56.87   362.8
   58.56  363.11   64.54  362.98   66.68  363.12   71.95  363.09   74.49  362.95
   94.77  364.01  104.55  364.23
#Mann= 3 , 0 , 0
       0      .1       0   47.11     .05       0   58.56     .12       0
Bank Sta=47.11,58.56
XS Rating Curve= 0 ,0
Exp/Cntr=0.3,0.1

Type RM Length L Ch R = 1 ,18341.17,3.64,3.82,3.48
XS GIS Cut Line= 3
    -608984.7855   -1044901.5539    -609031.6963   -1044854.4518
    -609056.4353   -1044826.8159
#Sta/Elev= 21
       0  372.94    2.13  372.61   20.54  369.17   21.45  368.93   21.89  368.65
   33.77  363.06   39.86  362.88   43.25  362.84   46.71  362.94   47.49  362.85
   49.56  361.32   51.05  361.09   54.92  361.34    57.3  362.81   59.63  363.03
   65.57  362.92   67.49  363.04   74.34  362.62   81.72  362.96   86.35  363.35
  103.57  363.97
#Mann= 3 , 0 , 0
       0      .1       0   47.49     .05       0    57.3     .12       0
Levee=0,,,-1,59.93,362.97,,
Bank Sta=47.49,57.3
XS Rating Curve= 0 ,0
Exp/Cntr=0.3,0.1

Type RM Length L Ch R = 1 ,18337.36,14.84,14.42,14.55
XS GIS Cut Line= 4
     -608988.397   -1044905.6744    -609016.6957   -1044874.6581
-609031.05539999   -1044860.7368-609065.50409999   -1044820.1635
#Sta/Elev= 23
       0  372.66    7.27  371.71   18.26  369.64   22.38  369.43   23.75  366.65
   32.89  362.99   44.01  362.82   47.08  362.88   47.98  362.78   49.83  361.33
   51.34  361.04   55.16  361.22   56.57  362.09   57.45  362.74   60.24  362.98
   66.23  362.88   67.23  362.95   74.45  362.47   84.01  362.91   87.64  363.22
  100.82  363.72  111.88  364.06  115.21  364.08
#Mann= 3 , 0 , 0
       0      .1       0   47.98     .05       0   57.45     .12       0
Levee=0,,,-1,60.21,362.99,,
#Block Obstruct= 1 ,-1
   28.28   43.46366.8377
Bank Sta=47.98,57.45
XS Rating Curve= 0 ,0
Exp/Cntr=0.3,0.1

Type RM Length L Ch R = 1 ,18322.93,16.56,16.4,16.08
XS GIS Cut Line= 2
    -608999.2052   -1044914.5843-609092.44469999   -1044816.5633
#Sta/Elev= 30
       0   371.6    1.44  371.41   11.32  370.72   17.22  369.69      22  369.71
   22.18  369.37   26.56  363.14   26.79  363.06   32.25  362.96   36.52  363.02
   46.17  362.61   46.51  362.42    46.8  362.39   48.27   361.2   49.96  360.97
   52.55  361.04   54.13  361.21   56.24  362.84   58.62  362.74   59.86  362.85
   65.92  362.78   67.09  362.35   68.75  362.34    85.2  362.75  103.25  363.53
   109.5  363.69  124.02  363.67  125.26  364.47   130.6   365.3  135.28  366.61
#Mann= 3 , 0 , 0
       0      .1       0   46.17     .05       0   56.24     .12       0
Levee=0,,,-1,56.26,362.77,,
#Block Obstruct= 1 ,-1
   26.73   35.54366.0181
Bank Sta=46.17,56.24
XS Rating Curve= 0 ,0
Exp/Cntr=0.3,0.1

Type RM Length L Ch R = 1 ,18306.53,11.47,11.55,11.69
XS GIS Cut Line= 3
-609011.42359999   -1044926.7722     -609089.892   -1044841.4859
-609102.89469999   -1044819.0525
#Sta/Elev= 28
       0  371.18    6.19  370.79   12.56  370.67   15.64  369.97   21.26   369.1
   27.95  363.31   28.33  363.04    42.1  362.52   42.75  362.52   42.97  362.64
   43.45  362.63   46.81  362.42   47.74  361.76   48.31  361.11   49.74  361.06
   55.15  361.16   56.14  361.95   56.76  362.86   61.31   362.7   67.32  362.66
   68.74  361.99   85.01  362.37   97.26  363.06  115.89  363.41  131.24  363.56
  131.94  364.19  136.75  364.86  141.82  366.12
#Mann= 3 , 0 , 0
       0      .1       0   46.81     .05       0   56.76     .12       0
Levee=0,,,-1,57,362.77,,
#Block Obstruct= 2 ,-1
   39.21   42.75365.5524   76.18   94.88 365.575
Bank Sta=46.81,56.76
XS Rating Curve= 0 ,0
Exp/Cntr=0.3,0.1

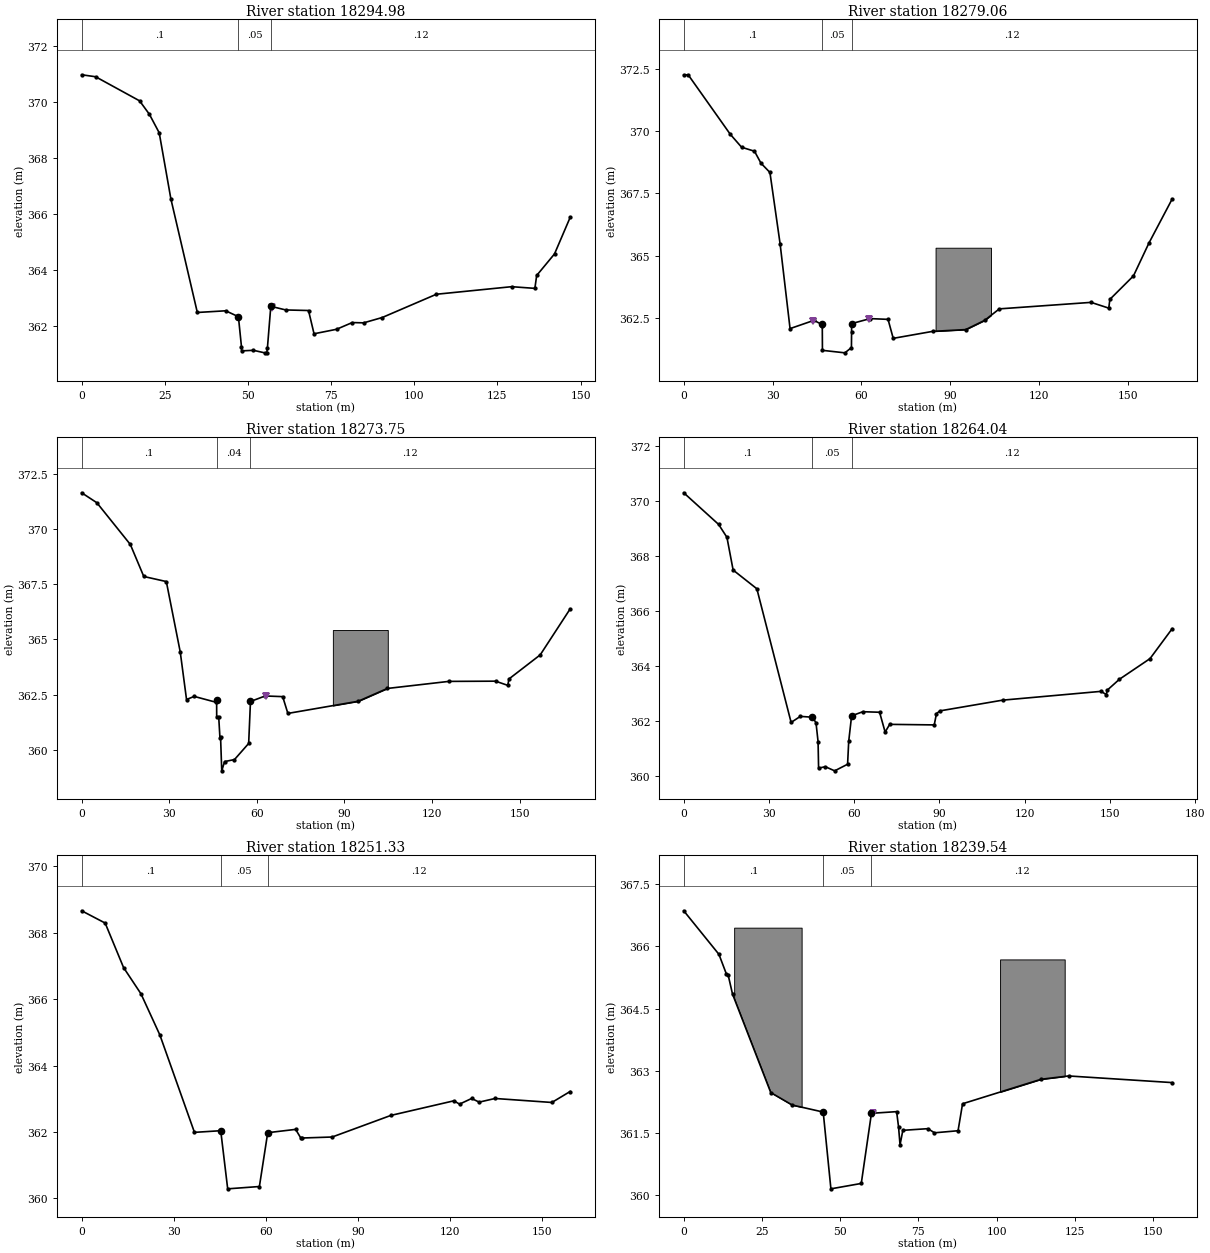
Type RM Length L Ch R = 1 ,18294.98,16.32,15.92,15.19
XS GIS Cut Line= 4
    -609019.4125   -1044934.5905    -609077.4164   -1044872.4435
    -609103.2397   -1044839.8467    -609108.1081   -1044820.1617
#Sta/Elev= 29
       0  370.98    4.19  370.91   17.42  370.05   20.37  369.57   23.32  368.91
   26.83  366.55   34.78   362.5    43.3  362.56   47.13  362.35   48.05  361.28
    48.1  361.13   51.66  361.15   55.02  361.06   55.67  361.07   55.85  361.23
   56.87  362.72   61.37  362.59   68.21  362.57   69.87  361.74   76.63   361.9
   81.35  362.14   84.78  362.13   90.37  362.32  106.65  363.15  129.28  363.42
  136.27  363.36  136.81  363.82  142.18  364.59  146.87  365.89
#Mann= 3 , 0 , 0
       0      .1       0   47.13     .05       0   56.87     .12       0
Levee=0,,,-1,57.37,362.66,,
Bank Sta=47.13,56.87
XS Rating Curve= 0 ,0
Exp/Cntr=0.3,0.1

Type RM Length L Ch R = 1 ,18279.06,5.31,5.32,5.33
XS GIS Cut Line= 5
-609032.27279999   -1044946.5812    -609059.4153   -1044915.6818
     -609083.818   -1044887.4375-609116.26419999   -1044848.5425
-609124.47399999   -1044813.5362
#Sta/Elev= 30
       0  372.24     1.5  372.25   15.72  369.87   19.55  369.35   23.91  369.19
   26.11  368.71   29.13  368.34   32.56  365.49   35.93  362.09   43.99  362.42
   46.63  362.26   46.82   362.2   46.87  361.22   54.47  361.12   56.67  361.33
   56.72  361.94   56.73  362.29   62.98  362.49   69.04  362.46   70.79   361.7
   84.14  361.98   95.28  362.05  101.69  362.42  106.65  362.88  137.65  363.14
  143.62  362.91     144  363.26  151.97   364.2  157.22  365.52  165.06  367.28
#Mann= 3 , 0 , 0
       0      .1       0   46.63     .05       0   56.73     .12       0
Levee=-1,43.75,362.38,-1,62.46,362.46,,
#Block Obstruct= 1 ,-1
    85.1  103.82365.3277
Bank Sta=46.63,56.73
XS Rating Curve= 0 ,0
Exp/Cntr=0.3,0.1

Type RM Length L Ch R = 1 ,18273.75,10.28,9.7,8.84
XS GIS Cut Line= 5
    -609036.4443   -1044949.8598-609064.65399999   -1044917.7456
-609089.05669999   -1044889.5013-609120.98169999   -1044852.9628
    -609132.1506   -1044815.9045
#Sta/Elev= 30
       0  371.64     5.2  371.19   16.67   369.3   21.28  367.85      29  367.62
   33.77  364.43   35.92  362.28   38.55  362.42   45.88  362.16   46.23  362.26
   46.25  361.49   46.94   361.5   47.36  360.55   47.57   360.6   47.98  359.05
   48.96  359.47   52.34  359.56    57.2  360.29   57.82  362.19   62.85  362.44
   68.85  362.41   70.63  361.65   94.71   362.2  104.69  362.78  125.75   363.1
  141.77  363.11  145.94  362.92  146.35  363.21  157.05   364.3   167.3  366.38
#Mann= 3 , 0 , 0
       0      .1       0   46.23     .04       0   57.82     .12       0
Levee=0,,,-1,63.29,362.42,,
#Block Obstruct= 1 ,-1
   86.04  104.85365.4245
Bank Sta=46.23,57.82
XS Rating Curve= 0 ,0
Exp/Cntr=0.3,0.1

Type RM Length L Ch R = 1 ,18264.04,12.48,12.71,12.7
XS GIS Cut Line= 5
    -609043.6799   -1044956.0504    -609072.4114   -1044924.5346
-609084.51969999   -1044908.6165    -609125.8273   -1044857.4816
-609142.94559999   -1044817.4285
#Sta/Elev= 30
       0  370.31   12.28  369.16   15.21  368.69   17.39   367.5   25.74  366.82
    37.8  361.96   41.05  362.18   45.27  362.15   46.56  361.95   47.29  361.26
   47.47   360.3   49.85  360.35   53.13   360.2   57.68  360.44   58.07  361.27
   59.09   362.2   63.06  362.35   68.94  362.33   70.89  361.61    72.5  361.89
   88.18  361.87   88.96  362.28   90.18  362.38  112.24  362.77  146.92  363.09
  148.75  362.97  149.04  363.13  153.37  363.53  164.13  364.28  171.94  365.37
#Mann= 3 , 0 , 0
       0      .1       0   45.27     .05       0   59.09     .12       0
Bank Sta=45.27,59.09
XS Rating Curve= 0 ,0
Exp/Cntr=0.3,0.1

Type RM Length L Ch R = 1 ,18251.33,11.82,11.79,11.94
XS GIS Cut Line= 3
    -609055.0687   -1044965.2886    -609095.5801   -1044915.7116
    -609148.4968   -1044836.6673
#Sta/Elev= 22
       0  368.66    7.66  368.29   13.66  366.95   19.33  366.16   25.49  364.92
   36.75  361.99   45.31  362.04   47.58  360.29   57.91  360.36   60.62  361.98
   69.72  362.08   71.33  361.83   71.83  361.82   81.62  361.85  100.74   362.5
  121.28  362.94  123.12  362.84  127.06  363.01  129.52   362.9  134.68  363.01
   153.2  362.89  159.15  363.22
#Mann= 3 , 0 , 0
       0      .1       0   45.31     .05       0   60.62     .12       0
Bank Sta=45.31,60.62
XS Rating Curve= 0 ,0
Exp/Cntr=0.3,0.1

Type RM Length L Ch R = 1 ,18239.54,14.41,15.04,15.89
XS GIS Cut Line= 3
    -609064.9836   -1044971.8533    -609104.8405   -1044922.9878
-609156.10359999   -1044845.2663
#Sta/Elev= 22
       0  366.86   11.26  365.81   13.62  365.34   14.21  365.31   15.61  364.85
   27.82  362.48   34.65  362.18   44.59  362.01   47.05  360.16   56.76  360.29
   60.01  361.98   68.06  362.02   68.68  361.65   69.15  361.22   70.05  361.57
   78.08  361.61   80.15  361.51    87.7  361.56   89.14  362.21  114.25   362.8
  123.01  362.88  156.16  362.72
#Mann= 3 , 0 , 0
       0      .1       0   44.59     .05       0   60.01     .12       0
Levee=0,,,-1,60.6,361.97,,
#Block Obstruct= 2 ,-1
   16.12   37.69366.4533  101.13  121.79365.6882
Bank Sta=44.59,60.01
XS Rating Curve= 0 ,0
Exp/Cntr=0.3,0.1

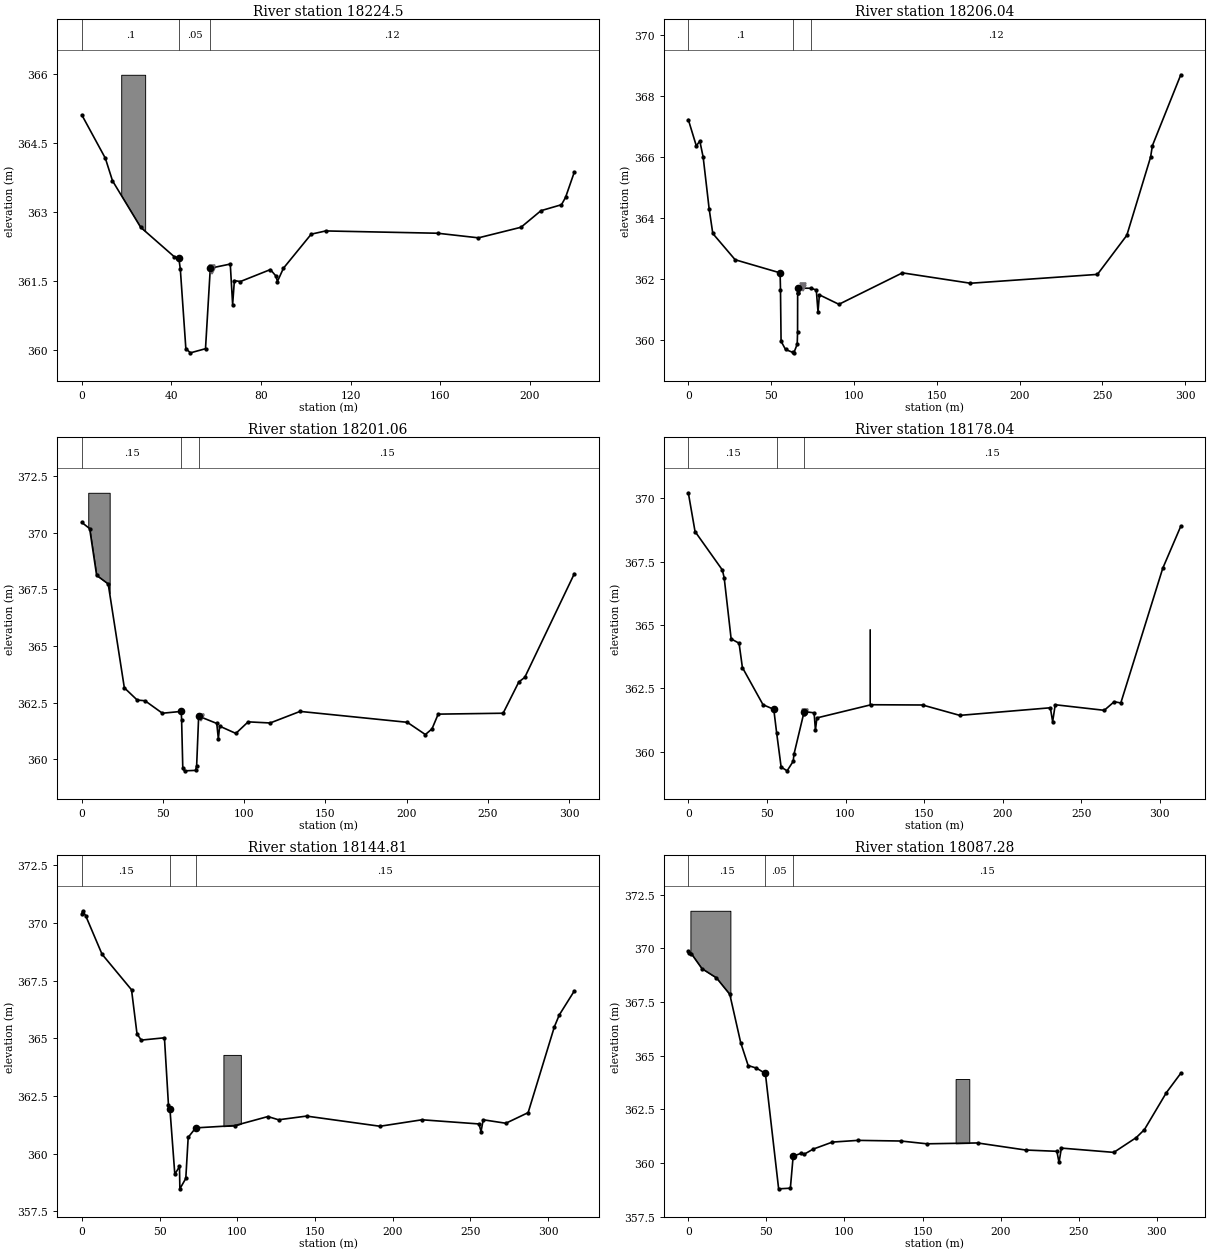
Type RM Length L Ch R = 1 ,18224.5 ,18.07,18.46,18.77
XS GIS Cut Line= 3
    -609075.6612   -1044979.0075    -609117.0775    -1044932.579
-609210.79199999   -1044805.8233
#Sta/Elev= 28
       0  365.11   10.49  364.17   13.68  363.68   26.24  362.67   41.24  362.03
   43.28     362   43.96  361.76   46.43  360.03   48.49  359.94    55.2  360.03
   57.34  361.78   66.26  361.87   67.31  360.99   68.09  361.51   70.76  361.49
   84.16  361.75   86.64  361.61    87.3  361.49      90  361.78   102.4  362.52
  108.88  362.59  158.83  362.54  177.06  362.44  196.05  362.67  204.95  363.03
  214.11  363.16  215.94  363.32  219.85  363.87
#Mann= 3 , 0 , 0
       0      .1       0   43.28     .05       0   57.34     .12       0
Levee=0,,,-1,58.17,361.72,,
#Block Obstruct= 1 ,-1
   17.57   28.26365.9847
Bank Sta=43.28,57.34
XS Rating Curve= 0 ,0
Exp/Cntr=0.3,0.1

Type RM Length L Ch R = 1 ,18206.04,5.09,4.98,4.99
XS GIS Cut Line= 4
     -609080.951    -1044998.105    -609116.2027    -1044960.872
    -609129.9171   -1044946.3148-609272.49179999   -1044770.8857
#Sta/Elev= 30
       0  367.22    4.83  366.36    6.94  366.52    8.97  365.99   12.57   364.3
   14.78  363.49   28.27  362.63   55.41   362.2   55.65  361.65      56  359.96
    58.7  359.69   63.24359.5912   63.69  359.58   65.74  359.86   65.96  360.26
   66.01  361.53   66.11  361.55   66.12   361.7      74 361.696   77.27  361.64
    78.3  360.92   79.13  361.48   90.93  361.17  129.25   362.2  170.35  361.86
     247  362.15  264.74  363.43  279.08  365.99   280.2  366.37  297.33  368.69
#Mann= 3 ,-1 , 0
       0      .1       0   63.24     .05       0      74     .12       0
Levee=0,,,-1,69.11,361.76,,
Bank Sta=55.41,66.12
XS Rating Curve= 0 ,0
Exp/Cntr=0.3,0.1

Type RM Length L Ch R = 1 ,18201.06,23.86,23.02,22.09
XS GIS Cut Line= 4
     -609081.967   -1045006.5717-609120.09479999    -1044964.001
    -609133.8092   -1044949.4436    -609276.3839   -1044774.0146
#Sta/Elev= 30
       0  370.45     4.8  370.18    9.09  368.12   16.22  367.74   26.16  363.16
    34.1  362.62   38.88  362.59   49.59  362.04   61.21  362.12   61.43  361.72
   62.15  359.61   63.21   359.5   70.02  359.52   70.68  359.73   71.92  361.91
   83.07  361.59   84.04  360.91   84.84  361.47   94.82  361.15  102.39  361.66
  115.93  361.61  134.35  362.12  200.36  361.64   211.5   361.1  215.58  361.35
  219.39     362  259.37  362.04  269.05  363.42  272.69  363.62  303.21  368.19
#Mann= 3 , 0 , 0
       0     .15       0   61.21     .05       0   71.92     .15       0
Levee=0,,,-1,73.15,361.83,,
#Block Obstruct= 1 ,-1
    3.93   17.13371.7588
Bank Sta=61.21,71.92
XS Rating Curve= 0 ,0
Exp/Cntr=0.3,0.1

Type RM Length L Ch R = 1 ,18178.04,32.9,33.23,33.2
XS GIS Cut Line= 4
    -609103.6508   -1045021.0811-609138.55079999   -1044978.8772
    -609151.1605   -1044963.3531    -609291.7859   -1044770.6855
#Sta/Elev= 30
       0  370.22    4.28  368.69   21.67  367.17   22.82  366.86   27.24  364.45
   32.28  364.28    34.4  363.32   47.53  361.85   54.36  361.67   56.22360.7247
   59.04  359.39   62.85  359.24   66.74  359.62   67.19  359.89   73.29 361.474
   73.82  361.58   80.03  361.53   80.86  360.85   81.81  361.33  116.27  361.85
  148.98  361.84   172.7  361.43   230.3  361.73  231.77  361.18  233.41  361.85
   264.6  361.63  270.94  361.97  275.13  361.92  301.82  367.24  313.29   368.9
#Mann= 3 ,-1 , 0
       0     .15       0   56.22     .05       0   73.29     .15       0
Levee=0,,,-1,73.96,361.53,,
#Block Obstruct= 1 ,-1
  115.17  115.55 364.834
Bank Sta=54.36,73.82
XS Rating Curve= 0 ,0
Exp/Cntr=0.3,0.1

Type RM Length L Ch R = 1 ,18144.81,57.17,57.54,57.11
XS GIS Cut Line= 3
    -609126.6578   -1045045.0457    -609180.4545    -1044979.726
-609309.43919999   -1044786.5799
#Sta/Elev= 30
       0   370.4     .58  370.52     2.5   370.3   12.98  368.64   31.96   367.1
   35.49  365.19   38.21  364.92   53.14  365.02   55.75  362.09   56.66  361.95
   59.82  359.11   62.82  359.45   63.07  358.48   66.88  358.93   68.42  360.71
   73.26  361.12   98.47  361.22  119.71  361.61  126.56  361.47  144.56  361.63
  191.84  361.19  218.85  361.47  255.53  361.29  256.86  360.96  258.24  361.47
  272.83  361.32  287.16  361.78  304.06   365.5   307.2  366.01  316.88  367.05
#Mann= 3 , 0 , 0
       0     .15       0   56.66     .05       0   73.26     .15       0
#Block Obstruct= 1 ,-1
   91.09   102.3364.2794
Bank Sta=56.66,73.26
XS Rating Curve= 0 ,0
Exp/Cntr=0.3,0.1

Type RM Length L Ch R = 1 ,18087.28,17.9,17.24,16.41
XS GIS Cut Line= 4
    -609172.6953   -1045075.7374-609210.22019999   -1045033.9658
    -609225.4338   -1045014.7835-609349.78819999   -1044815.6841
#Sta/Elev= 30
       0  369.87     .34  369.79     1.9  369.76    8.72  369.06   17.99  368.63
   26.56  367.86   33.53  365.61   38.32  364.54   43.62  364.42   49.35  364.17
   57.84  358.79   65.35  358.82   67.14  360.31   71.92  360.44   74.13   360.4
   79.88  360.64   92.26  360.97  108.58  361.05  136.13  361.02  152.81  360.89
   185.2  360.93  215.99   360.6  236.03  360.54   237.4  360.02  238.91  360.69
  272.48  360.49  286.86  361.18  292.07  361.55  306.19  363.28  315.38  364.18
#Mann= 3 , 0 , 0
       0     .15       0   49.35     .05       0   67.14     .15       0
#Block Obstruct= 2 ,-1
    1.34   26.94371.7567  171.18  179.93363.9105
Bank Sta=49.35,67.14
XS Rating Curve= 0 ,0
Exp/Cntr=0.3,0.1

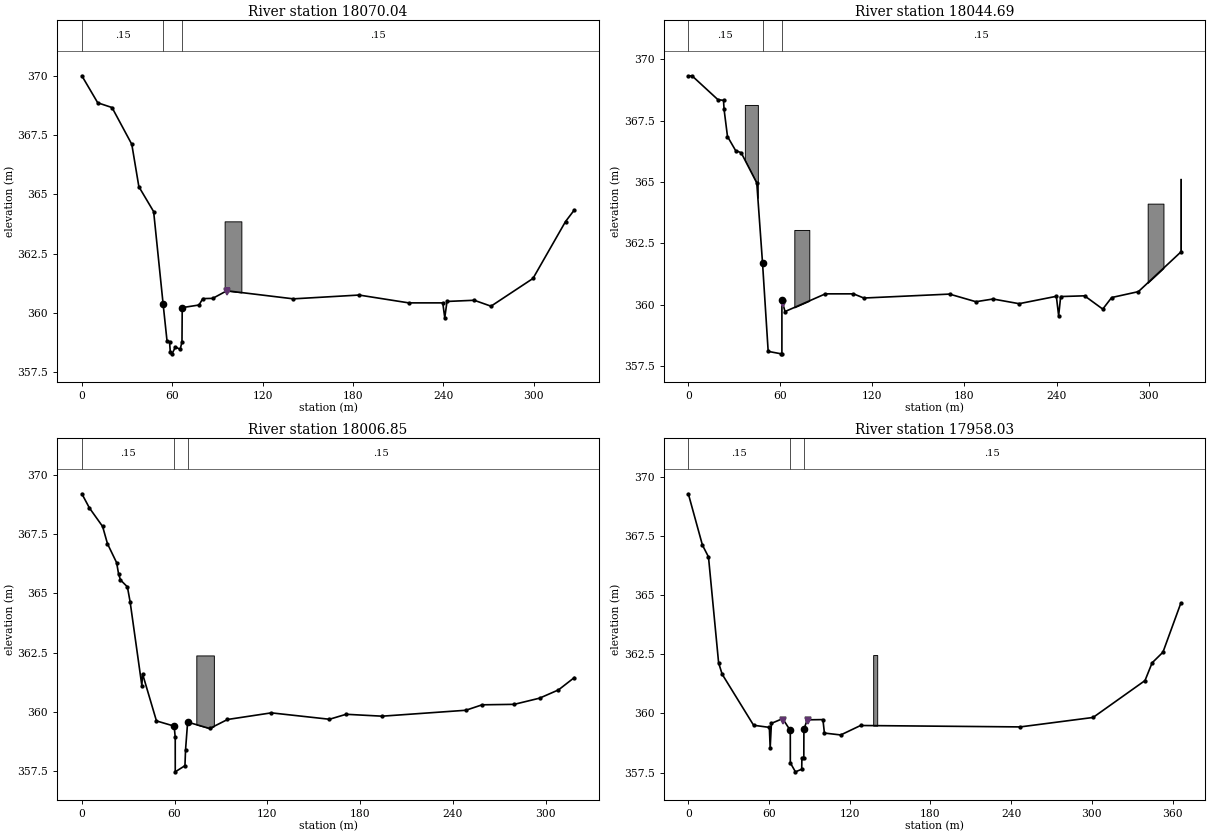
Type RM Length L Ch R = 1 ,18070.04,26.03,25.34,24.56
XS GIS Cut Line= 4
    -609188.4695   -1045088.7556-609221.08839999   -1045048.4074
    -609233.1209    -1045032.432    -609365.3255   -1044814.4483
#Sta/Elev= 30
       0     370   10.54  368.86   20.03  368.66   33.14  367.11   37.84  365.32
   47.64  364.27    53.9360.3909   56.53  358.81   58.19  358.78    58.7  358.34
   59.86  358.27   62.11  358.56   65.23  358.46   66.45  358.77   66.61  360.22
   77.76  360.33   80.25   360.6   86.85  360.61   96.19  360.93  140.38  360.59
  183.97  360.75  216.94  360.42  239.52  360.42  240.85  359.79  242.33  360.48
  260.41  360.53  271.53  360.28  299.39  361.45  320.98  363.85  326.83  364.34
#Mann= 3 ,-1 , 0
       0     .15       0    53.9     .05       0   66.61     .15       0
Levee=0,,,-1,96.59,360.86,,
#Block Obstruct= 1 ,-1
   94.75  105.86363.8593
Bank Sta=53.9,66.61
XS Rating Curve= 0 ,0
Exp/Cntr=0.3,0.1

Type RM Length L Ch R = 1 ,18044.69,39.68,37.85,34.98
XS GIS Cut Line= 4
    -609211.3246   -1045101.1375    -609241.9703   -1045063.7315
    -609258.5068   -1045037.9345    -609384.8456   -1044831.5591
#Sta/Elev= 30
       0  369.31    2.39  369.32   19.27  368.35   22.94  368.32   23.29  367.96
   25.53  366.85   30.81  366.28   34.45  366.19   44.62  364.96   48.36  361.71
   52.05  358.11   60.57  358.01   60.99  358.01      61  360.18   63.04  359.73
   89.32  360.45  107.65  360.45   114.4  360.28  170.26  360.44  187.43  360.13
  198.58  360.24  215.58  360.05  239.86  360.35  241.36  359.56  242.68  360.34
  258.25  360.37  270.11  359.83  275.91   360.3  293.32  360.54  320.97  362.15
#Mann= 3 , 0 , 0
       0     .15       0   48.36     .05       0      61     .15       0
Levee=0,,,-1,61.43,360.05,,
#Block Obstruct= 4 ,-1
   69.09   78.84363.0494   36.85   45.32 368.134  320.66  320.97365.1357
  299.39  309.67364.1195
Bank Sta=48.36,61
XS Rating Curve= 0 ,0
Exp/Cntr=0.3,0.1

Type RM Length L Ch R = 1 ,18006.85,47.57,48.82,45.88
XS GIS Cut Line= 4
-609249.95389999   -1045127.0667-609280.33489999   -1045075.6377
    -609281.6579   -1045067.0388    -609407.3352   -1044850.7415
#Sta/Elev= 30
       0  369.21    4.91  368.61   13.43  367.83   16.58   367.1    22.5   366.3
   23.75  365.83      25  365.57   29.46  365.28   31.22  364.65   38.82  361.11
   39.25  361.61   48.26  359.62   59.73   359.4   60.41  358.92   60.42  357.47
    66.7  357.73   67.07  358.39   68.43  359.57   82.73   359.3   94.22  359.68
  122.56  359.96  160.18  359.69  170.96   359.9  194.24  359.82  248.41  360.07
  258.94   360.3  279.72  360.32  296.07  360.58  308.35  360.93  318.59  361.45
#Mann= 3 , 0 , 0
       0     .15       0   59.73     .05       0   68.43     .15       0
#Block Obstruct= 1 ,-1
   74.05    85.4362.3846
Bank Sta=59.73,68.43
XS Rating Curve= 0 ,0
Exp/Cntr=0.3,0.1

Type RM Length L Ch R = 1 ,17958.03,4.98,4.96,5.01
XS GIS Cut Line= 5
-609289.07889999   -1045149.6626    -609326.2672   -1045090.5068
    -609331.3531   -1045071.1643-609362.16739999   -1045001.6811
     -609463.228   -1044828.8855
#Sta/Elev= 30
       0  369.29   10.49  367.12   14.99  366.62   22.52  362.14   25.14  361.66
   48.53   359.5   60.23  359.41   60.84  358.54   61.76  359.58   70.13  359.78
   75.55 359.302    75.8   359.3   75.82  357.91   79.63  357.53    84.3  357.64
   84.42  358.13   85.85  358.13   85.91  359.33   86.02359.3391   88.33  359.73
  100.05  359.74  101.16  359.17  113.29  359.09  128.04  359.49  246.69  359.43
  300.86  359.83  339.45  361.39  344.75  362.14  352.79  362.59  366.06  364.66
#Mann= 3 ,-1 , 0
       0     .15       0   75.55     .04       0   86.02     .15       0
Levee=-1,70.67,359.7,-1,88.68,359.7,,
#Block Obstruct= 1 ,-1
   137.4   140.4362.4691
Bank Sta=75.55,86.02
XS Rating Curve= 0 ,0
Exp/Cntr=0.3,0.1