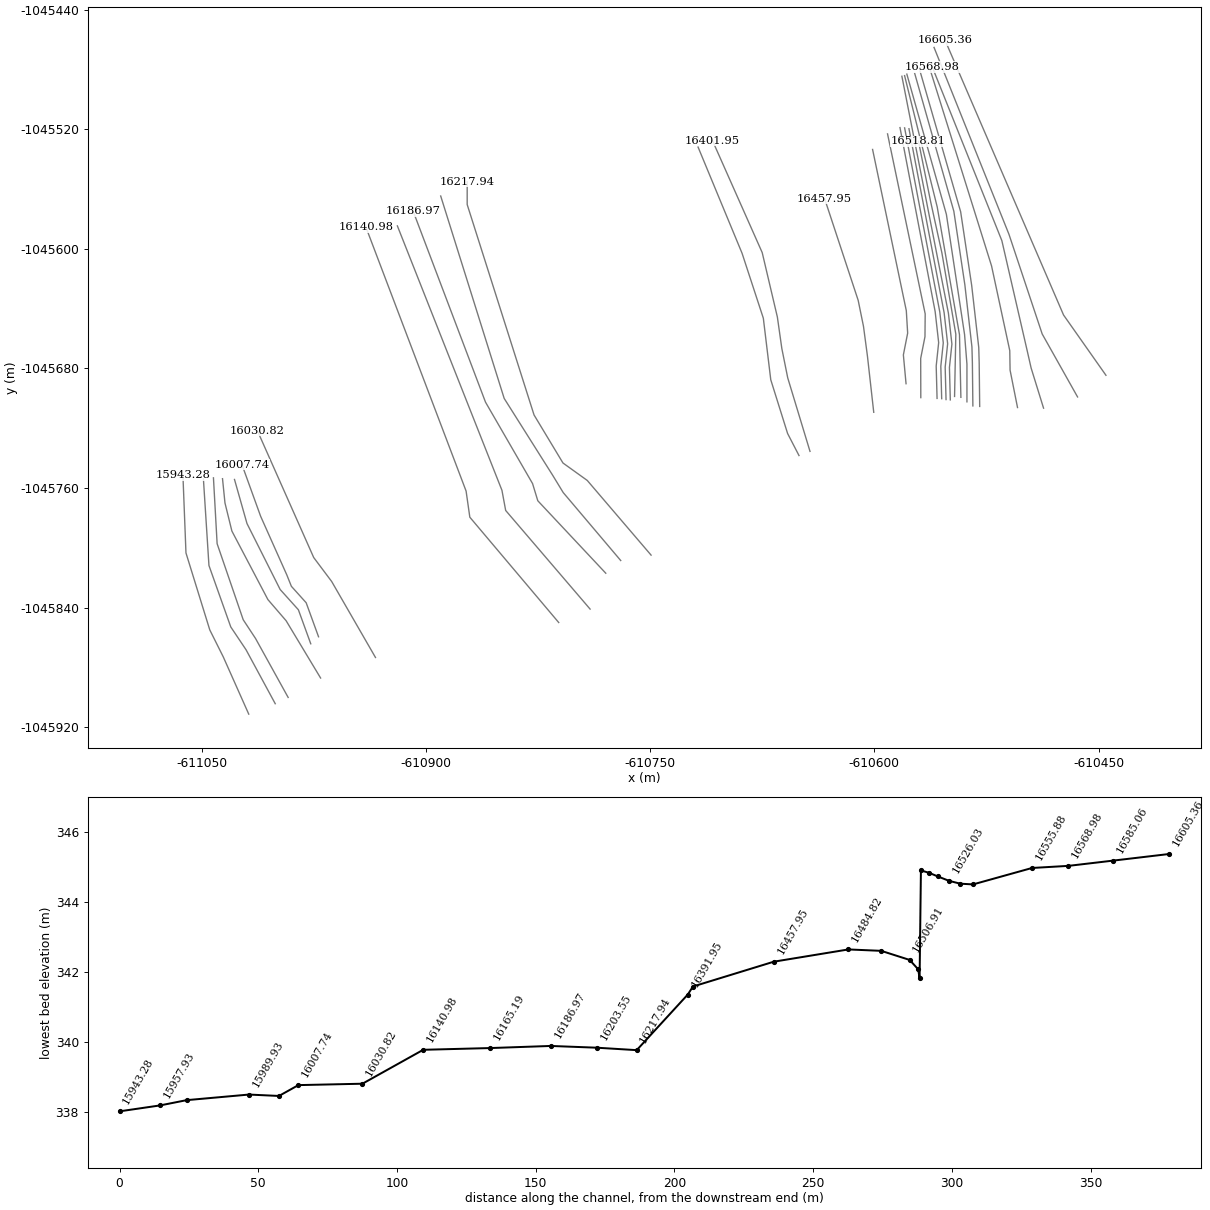
HEC-RAS study PPO_Kvasiny_efektiv.prj: PPO_Kvasiny_efektivita

--- PPO_Kvasiny_efektiv.g07 (geometry) --- (continued)

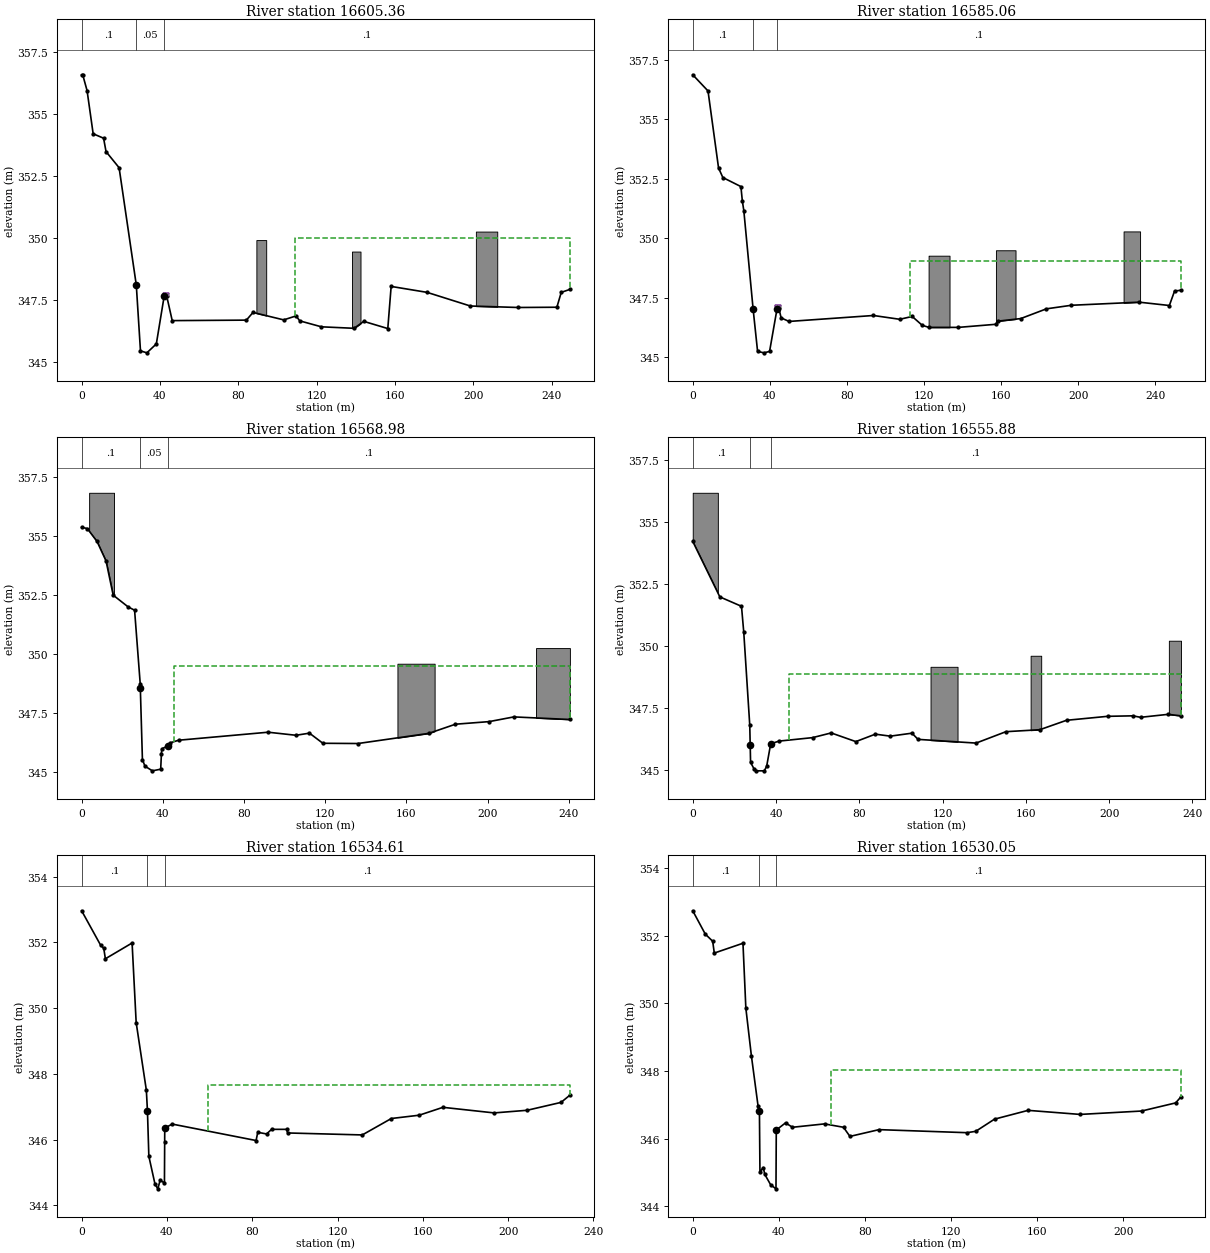
Type RM Length L Ch R = 1 ,16605.36,21.02,20.3,16.27
XS GIS Cut Line= 3
-610445.09629999   -1045684.5852-610473.44709999   -1045644.2738
-610552.67139999    -1045460.529
#Sta/Elev= 30
       0  356.58     .55  356.59    2.78  355.95    5.88  354.21   11.21  354.03
   12.46  353.49   19.13  352.84   27.91  348.11   30.05  345.45   33.32  345.37
   38.15  345.73   42.18  347.67   43.48  347.65   46.26  346.67   84.14  346.69
   87.53     347  103.21   346.7  109.51  346.86  111.41  346.66  122.47  346.42
  139.16  346.36   144.1  346.64  156.37  346.35  158.08  348.05  176.45  347.81
  198.52  347.26  222.94   347.2  242.73  347.21  244.96  347.81  249.38  347.93
#Mann= 3 , 0 , 0
       0      .1       0   27.91     .05       0   42.18      .1       0
Levee=0,,,-1,42.87,347.61,,
#XS Ineff= 2 , 0
                          108.98          349.99
Permanent Ineff=
       F       F
#Block Obstruct= 3 ,-1
  138.07  142.43349.4565   89.25   94.26349.9202  201.36  212.27350.2634
Bank Sta=27.91,42.18
XS Rating Curve= 0 ,0
Exp/Cntr=0.3,0.1

Type RM Length L Ch R = 1 ,16585.06,17.86,16.08,10.48
XS GIS Cut Line= 4
    -610464.0819   -1045699.0756    -610487.7346   -1045656.9739
    -610509.9596   -1045590.2987    -610560.0797   -1045465.2915
#Sta/Elev= 30
       0  356.87    7.92  356.19   13.39  352.95   15.62  352.55   24.98  352.17
   25.73  351.56   26.49  351.16    31.3  347.03   33.63  345.24   36.97  345.18
   39.85  345.24   43.72  347.03   44.65  347.06   45.84  346.65   49.93   346.5
   93.75  346.75  107.37  346.59  113.82  346.71  118.99  346.34  122.48  346.25
  137.76  346.25  157.18  346.38  158.11  346.51  170.11  346.62  183.44  347.03
  196.43  347.18  231.58  347.31  247.21  347.17  249.92  347.78  253.25  347.81
#Mann= 3 , 0 , 0
       0      .1       0    31.3     .05       0   43.72      .1       0
Levee=0,,,-1,44.45,347.03,,
#XS Ineff= 2 , 0
                          112.59          349.04
Permanent Ineff=
       F       F
#Block Obstruct= 3 ,-1
  122.33  133.19349.2643  157.26  167.42349.4925  223.47  232.02350.2849
Bank Sta=31.3,43.72
XS Rating Curve= 0 ,0
Exp/Cntr=0.3,0.1

Type RM Length L Ch R = 1 ,16568.98,14.3,13.1,11.02
XS GIS Cut Line= 5
    -610486.8255   -1045706.5634-610495.14299999   -1045679.7281
    -610497.7888   -1045668.0863    -610514.7221    -1045594.532
    -610561.2439   -1045478.4149
#Sta/Elev= 28
       0  355.37    2.76  355.32    7.58  354.77   12.03  353.94   15.54  352.49
   22.92  351.99   26.09  351.85   28.89   348.7   28.92  348.54   29.95  345.51
   31.19  345.23   34.85  345.03   38.95   345.1   39.31  345.75   39.49  345.96
   42.33  346.09   43.66  346.22   47.79  346.33   91.89  346.67  105.62  346.54
  112.26  346.63  118.88   346.2  136.17  346.19     171  346.62  184.22  347.01
  200.78  347.12  212.99  347.32   240.6  347.21
#Mann= 3 , 0 , 0
       0      .1       0   28.92     .05       0   42.33      .1       0
#XS Ineff= 2 , 0
                           45.47          349.48
Permanent Ineff=
       F       F
#Block Obstruct= 3 ,-1
    3.69   15.95356.8368  155.62  173.94 349.579  223.92   240.6350.2427
Bank Sta=28.92,42.33
XS Rating Curve= 0 ,0
Exp/Cntr=0.3,0.1

Type RM Length L Ch R = 1 ,16555.88,20.77,21.27,17.9
XS GIS Cut Line= 5
    -610504.2404   -1045706.1507    -610509.2146    -1045681.174
    -610509.4305   -1045668.0863-610521.60139999   -1045611.4654
    -610562.8314   -1045479.6849
#Sta/Elev= 29
       0  354.23   13.02  351.99   23.42  351.61   24.51  350.56   27.39  346.81
    27.6  346.01   27.78  345.31   29.57  345.03   30.58  344.97   34.36  344.97
    35.5  345.15   37.44  346.06   41.43  346.17   57.54  346.31    66.5   346.5
   78.34  346.15   87.71  346.45    94.9  346.37   105.3  346.49  108.23  346.24
  136.11  346.09  150.44  346.55  166.72  346.63  179.56  347.01  199.26  347.17
  211.42  347.19  215.11  347.13  228.36  347.25  234.55  347.19
#Mann= 3 , 0 , 0
       0      .1       0    27.6     .05       0   37.44      .1       0
#XS Ineff= 2 , 0
                           46.19          348.89
Permanent Ineff=
       F       F
#Block Obstruct= 4 ,-1
       0   12.06356.1919  114.23   127.2349.1687  162.31  167.39349.6144
  228.72  234.55350.2217
Bank Sta=27.6,37.44
XS Rating Curve= 0 ,0
Exp/Cntr=0.3,0.1

Type RM Length L Ch R = 1 ,16534.61,4.61,4.56,4.51
XS GIS Cut Line= 6
-610529.54529999   -1045705.4184    -610529.8783    -1045676.323
-610530.17399999   -1045665.9981-610534.91189999   -1045624.3717
-610542.27789999   -1045575.2226-610569.46539999   -1045481.1129
#Sta/Elev= 30
       0  352.96    8.93  351.91   10.36  351.82   11.14   351.5   23.66  351.98
   25.57  349.56   30.35   347.5   30.86  346.87   31.52  345.49   34.38  344.65
   35.72   344.5    36.8  344.76   38.83  344.68   38.94  345.92   38.97  346.35
   42.49  346.47   81.81  345.97    82.6  346.22   86.73  346.17   89.08  346.31
    96.1  346.31   96.62   346.2  131.61  346.14  145.25  346.64  158.29  346.74
  169.44  346.98  193.45  346.81   208.9  346.89  224.82  347.13  228.98  347.35
#Mann= 3 , 0 , 0
       0      .1       0   30.86     .04       0   38.97      .1       0
#XS Ineff= 2 , 0
                           59.32          347.66
Permanent Ineff=
       F       F
Bank Sta=30.86,38.97
XS Rating Curve= 0 ,0
Exp/Cntr=0.5,0.3

Type RM Length L Ch R = 1 ,16530.05,3.73,4.02,4.32
XS GIS Cut Line= 6
    -610534.1055   -1045705.0639-610534.43849999   -1045675.9685
    -610534.7342   -1045665.6436    -610539.4721   -1045624.0172
    -610546.8381   -1045574.8681    -610573.0214   -1045482.6369
#Sta/Elev= 30
       0  352.74    5.83  352.05    9.26  351.84   10.02  351.49   23.34  351.78
   24.68  349.86   27.24  348.46   30.35  346.97   30.99  346.81   31.23  345.02
   32.79  345.15   33.46  344.95    36.2  344.64   38.68  344.52   38.82  346.25
   38.85  346.26   43.12  346.47   46.35  346.34   61.25  346.44   70.06  346.34
   73.04  346.07   86.57  346.27  127.43  346.18   131.5  346.22  140.23  346.58
  155.85  346.84  180.01  346.72  208.55  346.82  224.39  347.06   226.9  347.24
#Mann= 3 , 0 , 0
       0      .1       0   30.99     .04       0   38.85      .1       0
#XS Ineff= 2 , 0
                           64.23          348.04
Permanent Ineff=
       F       F
Bank Sta=30.99,38.85
XS Rating Curve= 0 ,0
Exp/Cntr=0.5,0.3

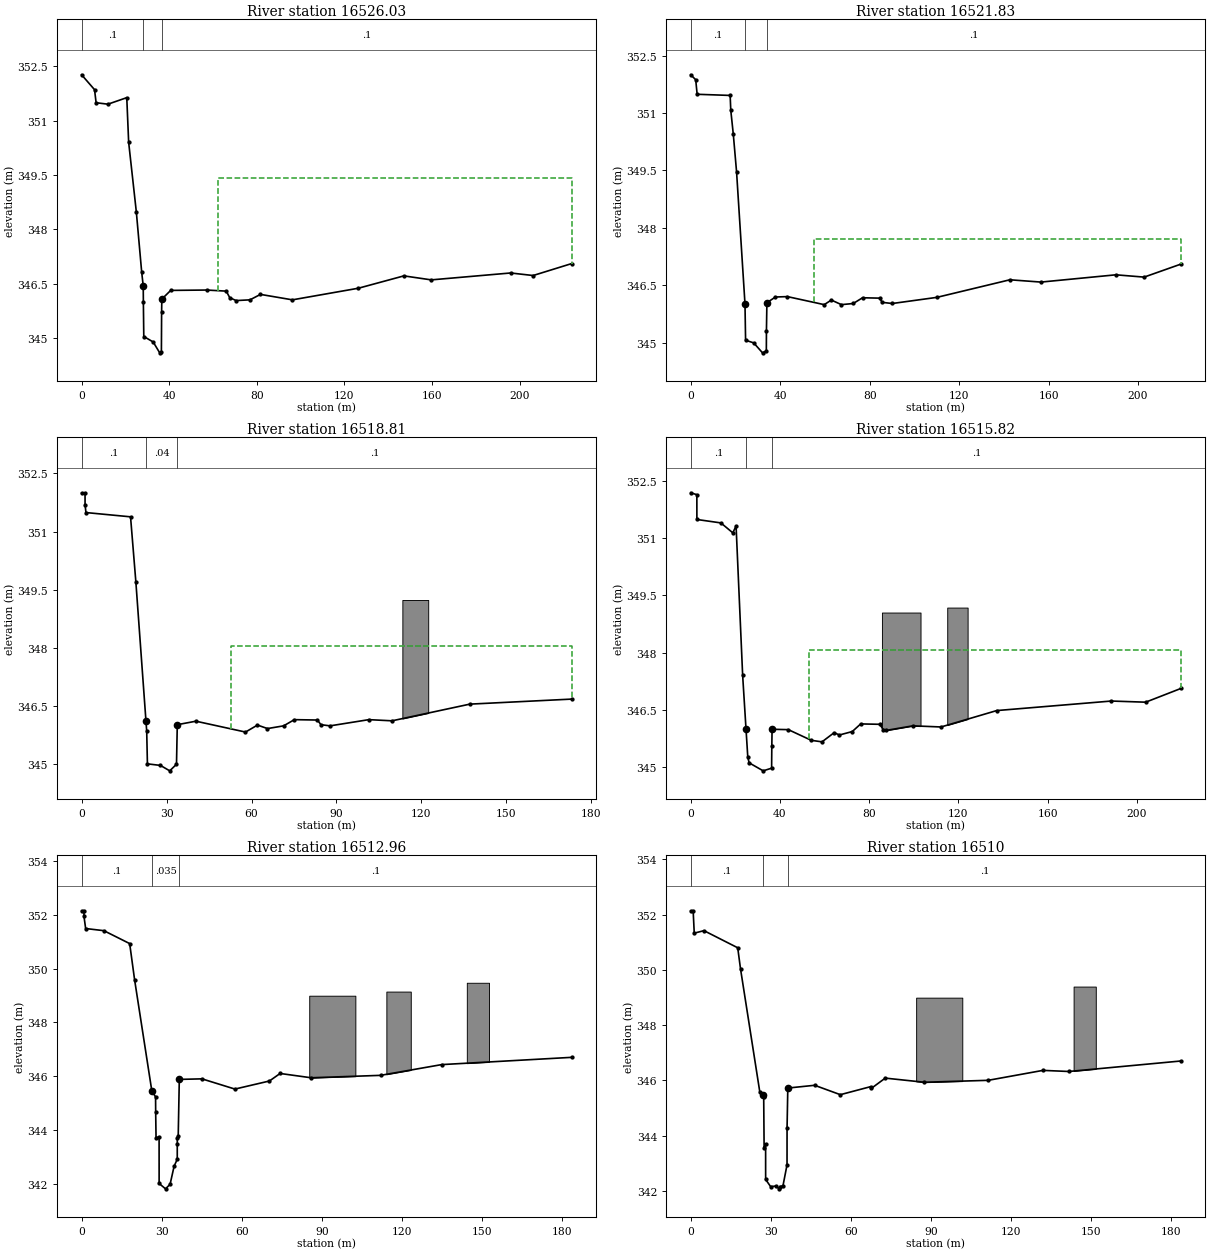
Type RM Length L Ch R = 1 ,16526.03,4.58,4.2,3.62
XS GIS Cut Line= 5
    -610538.0693   -1045702.3362-610538.07229999    -1045677.112
    -610539.6568   -1045657.3569-610551.82759999   -1045576.9234
    -610578.2707   -1045483.1449
#Sta/Elev= 30
       0  352.26     5.9  351.85    6.62  351.49   12.02  351.45   20.62  351.63
   21.48   350.4   24.99  348.48   27.42  346.83   28.14  346.44    28.2     346
   28.39  345.05   32.67   344.9   35.66   344.6   36.43  344.62   36.53  345.72
   36.63  346.08   40.68  346.32   57.07  346.33   66.05   346.3   67.64  346.12
   70.55  346.04   76.88  346.06   81.67  346.21   96.26  346.06  126.39  346.38
  147.15  346.72  159.66  346.61   195.9   346.8  206.17  346.73  223.83  347.06
#Mann= 3 , 0 , 0
       0      .1       0   28.14     .04       0   36.63      .1       0
#XS Ineff= 2 , 0
                           62.36          349.41
Permanent Ineff=
       F       F
Bank Sta=28.14,36.63
XS Rating Curve= 0 ,0
Exp/Cntr=0.3,0.1

Type RM Length L Ch R = 1 ,16521.83,3.27,3.02,2.37
XS GIS Cut Line= 4
    -610542.1235   -1045699.3356    -610543.0548   -1045657.4255
    -610557.9562   -1045571.9967    -610579.7877   -1045484.1398
#Sta/Elev= 30
       0     352    2.23  351.87    2.87  351.49   17.63  351.46   17.91  351.07
   19.03  350.45    20.5  349.46   24.26  346.01   24.53  345.06   28.17  344.99
    32.1  344.73   33.81  344.78   33.85   345.3   34.06  346.04   37.87  346.19
   43.23   346.2    59.7  345.99   62.86  346.11   67.39  345.99   72.66  346.02
   76.82  346.17   84.53  346.16   85.58  346.05   90.13  346.02  110.02  346.18
   142.7  346.64  156.61  346.58   190.1  346.77  202.73  346.71  219.17  347.05
#Mann= 3 , 0 , 0
       0      .1       0   24.26     .04       0   34.06      .1       0
#XS Ineff= 2 , 0
                           55.28           347.7
Permanent Ineff=
       F       F
Bank Sta=24.26,34.06
XS Rating Curve= 0 ,0
Exp/Cntr=0.3,0.1

Type RM Length L Ch R = 1 ,16518.81,3.46,2.99,2.85
XS GIS Cut Line= 5
    -610546.3568   -1045698.7429    -610545.5101   -1045657.0869
    -610554.8235   -1045602.7307    -610562.3588   -1045568.4407
    -610570.4869   -1045528.0546
#Sta/Elev= 26
       0  351.99    1.21     352    1.22  351.69    1.53  351.49   17.28  351.38
   19.15  349.71   22.73346.1114   22.99  345.85   23.24  345.01   27.84  344.97
   31.12  344.83   33.51     345   33.79  346.02   40.37  346.11   57.88  345.83
   62.11  346.01   65.65  345.92   71.34  345.99   75.14  346.15   83.28  346.14
   84.52  346.02   87.74  345.99  101.44  346.15  109.64  346.12   137.1  346.55
  173.12  346.68
#Mann= 3 , 0 , 0
       0      .1       0   22.73     .04       0   33.79      .1       0
#XS Ineff= 2 , 0
                           52.69          348.06
Permanent Ineff=
       F       F
#Block Obstruct= 1 ,-1
  113.28  122.41349.2358
Bank Sta=22.73,33.79
XS Rating Curve= 0 ,0
Exp/Cntr=0.3,0.1

Type RM Length L Ch R = 1 ,16515.82,0.477,0.477,0.472
XS GIS Cut Line= 5
    -610549.2021   -1045701.0436    -610549.7798   -1045679.3474
    -610548.1328   -1045663.7179    -610550.4721   -1045643.0045
    -610581.5868   -1045484.5631
#Sta/Elev= 30
       0  352.19    2.75  352.14    2.76  351.49   13.52   351.4   18.86  351.14
   20.33  351.32   23.28   347.4   24.79  345.99   25.58  345.26   26.18  345.11
   32.48   344.9   36.26  344.97   36.35  345.55   36.47  345.99   43.76  345.98
   54.05   345.7   58.86  345.66   64.28   345.9   66.66  345.84   72.41  345.93
   76.19  346.13   84.83  346.12   86.33  345.97   87.61  345.96   99.59  346.08
  112.21  346.05  137.16  346.48  188.56  346.73  203.93   346.7  219.73  347.06
#Mann= 3 , 0 , 0
       0      .1       0   24.79    .035       0   36.47      .1       0
#XS Ineff= 2 , 0
                           52.83          348.06
Permanent Ineff=
       F       F
#Block Obstruct= 2 ,-1
  114.98  124.12349.1804   85.71  103.01  349.05
Bank Sta=24.79,36.47
XS Rating Curve= 0 ,0
Exp/Cntr=0.3,0.1

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
Type RM Length L Ch R = 1 ,16512.96,0.493,0.493,0.475
XS GIS Cut Line= 5
    -610552.0539   -1045700.8215    -610552.6316   -1045679.1253
    -610550.9846   -1045663.4958-610553.32389999   -1045642.7824
    -610576.8487   -1045519.6843
#Sta/Elev= 30
       0  352.15     .88  352.14     .89  351.94    1.51  351.49    8.34  351.41
      18  350.93   19.85  349.58    26.3  345.45    27.7  345.23   27.74  344.65
   27.88   343.7   29.02  343.75   29.03  342.01   31.43  341.81   33.14  341.98
   34.64  342.65   35.82  342.91   35.83  343.49   35.84   343.7   36.18  343.77
   36.59  345.89   36.64  345.88   45.06   345.9   57.42  345.52   70.34  345.82
   74.35   346.1   85.98  345.94  111.96  346.03  134.86  346.43  183.59   346.7
#Mann= 3 , 0 , 0
       0      .1       0    26.3    .035       0   36.64      .1       0
#Block Obstruct= 3 ,-1
  114.14  123.28349.1454   85.25  102.53348.9921  144.27  152.58349.4734
Bank Sta=26.3,36.64
XS Rating Curve= 0 ,0
Exp/Cntr=0.3,0.1

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
Type RM Length L Ch R = 1 ,16510   ,3.1,3.09,3.07
XS GIS Cut Line= 5
    -610554.9674   -1045700.2362    -610555.5451     -1045678.54
    -610553.8981   -1045662.9105-610556.23739999   -1045642.1971
    -610579.7622    -1045519.099
#Sta/Elev= 30
       0  352.13     .91  352.14    1.32  351.33    4.96  351.42    17.6   350.8
   18.66  350.03   25.87  345.58   27.05  345.46   27.33  345.41   27.49  343.54
   28.05   343.7   28.06  342.41   29.93  342.15   31.79  342.17   33.22  342.07
   33.41  342.15   34.55  342.18   36.07  342.94   36.08  344.27   36.36  345.72
   46.41  345.82   56.04  345.48   67.35  345.77   67.67  345.71   72.86  346.08
   87.49  345.93   111.4     346  131.93  346.36  141.61  346.32  183.59   346.7
#Mann= 3 , 0 , 0
       0      .1       0   27.05    .035       0   36.36      .1       0
#Block Obstruct= 2 ,-1
   84.43  101.71348.9938   143.4  151.71349.3952
Bank Sta=27.05,36.36
XS Rating Curve= 0 ,0
Exp/Cntr=0.3,0.1

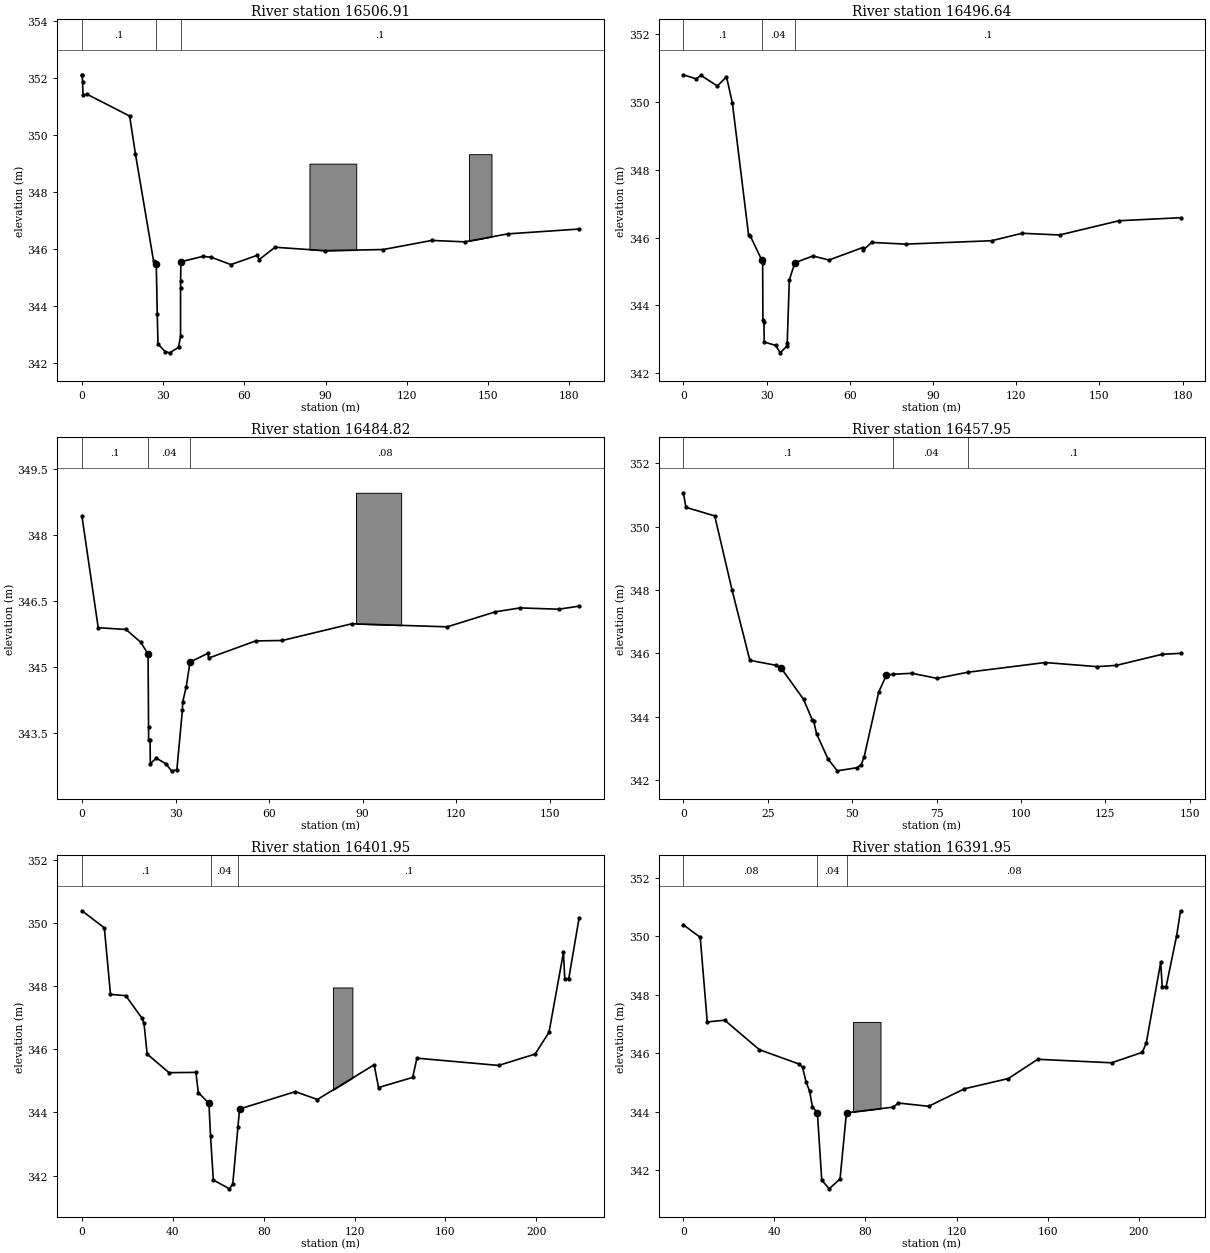
Type RM Length L Ch R = 1 ,16506.91,10.74,10.26,7.39
XS GIS Cut Line= 5
    -610558.0583   -1045700.0491     -610558.636   -1045678.3529
     -610556.989   -1045662.7234-610559.32829999     -1045642.01
    -610582.8531   -1045518.9119
#Sta/Elev= 30
       0  352.11     .08  352.11     .22  351.84     .39   351.4    1.79  351.43
    17.6  350.66   19.74  349.33   26.45  345.56   27.44  345.45   27.81  343.69
   28.07  342.65   30.74  342.38   32.37  342.34   35.65  342.53    36.4  342.92
   36.41  344.61   36.42  344.87   36.54  345.54   44.67  345.73    47.7   345.7
   54.99  345.44   64.81  345.77   65.35  345.61    71.3  346.05    89.6  345.93
  111.25  345.97  129.19  346.29   141.3  346.24  157.27  346.52  183.59  346.69
#Mann= 3 , 0 , 0
       0      .1       0   27.44    .035       0   36.54      .1       0
#Block Obstruct= 2 ,-1
      84  101.28348.9877  142.91  151.22349.3203
Bank Sta=27.44,36.54
XS Rating Curve= 0 ,0
Exp/Cntr=0.3,0.1

Type RM Length L Ch R = 1 ,16496.64,11.84,11.82,12.2
XS GIS Cut Line= 5
-610568.93389999   -1045699.5274-610569.01029999   -1045673.3139
    -610566.1424   -1045658.7355    -610566.0002   -1045643.5141
    -610591.1844   -1045523.1212
#Sta/Elev= 30
       0  350.81    4.59  350.69    6.39  350.79   12.24  350.48   15.55  350.75
   17.67  349.98   23.53  346.07   24.13  346.05   28.27  345.34   28.59  345.26
   28.68  343.56   29.06  343.51   29.15  342.92   33.26  342.82   34.94   342.6
   37.33   342.8   37.45  342.89   38.21  344.75   40.19  345.26   46.74  345.46
   52.51  345.34   64.67  345.71   64.94  345.64   67.88  345.86   80.18  345.81
  111.15  345.91  122.14  346.13  135.67  346.08  157.06   346.5  179.29  346.59
#Mann= 3 , 0 , 0
       0      .1       0   28.27     .04       0   40.19      .1       0
Bank Sta=28.27,40.19
XS Rating Curve= 0 ,0
Exp/Cntr=0.3,0.1

Type RM Length L Ch R = 1 ,16484.82,24.61,26.87,29.73
XS GIS Cut Line= 5
    -610578.8018   -1045690.2112    -610580.5927   -1045670.9478
    -610577.7248   -1045656.3694    -610578.6325   -1045641.3372
    -610601.1836   -1045533.5318
#Sta/Elev= 27
       0  348.42    5.21  345.89   14.12  345.85   18.84  345.56    21.2  345.29
   21.35  343.63   21.37  343.33   21.84  343.35   21.91   342.8   23.79  342.93
   26.89   342.8   28.71  342.64   30.42  342.66    32.2  344.02   32.28   344.2
   33.43  344.55   34.64  345.11   40.42  345.31   40.58   345.2    55.7  345.59
   64.24   345.6   86.53  345.98  117.11  345.91  132.48  346.25  140.48  346.34
  152.86  346.31   159.4  346.38
#Mann= 3 , 0 , 0
       0      .1       0    21.2     .04       0   34.64     .08       0
#Block Obstruct= 1 ,-1
   87.85  102.34 348.954
Bank Sta=21.2,34.64
XS Rating Curve= 0 ,0
Exp/Cntr=0.3,0.1

Type RM Length L Ch R = 1 ,16457.95,27.86,29.15,31.23
XS GIS Cut Line= 5
    -610600.4112   -1045709.3366    -610604.6319   -1045671.6896
    -610607.2707   -1045651.8644-610610.81619999   -1045634.4717
     -610633.272   -1045566.4278
#Sta/Elev= 27
       0  351.07     .76  350.61    9.29  350.34   14.42     348    19.7  345.78
   27.53  345.62      29  345.53   35.59  344.55   38.18   343.9   38.58  343.87
   39.46  343.46   42.87  342.66   45.62  342.29   51.48  342.39   52.72  342.49
   53.58  342.74   57.88  344.78   60.14  345.31   62.13345.3404   67.71  345.37
   75.12  345.21   84.25 345.403  107.15  345.71  122.62  345.58  128.27  345.62
  141.83  345.97  147.29     346
#Mann= 3 ,-1 , 0
       0      .1       0   62.13     .04       0   84.25      .1       0
Bank Sta=29,60.14
XS Rating Curve= 0 ,0
Exp/Cntr=0.3,0.1

Type RM Length L Ch R = 1 ,16401.95,1.88,1.88,1.88
XS GIS Cut Line= 6
    -610643.0462   -1045735.4757    -610657.9483   -1045686.2902
-610661.88529999   -1045666.6815-610664.87119999    -1045645.638
-610675.02239999   -1045602.4955-610708.26749999   -1045527.6306
#Sta/Elev= 30
       0  350.39    9.85  349.85   12.56  347.74   19.29   347.7   26.28     347
   27.32  346.82    28.7  345.85   38.33  345.26   50.16  345.27   51.22  344.63
    55.9  344.29   56.59343.2583   57.83  341.86   64.94  341.58   66.39  341.74
   68.65343.5249   69.38  344.11   93.96  344.66  103.63  344.41  128.62  345.51
  130.57  344.79  145.58  345.11  147.47  345.72  183.43  345.49  199.49  345.85
  205.61  346.54  211.97  349.07  212.55  348.24   214.3  348.24  218.88  350.17
#Mann= 3 ,-1 , 0
       0      .1       0   56.59     .04       0   68.65      .1       0
#Block Obstruct= 1 ,-1
  110.49  119.04347.9603
Bank Sta=55.9,69.38
XS Rating Curve= 0 ,0
Exp/Cntr=0.5,0.3

Type RM Length L Ch R = 1 ,16391.95,18.23,18.4,18.11
XS GIS Cut Line= 6
    -610650.4058   -1045738.2674    -610658.0192   -1045723.5482
     -610669.287   -1045687.5937     -610674.261   -1045646.3993
    -610688.4727    -1045603.003-610717.91099999   -1045531.9448
#Sta/Elev= 30
       0   350.4    7.41  349.97   10.49  347.07   18.16  347.13   33.37  346.12
   50.73  345.63   52.36  345.51   53.89  345.02   55.45   344.7   56.67  344.17
   58.88343.9468   60.79  341.65   64.07  341.35   68.83  341.69   71.64  343.96
   71.91  343.96   92.16  344.15   94.48  344.29  107.73  344.18  123.49  344.78
  142.72  345.13  155.66  345.79  188.15  345.67  201.62  346.03  203.37  346.36
  209.67  349.11  210.34  348.28  212.07  348.28  216.69  350.03   218.4  350.88
#Mann= 3 ,-1 , 0
       0     .08       0   58.88     .04       0   71.91     .08       0
#Block Obstruct= 1 ,-1
   74.51    86.6347.0706
Bank Sta=58.88,71.91
XS Rating Curve= 0 ,0
Exp/Cntr=0.3,0.1

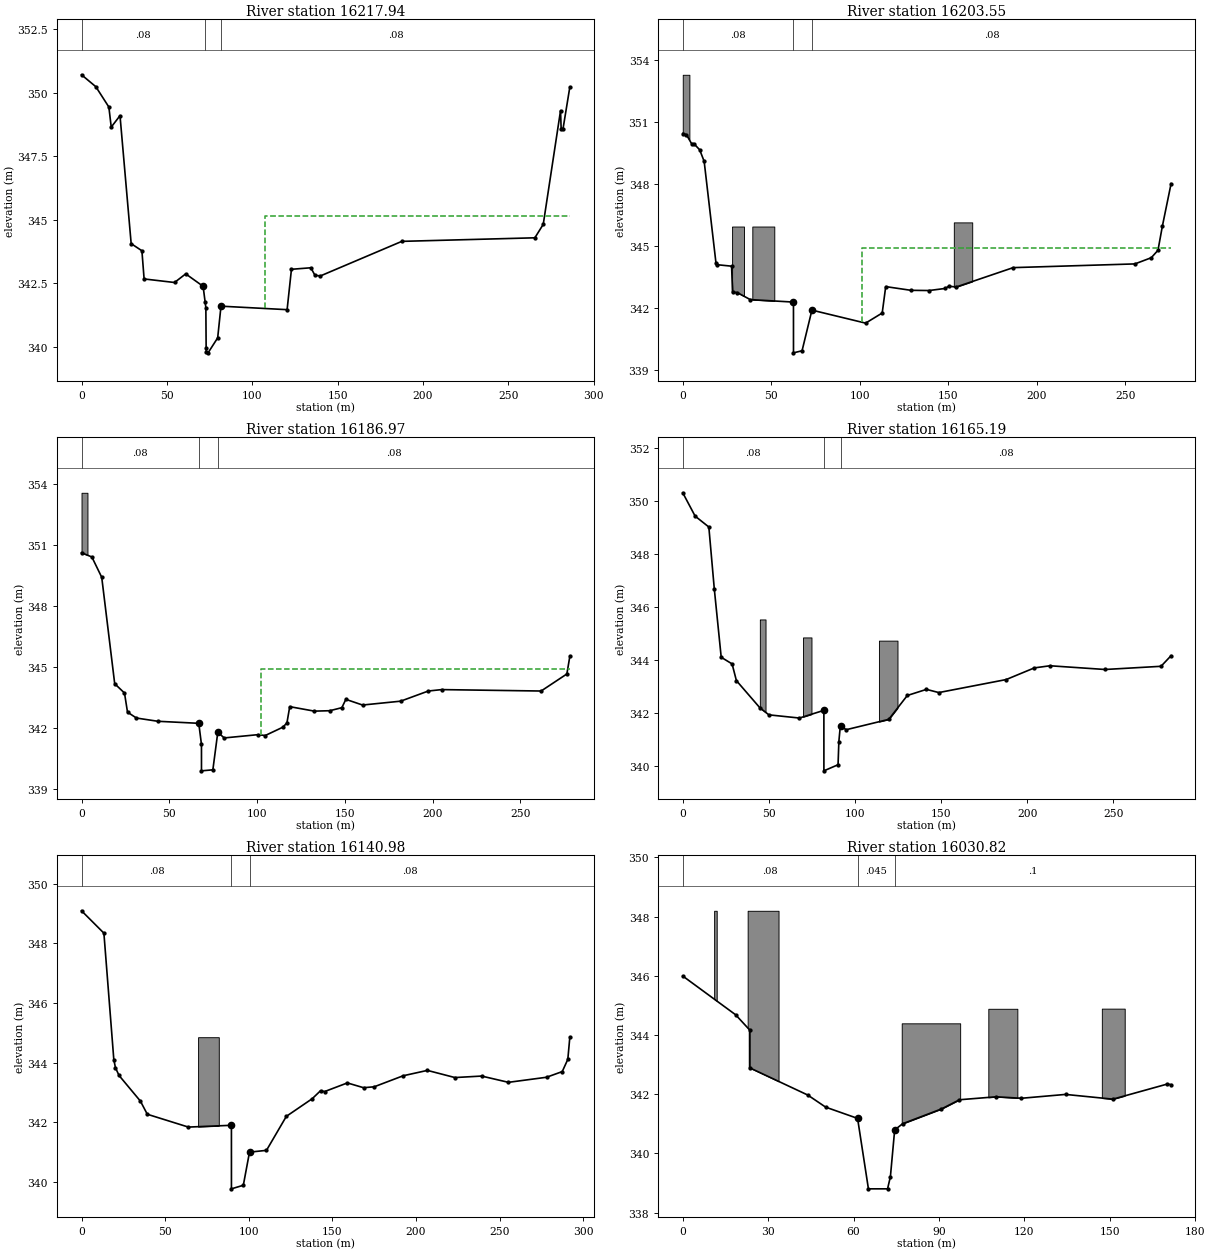
Type RM Length L Ch R = 1 ,16217.94,17.82,14.38,10.85
XS GIS Cut Line= 6
    -610749.3409   -1045804.8633    -610792.0326   -1045754.9198
    -610808.2784   -1045743.2547    -610827.6222   -1045711.1307
    -610872.3427   -1045570.3783    -610872.3427   -1045555.1515
#Sta/Elev= 30
       0  350.71    8.39  350.24   16.02  349.44   17.41  348.65   22.55   349.1
   29.09  344.06   35.38  343.78   36.67  342.67   54.49  342.53   61.05  342.87
   71.24  342.38   72.44341.7539   72.85  341.54   73.02  339.95    73.1  339.81
   74.14  339.76   79.78  340.35   81.72341.5977  120.46  341.46     123  343.05
  134.37  343.11  136.79  342.81  140.02  342.79  187.68  344.15  265.62  344.29
  270.54  344.82  280.67   349.3  281.02  348.59  282.12  348.58  286.12  350.23
#Mann= 3 ,-1 , 0
       0     .08       0   72.44     .04       0   81.72     .08       0
#XS Ineff= 2 , 0
                          107.39          345.13
Permanent Ineff=
       F       F
Bank Sta=71.24,81.72
XS Rating Curve= 0 ,0
Exp/Cntr=0.3,0.1

Type RM Length L Ch R = 1 ,16203.55,16.98,16.59,13.12
XS GIS Cut Line= 5
    -610769.6559   -1045808.4823    -610808.1264   -1045763.0171
    -610815.1211   -1045751.5259    -610847.5962   -1045700.0653
    -610890.0638   -1045564.6689
#Sta/Elev= 30
       0  350.46    2.07   350.4    4.97  349.97    6.36  349.96    9.56  349.67
   12.09  349.11   18.75  344.19   19.58   344.1   27.59  344.03    28.1  342.77
   30.81  342.75   38.12  342.41   62.52  342.29   62.53  339.83   67.37  339.93
   72.94   341.9  103.27  341.27  112.63  341.76  114.61  343.04  128.88  342.86
  139.06  342.85  148.15  342.95  150.27  343.06  154.36  343.02  186.61  343.96
  255.33  344.14  264.57  344.44  268.36   344.8  270.82  345.96  275.76  348.03
#Mann= 3 , 0 , 0
       0     .08       0   62.52     .04       0   72.94     .08       0
#XS Ineff= 2 , 0
                          101.15          344.89
Permanent Ineff=
       F       F
#Block Obstruct= 4 ,-1
  153.07  163.46346.1526       0    3.74353.3066   27.86   34.56 345.952
   39.28   51.69 345.952
Bank Sta=62.52,72.94
XS Rating Curve= 0 ,0
Exp/Cntr=0.3,0.1

Type RM Length L Ch R = 1 ,16186.97,23.06,21.77,16.29
XS GIS Cut Line= 5
    -610779.6482   -1045816.9759    -610825.1134   -1045768.5129
    -610828.6108   -1045757.0217-610860.08659999   -1045702.5634
    -610908.5496   -1045574.6612
#Sta/Elev= 30
       0  350.62    5.89  350.41   11.51  349.41    18.9  344.17   24.48  343.71
   26.19  342.77   31.27  342.48   43.49  342.32   66.78  342.22   68.32  341.18
   68.33  339.88   74.81  339.93   77.62  341.78   81.26   341.5  100.37  341.66
  104.66  341.62   114.7  342.03     117  342.24  118.59  343.04   132.6  342.82
  141.36  342.84  148.28  342.99  150.56   343.4  160.08  343.12  181.77  343.31
  197.52  343.81  205.12  343.88  261.78  343.81  276.45  344.65  278.14  345.52
#Mann= 3 , 0 , 0
       0     .08       0   66.78     .04       0   77.62     .08       0
#XS Ineff= 2 , 0
                          102.02          344.89
Permanent Ineff=
       F       F
#Block Obstruct= 1 ,-1
       0    3.38 353.571
Bank Sta=66.78,77.62
XS Rating Curve= 0 ,0
Exp/Cntr=0.3,0.1

Type RM Length L Ch R = 1 ,16165.19,23.88,24.21,22.28
XS GIS Cut Line= 4
    -610790.1402   -1045840.9575-610846.59699999    -1045775.008
    -610849.0951   -1045761.5183-610919.04149999   -1045584.6535
#Sta/Elev= 27
       0   350.3    7.18  349.42   15.14  349.01   18.29  346.69   22.32   344.1
   28.64  343.85   31.14  343.22   44.85  342.19   50.01  341.93   67.73  341.81
   81.92   342.1   81.93  339.82   90.15  340.05   90.61  340.92   91.47  341.52
   91.57  341.52   94.87  341.37  119.58  341.76  130.35  342.66  141.45  342.89
  148.64  342.77  187.72  343.26  204.08   343.7  213.17  343.78  245.14  343.64
  277.62  343.76  283.46  344.16
#Mann= 3 , 0 , 0
       0     .08       0   81.92     .04       0   91.57     .08       0
#Block Obstruct= 3 ,-1
   44.75   48.05345.5259   69.81   74.72344.8481  113.88  124.65344.7277
Bank Sta=81.92,91.57
XS Rating Curve= 0 ,0
Exp/Cntr=0.3,0.1

Type RM Length L Ch R = 1 ,16140.98,20.09,21.91,20.25
XS GIS Cut Line= 4
    -610811.1241   -1045849.9506    -610870.5786   -1045779.5045
-610873.07669999   -1045762.0179    -610940.0255   -1045585.6527
#Sta/Elev= 29
       0  349.09   13.38  348.34   19.31   344.1   20.29  343.83   22.43  343.57
   35.21  342.71   39.32  342.27   63.88  341.84   89.62   341.9   89.63  339.77
   96.74  339.89  100.43     341  110.58  341.06  122.46   342.2   137.9  342.79
  142.93  343.06  145.31  343.03  158.93  343.32  168.61  343.16  174.96  343.19
  192.29  343.56  206.78  343.74  223.24   343.5   239.2  343.55  255.24  343.34
  278.02  343.51   287.4   343.7  290.74  344.11  291.95  344.86
#Mann= 3 , 0 , 0
       0     .08       0   89.62     .04       0  100.43     .08       0
#Block Obstruct= 1 ,-1
   69.69   82.07344.8526
Bank Sta=89.62,100.43
XS Rating Curve= 0 ,0
Exp/Cntr=0.3,0.1

Type RM Length L Ch R = 1 ,16030.82,23.32,23.08,22.14
XS GIS Cut Line= 4
-610933.67859999    -1045873.336    -610963.0078   -1045822.4717
-610974.99879999   -1045806.4839-611012.67509999   -1045721.6095
#Sta/Elev= 20
       0  345.99   18.59  344.68   23.48  344.17   23.49  342.89    43.9  341.97
   50.21  341.56   61.42  341.18   65.23   338.8   71.95   338.8   72.95  339.21
   74.45  340.79   77.25     341    90.9   341.5   97.22  341.81  110.09  341.91
  118.98  341.86  134.47  341.99  151.11  341.83  170.21  342.34  171.56  342.32
#Mann= 3 , 0 , 0
       0     .08       0   61.42    .045       0   74.45      .1       0
#Block Obstruct= 5 ,-1
  107.35  117.55344.8834  147.23  155.27344.8887   76.93   97.46 344.392
   11.02   11.93348.1946    22.8   33.65348.1946
Bank Sta=61.42,74.45
XS Rating Curve= 0 ,0
Exp/Cntr=0.3,0.1

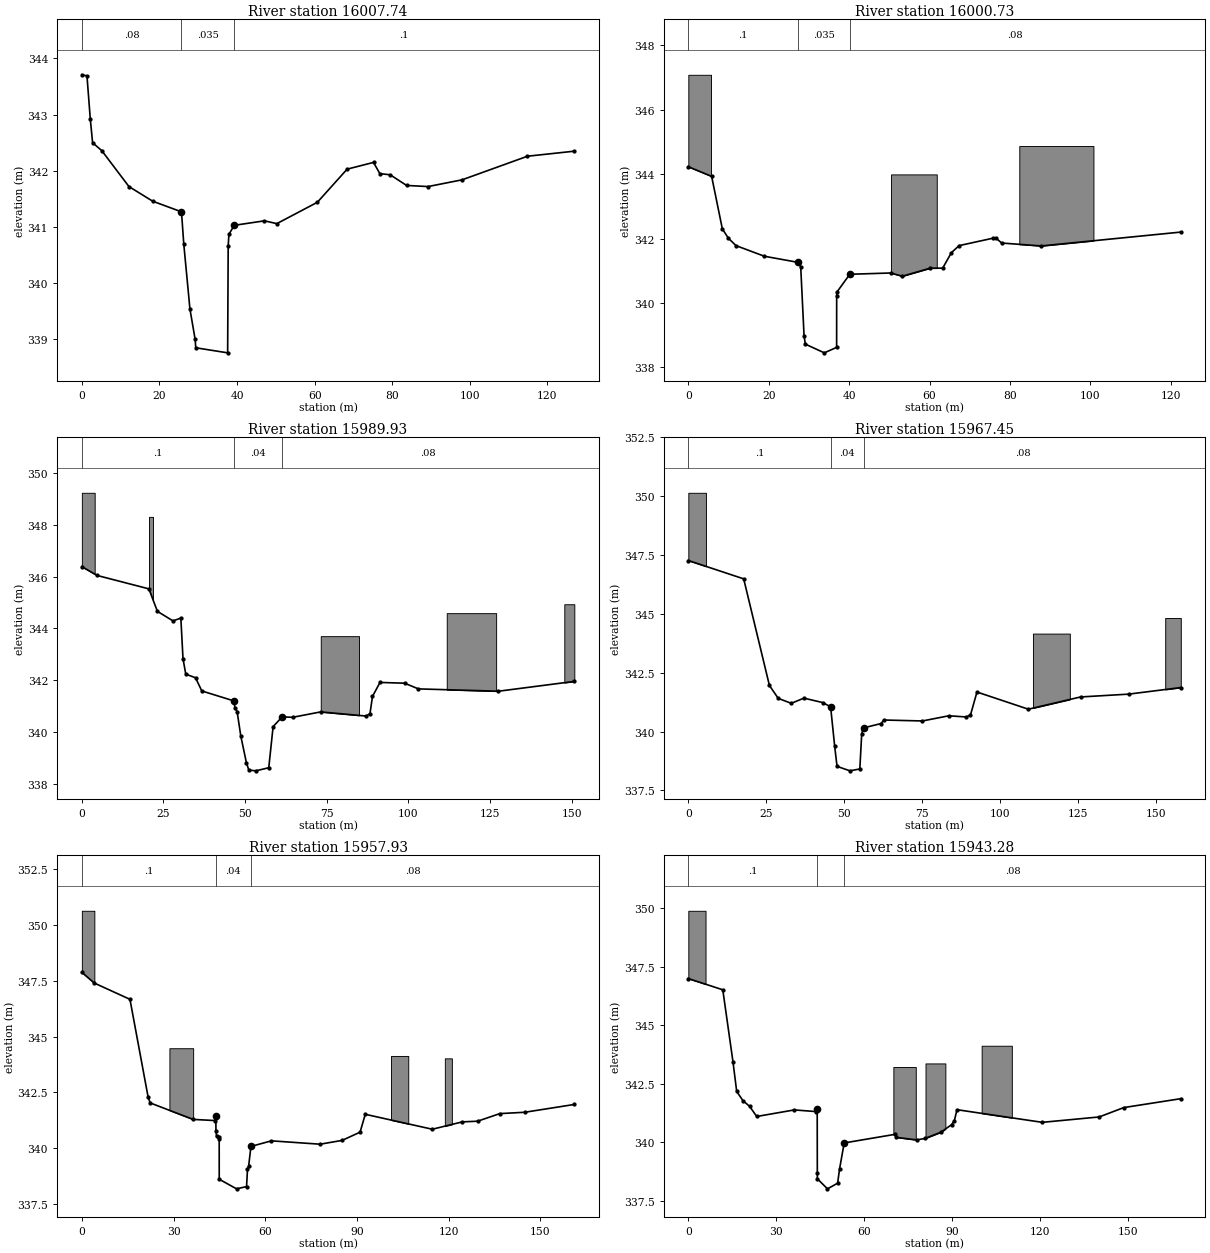
Type RM Length L Ch R = 1 ,16007.74,6.71,7.01,8.54
XS GIS Cut Line= 6
-610971.77129999   -1045859.4797    -610980.0408   -1045836.7296
    -610989.9356   -1045825.7279    -610992.9954   -1045818.0942
-611010.51089999   -1045778.8608    -611023.0044   -1045744.3002
#Sta/Elev= 28
       0  343.71    1.32  343.69    2.18  342.92    2.77   342.5    5.13  342.36
   12.14  341.72   18.24  341.46   25.68  341.27   26.28  340.69   27.86  339.54
    29.2     339   29.37  338.85   37.58  338.76   37.72  340.66   37.91  340.87
   39.28  341.03   47.07  341.11   50.26  341.06    60.7  341.44   68.38  342.03
   75.18  342.15   76.81  341.95   79.46  341.93   83.71  341.74   89.23  341.72
   98.01  341.84  114.86  342.26  126.94  342.35
#Mann= 3 , 0 , 0
       0     .08       0   25.68    .035       0   39.28      .1       0
Bank Sta=25.68,39.28
XS Rating Curve= 0 ,0
Exp/Cntr=0.5,0.3

Type RM Length L Ch R = 1 ,16000.73,9.83,10.81,10.61
XS GIS Cut Line= 5
     -610976.975   -1045864.1751    -610985.2445    -1045841.425
    -610997.4496   -1045827.8546-611019.62709999   -1045783.7506
    -611027.9807   -1045754.2729
#Sta/Elev= 26
       0  344.23     5.8  343.93    8.46   342.3    9.96  342.01   11.85  341.78
   18.91  341.45   27.28  341.26   27.95  341.12   28.78  338.98    29.1  338.72
   33.82  338.45   36.88  338.62   36.89   340.2   36.91  340.33   40.15  340.89
   50.35  340.93   53.21  340.83   60.15  341.08   63.25  341.08   65.41  341.56
   67.34  341.78   75.75  342.01   76.44  342.02   77.92  341.86   87.77  341.77
  122.46   342.2
#Mann= 3 , 0 , 0
       0      .1       0   27.28    .035       0   40.15     .08       0
#Block Obstruct= 3 ,-1
       0    5.64347.0853    82.3  100.74344.8723   50.41   61.78343.9916
Bank Sta=27.28,40.15
XS Rating Curve= 0 ,0
Exp/Cntr=0.5,0.3

Type RM Length L Ch R = 1 ,15989.93,23.84,22.47,19.81
XS GIS Cut Line= 6
    -610970.3973   -1045887.0677    -610993.4662   -1045848.7396
    -611005.6395   -1045834.6026    -611029.7291    -1045788.774
    -611034.3488   -1045770.0031    -611035.9998    -1045753.747
#Sta/Elev= 30
       0  346.39    4.63  346.05   20.52  345.53   23.14  344.66   27.92  344.29
   30.32   344.4   30.98  342.83   31.83  342.23   34.82  342.09   36.74  341.58
   46.45   341.2   46.96  340.92   47.56  340.78   48.68  339.84   50.39  338.81
   51.14  338.52   53.27  338.49   57.25  338.61   58.58   340.2   61.37  340.58
   64.54  340.56   73.16  340.77   87.05  340.61   88.25   340.7   89.02  341.37
   91.32  341.91   98.87  341.88  103.09  341.66   127.6  341.57  150.84  341.95
#Mann= 3 , 0 , 0
       0      .1       0   46.45     .04       0   61.37     .08       0
#Block Obstruct= 5 ,-1
   20.56    21.8348.3146  111.76  126.89  344.59   73.17    84.9   343.7
       0    3.93349.2465  147.77  150.84344.9349
Bank Sta=46.45,61.37
XS Rating Curve= 0 ,0
Exp/Cntr=0.3,0.1

Type RM Length L Ch R = 1 ,15967.45,9.35,9.53,9.59
XS GIS Cut Line= 5
-610992.09319999   -1045900.0587    -611013.8884   -1045860.6581
-611022.15659999   -1045848.0903-611039.60269999   -1045797.2262
-611042.06069999   -1045753.1775
#Sta/Elev= 26
       0  347.27   17.76  346.49   26.01  341.96   28.84  341.41   33.02   341.2
   37.08  341.42   43.15  341.23   45.64  341.05   46.95  339.37    47.7  338.52
   51.85  338.33   55.01  338.41   55.61  339.89   56.02  340.12   56.35  340.16
   61.82  340.34   62.73  340.49    75.1  340.45   83.56  340.67   89.14  340.62
    90.5   340.7   92.58  341.68  109.06  340.95   125.8  341.47  141.22  341.59
  157.96  341.87
#Mann= 3 , 0 , 0
       0      .1       0   45.64     .04       0   56.35     .08       0
#Block Obstruct= 3 ,-1
  110.54  122.37344.1635       0    5.65350.1486  152.96  157.96344.8275
Bank Sta=45.64,56.35
XS Rating Curve= 0 ,0
Exp/Cntr=0.3,0.1

Type RM Length L Ch R = 1 ,15957.93,15.71,14.65,13.63
XS GIS Cut Line= 5
     -611000.734   -1045904.2531    -611020.2591   -1045868.1678
-611030.47859999   -1045852.8987-611045.06769999   -1045811.8192
-611048.78449999   -1045753.7894
#Sta/Elev= 30
       0  347.88    4.05   347.4   15.74  346.67   21.67   342.3   22.34  342.03
   36.42  341.29    43.5  341.24   43.53  341.44   43.83  341.45   43.88  340.76
   44.08  340.53   44.92  340.42   44.94  340.49   44.95  338.61   50.61  338.18
   53.89  338.28    54.2  339.05   54.58   339.2   55.32  340.08   62.03  340.33
   77.96  340.18   85.16  340.35   91.04  340.72   92.73  341.52  114.67  340.85
  124.49  341.18  129.49  341.21  136.74  341.55   144.9  341.61  161.14  341.96
#Mann= 3 , 0 , 0
       0      .1       0   43.83     .04       0   55.32     .08       0
#Block Obstruct= 4 ,-1
  118.77  121.07344.0259  101.15   106.8344.1338       0    4.09350.6369
   28.65   36.42344.4799
Bank Sta=43.83,55.32
XS Rating Curve= 0 ,0
Exp/Cntr=0.3,0.1

Type RM Length L Ch R = 1 ,15943.28,9.23,8.7,8.01
XS GIS Cut Line= 5
-611018.45259999   -1045911.2168    -611035.5181   -1045872.8951
-611044.51399999   -1045854.9034-611060.44139999   -1045803.4049
-611062.47329999   -1045751.5215
#Sta/Elev= 30
       0  346.99   11.75  346.51   15.23  343.43   16.49  342.17    18.6  341.78
   20.91  341.53   23.32   341.1   36.13  341.38   43.42  341.31   43.45  341.42
   43.92  341.41   43.94  341.41   43.98  338.67   43.99  338.44   47.44  338.01
    50.9  338.25   51.56  338.86   53.14  339.97    70.6  340.34   70.79  340.21
   77.82   340.1   80.64  340.16   86.13  340.43   89.75  340.75   90.69  340.92
   91.59  341.39  120.67  340.85  140.07  341.08  148.45  341.48  167.89  341.86
#Mann= 3 , 0 , 0
       0      .1       0   43.92     .04       0   53.14     .08       0
#Block Obstruct= 4 ,-1
   80.86   87.63 343.366     100  110.29344.1213    69.9   77.54 343.214
       0    5.87349.8845
Bank Sta=43.92,53.14
XS Rating Curve= 0 ,0
Exp/Cntr=0.3,0.1