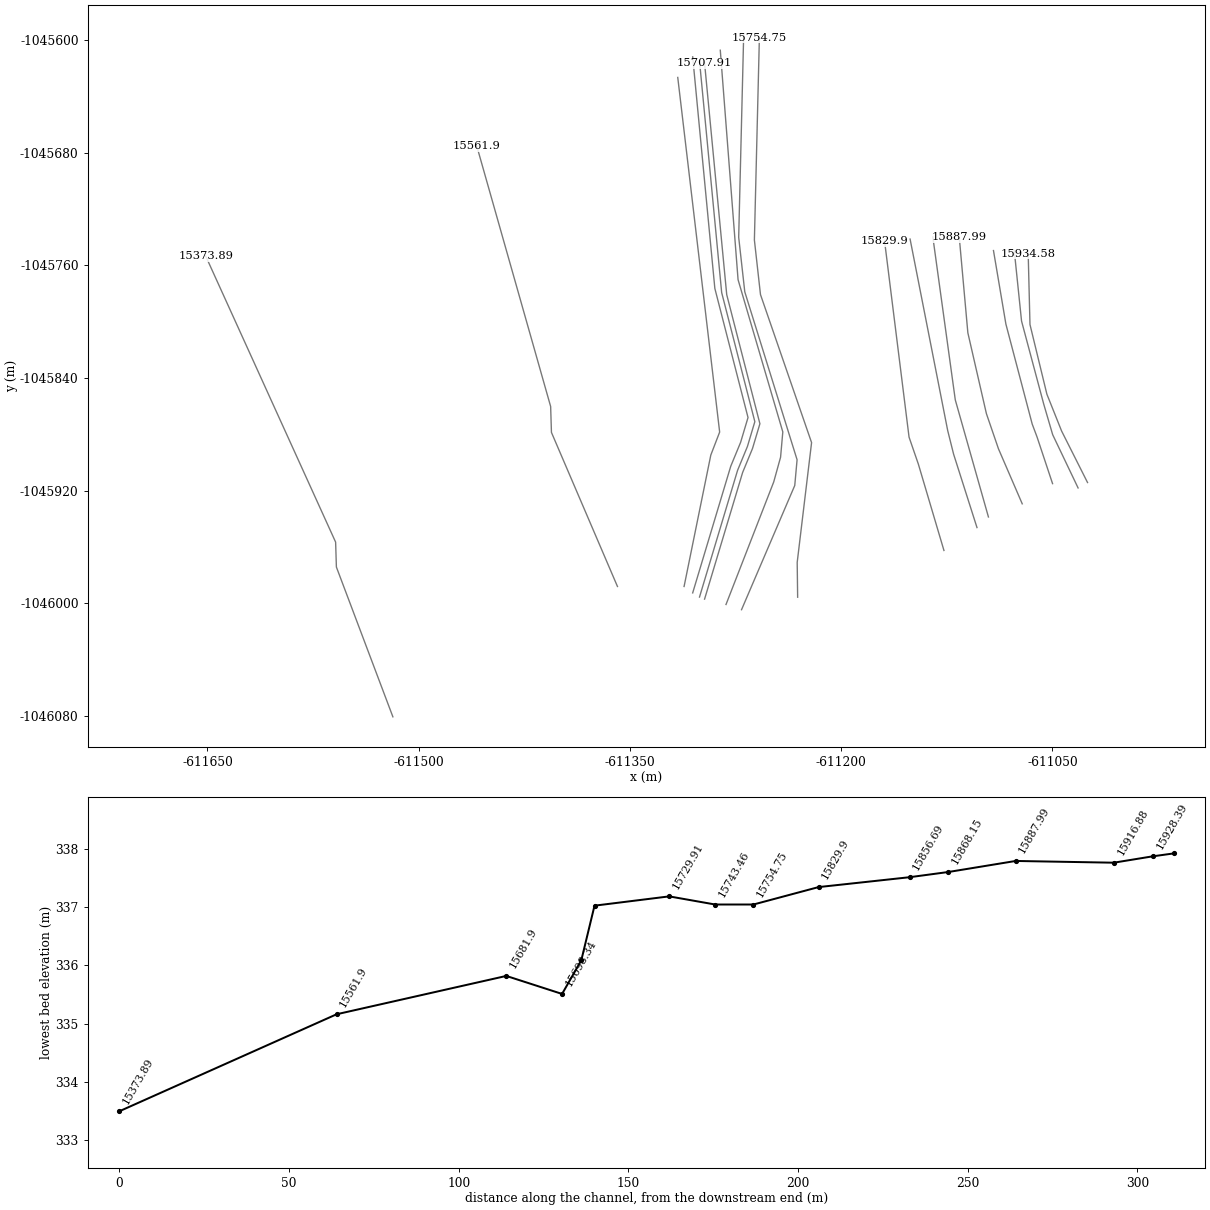
HEC-RAS study PPO_Kvasiny_efektiv.prj: PPO_Kvasiny_efektivita

--- PPO_Kvasiny_efektiv.g07 (geometry) --- (continued)

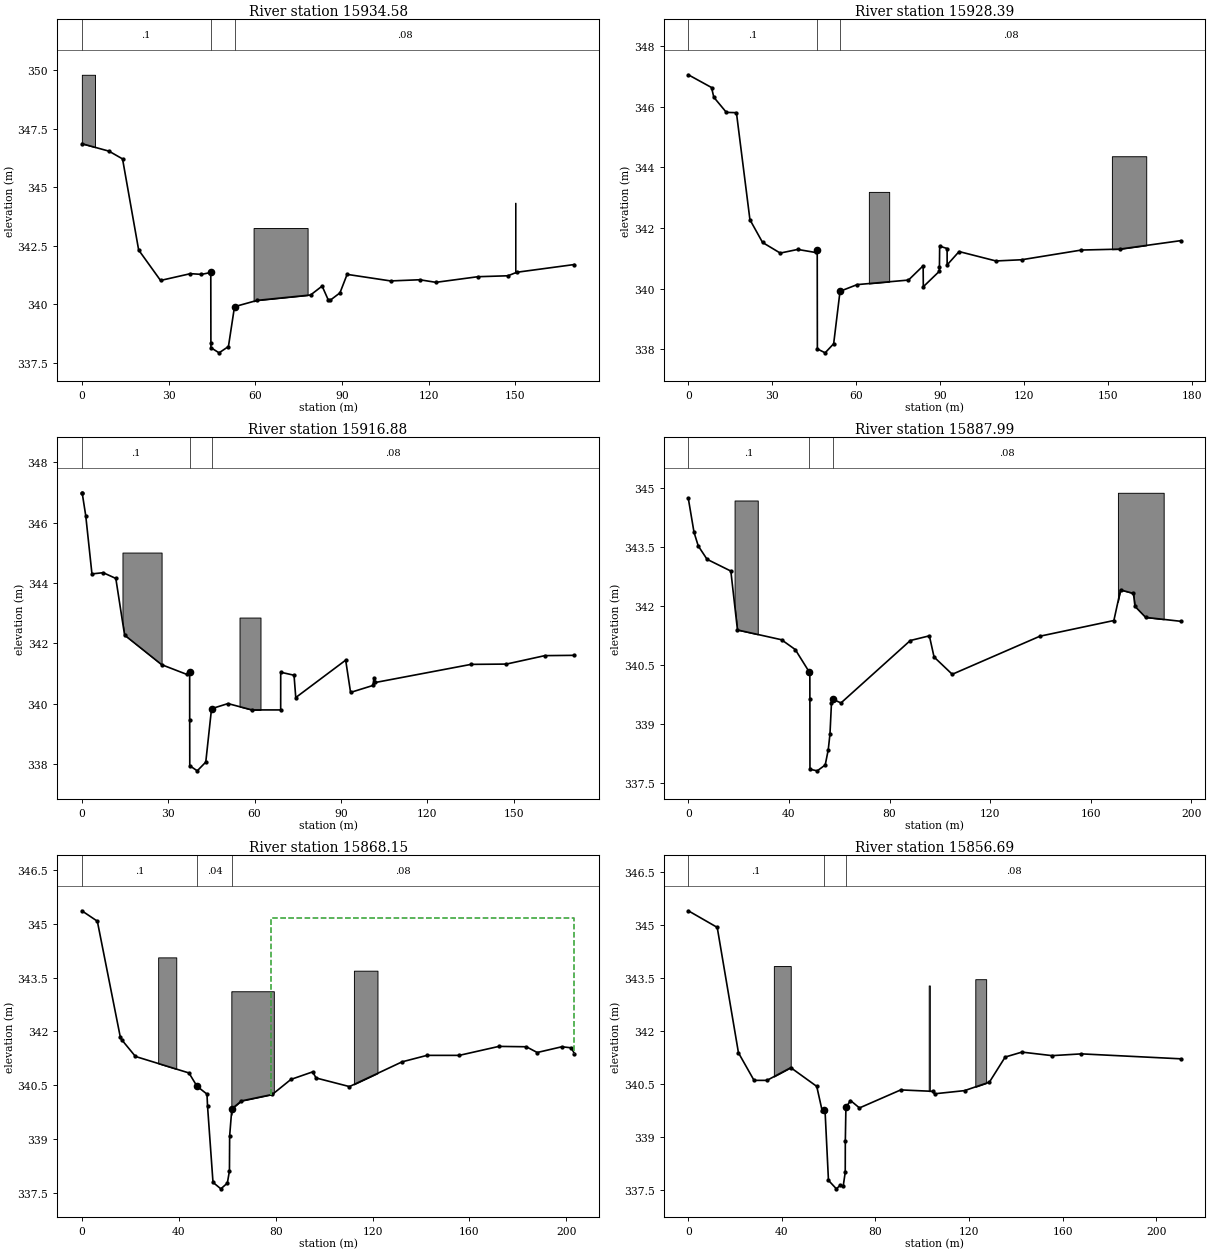
Type RM Length L Ch R = 1 ,15934.58,6.66,6.18,4
XS GIS Cut Line= 5
    -611025.0566   -1045914.2648    -611043.4717   -1045877.6887
-611053.92689999   -1045851.5159    -611065.9296   -1045802.0495
    -611067.1996   -1045751.6727
#Sta/Elev= 28
       0  346.86    9.39  346.54   14.08  346.21   19.66  342.32   27.23  341.02
   37.57  341.31    41.4  341.28    44.6  341.36   44.62  341.36   44.66  338.33
   44.67  338.15   47.49  337.93   50.73   338.2   52.83   339.9   60.69  340.17
   79.16   340.4   83.15  340.78   85.27  340.19   85.89  340.17   89.32  340.49
    91.8  341.28  106.84     341  116.94  341.05  122.53  340.94  137.05  341.18
  147.45  341.22  150.52  341.37  170.43   341.7
#Mann= 3 , 0 , 0
       0      .1       0    44.6     .04       0   52.83     .08       0
#Block Obstruct= 3 ,-1
   59.43   78.12343.2577  149.97  150.06344.3423       0    4.56349.8012
Bank Sta=44.6,52.83
XS Rating Curve= 0 ,0
Exp/Cntr=0.3,0.1

Type RM Length L Ch R = 1 ,15928.39,11.22,11.51,11.57
XS GIS Cut Line= 5
    -611031.7622   -1045918.1087-611049.80559999   -1045880.3034
-611056.15569999   -1045858.6076    -611071.9197   -1045799.5853
    -611077.0852   -1045749.5899
#Sta/Elev= 30
       0  347.05    8.29  346.63     9.1  346.31   13.59  345.81   17.18   345.8
      22  342.27   26.51  341.52   32.82  341.17   39.07  341.29   45.43  341.19
   46.03  341.27   46.08  338.01   48.85  337.88    51.9  338.18   54.17  339.91
   60.29  340.13   78.62  340.28   83.85  340.75   83.91  340.06   89.64  340.57
   89.67  340.72   89.75   341.4   92.41  341.32   92.42  340.78   96.68  341.22
  109.85  340.91  119.02  340.95  140.36  341.27     154   341.3  175.85  341.58
#Mann= 3 , 0 , 0
       0      .1       0   46.03     .04       0   54.17     .08       0
#Block Obstruct= 2 ,-1
   64.47   71.72343.1876  151.25  163.51344.3635
Bank Sta=46.03,54.17
XS Rating Curve= 0 ,0
Exp/Cntr=0.3,0.1

Type RM Length L Ch R = 1 ,15916.88,28.68,28.89,29.62
XS GIS Cut Line= 5
    -611049.8937   -1045915.0428    -611060.9182    -1045881.891
    -611064.3608   -1045872.7106    -611083.0196   -1045801.8009
-611091.84849999   -1045749.5303
#Sta/Elev= 30
       0  346.99     .14  346.97    1.35  346.23    3.51   344.3    7.42  344.34
    11.8  344.15   14.85  342.27   27.72  341.29    36.4  340.97   37.45  341.06
   37.46  339.45   37.49  337.94   40.08  337.77   43.05  338.06   45.05  339.83
   50.76     340   59.07  339.79   69.07  339.79   69.08  341.04   73.71  340.94
   74.31   340.2   91.65  341.44   93.35  340.37  101.08   340.6   101.5  340.85
  101.99   340.7   135.2   341.3  147.48  341.31  160.85  341.59  171.08   341.6
#Mann= 3 , 0 , 0
       0      .1       0   37.45     .04       0   45.05     .08       0
#Block Obstruct= 2 ,-1
   54.77   62.06342.8527   14.11    27.7 345.008
Bank Sta=37.45,45.05
XS Rating Curve= 0 ,0
Exp/Cntr=0.3,0.1

Type RM Length L Ch R = 1 ,15887.99,19.91,19.84,18.61
XS GIS Cut Line= 5
-611071.43079999   -1045929.3784-611088.29679999   -1045890.3326
    -611096.8689   -1045865.3553-611110.03889999   -1045807.9662
    -611116.1349   -1045740.2327
#Sta/Elev= 30
       0  344.74    2.26  343.88    3.95  343.53    7.45  343.19   16.91  342.89
   19.54  341.39   37.06  341.14   42.53  340.89   48.17  340.31   48.32   340.3
   48.34  339.64   48.37  337.84   51.28   337.8   54.44  337.95   55.65  338.34
   56.33  338.74   56.93  339.54   57.62  339.62   60.71  339.53   88.27  341.12
   95.85  341.24   97.72   340.7  104.95  340.26   139.8  341.23  169.22  341.63
  171.87  342.41     177  342.32  177.61  341.99  181.85  341.71  195.83  341.61
#Mann= 3 , 0 , 0
       0      .1       0   48.17     .04       0   57.62     .08       0
#Block Obstruct= 2 ,-1
   18.39   27.61344.6881  170.83  189.02344.8846
Bank Sta=48.17,57.62
XS Rating Curve= 0 ,0
Exp/Cntr=0.3,0.1

Type RM Length L Ch R = 1 ,15868.15,11.59,11.46,10.73
XS GIS Cut Line= 3
    -611095.4338     -1045938.72    -611118.9712   -1045855.5772
    -611134.9309   -1045739.7811
#Sta/Elev= 30
       0  345.36    6.39  345.07    15.9  341.83   16.52  341.76   22.12   341.3
   44.21  340.84   47.53  340.47   51.66  340.25   51.88  339.92   54.14  337.79
   57.39  337.61   60.06  337.77   60.93  338.11   61.01  339.08   61.91  339.84
   65.86  340.06   78.61  340.24   86.31  340.66   95.28  340.87   96.69   340.7
  110.47  340.46  132.21  341.15  142.47  341.33  155.79  341.33  172.16  341.58
  183.48  341.57  187.98  341.41  198.16  341.57  202.07  341.54   203.3  341.38
#Mann= 3 , 0 , 0
       0      .1       0   47.53     .04       0   61.91     .08       0
#XS Ineff= 2 , 0
                           77.94          345.17
Permanent Ineff=
       F       F
#Block Obstruct= 3 ,-1
  112.31  122.04343.6905    31.5   38.97344.0612   61.71   79.25343.1169
Bank Sta=47.53,61.91
XS Rating Curve= 0 ,0
Exp/Cntr=0.3,0.1

Type RM Length L Ch R = 1 ,15856.69,26.05,26.8,27.68
XS GIS Cut Line= 4
    -611103.5637   -1045946.2449-611120.18499999   -1045894.0618
    -611124.3476   -1045877.4141     -611151.067   -1045741.3785
#Sta/Elev= 30
       0  345.39   12.36  344.92   21.44  341.37    28.1  340.59   33.62  340.59
   43.81  340.95   54.91  340.42   57.26  339.72   57.88  339.75   58.46  339.73
   59.92  337.76   63.31  337.52   64.92  337.62   66.21  337.59   67.09  337.99
   67.13  338.88   67.38  339.83   67.49  339.83   69.33  340.02   73.18  339.81
   90.82  340.32  104.41  340.28   105.3  340.21  118.11   340.3  128.73  340.54
  135.47  341.25  142.63  341.39  155.53  341.29  168.07  341.34  210.56   341.2
#Mann= 3 , 0 , 0
       0      .1       0   57.88    .035       0   67.49     .08       0
#Block Obstruct= 3 ,-1
   122.7  127.34343.4536  102.78  103.27 343.276   36.57   43.79343.8254
Bank Sta=57.88,67.49
XS Rating Curve= 0 ,0
Exp/Cntr=0.3,0.1

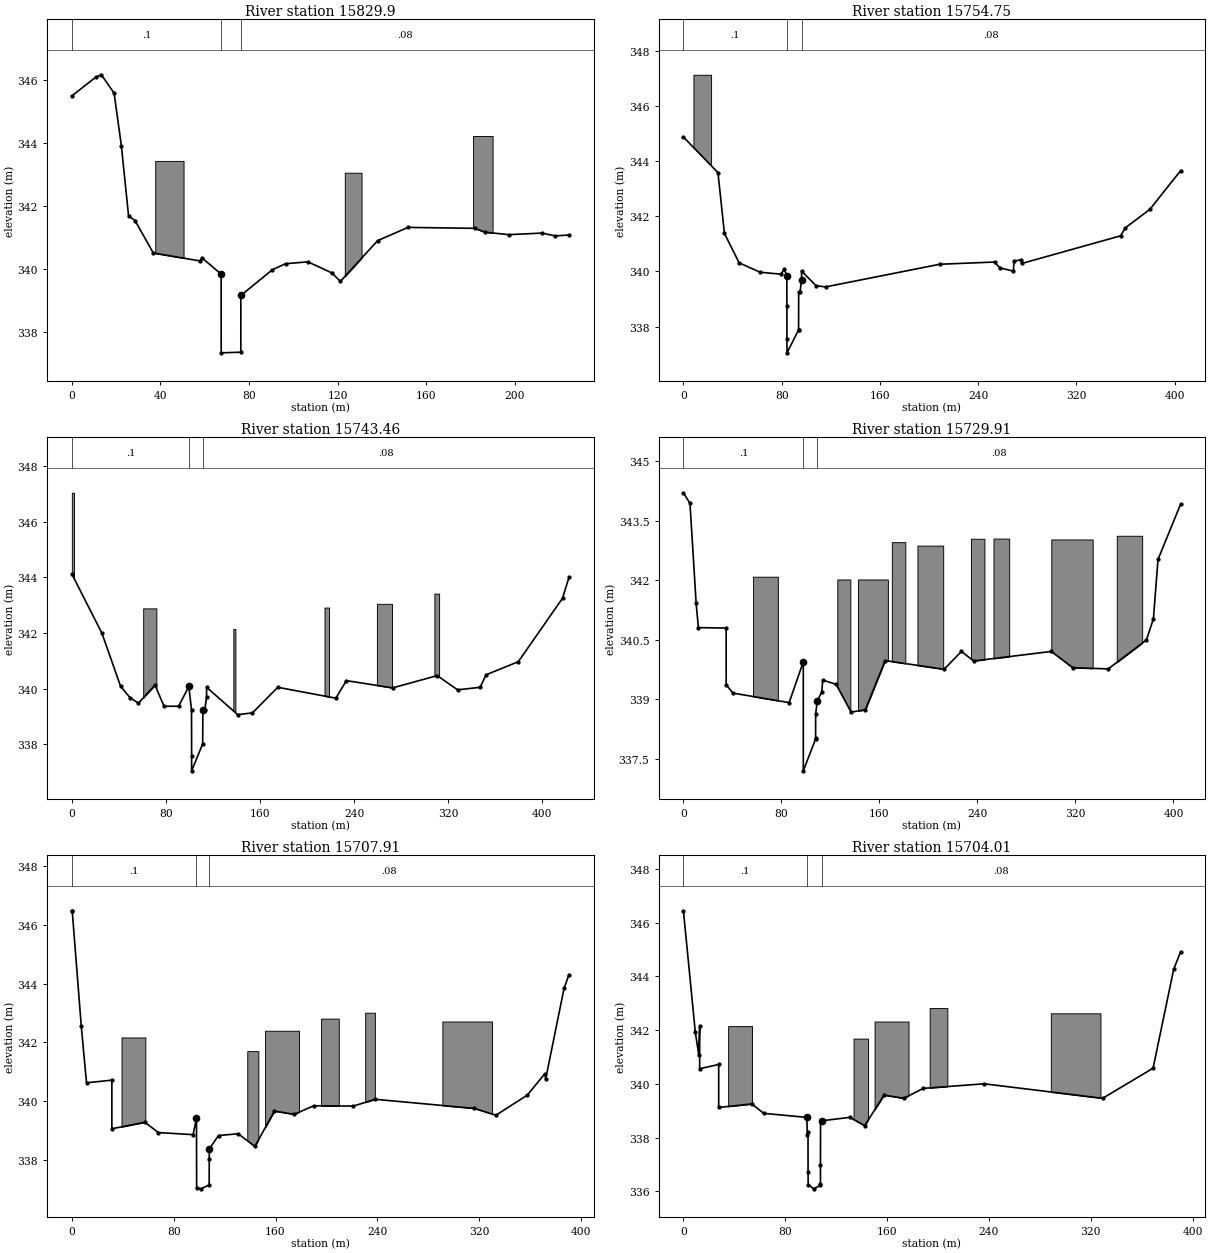
Type RM Length L Ch R = 1 ,15829.9 ,19.46,19.19,18.61
XS GIS Cut Line= 4
-611127.02369999   -1045962.5109-611145.18809999   -1045901.2055
    -611151.8026   -1045882.0232    -611169.1645    -1045742.966
#Sta/Elev= 28
       0  345.48   10.89  346.08   13.33  346.15   19.07  345.57   22.36   343.9
    25.6  341.69   28.57  341.53   36.77  340.51   57.75  340.26   58.86  340.35
   67.39  339.84    67.4  337.35   76.27  337.37   76.28  339.16   76.36  339.17
   90.51  339.98   96.45  340.17  106.54  340.23  117.37  339.88  121.19  339.61
  137.99   340.9  151.71  341.32  181.95  341.29  186.38  341.17  197.12  341.09
  212.17  341.14   218.2  341.05  224.37  341.08
#Mann= 3 , 0 , 0
       0      .1       0   67.39    .035       0   76.36     .08       0
#Block Obstruct= 3 ,-1
  123.19  130.76343.0505  181.09   189.9344.2119   37.64   50.42343.4244
Bank Sta=67.39,76.36
XS Rating Curve= 0 ,0
Exp/Cntr=0.3,0.1

Type RM Length L Ch R = 1 ,15754.75,11.28,11.29,11.04
XS GIS Cut Line= 6
     -611230.918   -1045995.6999    -611231.2355   -1045970.9348
    -611221.0212    -1045885.914    -611257.3088   -1045780.7867
    -611261.6351    -1045742.032    -611258.0872   -1045598.3207
#Sta/Elev= 30
       0  344.87   28.12  343.58   33.36  341.38   45.38  340.31    62.5  339.97
    79.6   339.9   81.88  340.08   84.19  339.85   84.22  338.74   84.29  337.54
    84.3  337.05   93.74  337.88   93.75  337.89   93.83  339.24   94.91  339.25
   96.15  339.68   96.21  340.01  108.01  339.48  115.83  339.44  208.71  340.26
  253.27  340.34  257.54  340.13  268.64  340.01  269.15  340.38  275.01  340.42
   275.6  340.29  355.89  341.29  359.79  341.58  379.77  342.25  404.72  343.65
#Mann= 3 , 0 , 0
       0      .1       0   84.19    .035       0   96.15     .08       0
#Block Obstruct= 1 ,-1
    8.14   22.52347.1254
Bank Sta=84.19,96.15
XS Rating Curve= 0 ,0
Exp/Cntr=0.5,0.3

Type RM Length L Ch R = 1 ,15743.46,14.98,13.54,10.62
XS GIS Cut Line= 6
    -611270.7595   -1046004.5644    -611232.9684    -1045916.367
-611231.32099999   -1045898.0854-611268.45829999   -1045778.8404
    -611272.7846   -1045740.0857    -611269.2368   -1045596.3744
#Sta/Elev= 30
       0  344.12   25.61  341.99   41.43  340.09   49.41  339.68    56.6  339.48
   70.68  340.13   78.41  339.37   90.78  339.37   99.48  340.08  101.76  339.24
  101.86  337.58  101.87  337.05  111.26  338.02   111.4  339.23  113.07  339.24
  114.55   339.7   114.6  340.05  140.98  339.07  153.54  339.13  175.09  340.05
  224.48  339.66  233.43  340.29  272.77  340.03  310.69  340.47  327.95  339.96
  347.21  340.05  352.21   340.5  379.62  340.97  417.22  343.25  422.69     344
#Mann= 3 , 0 , 0
       0      .1       0   99.48    .035       0   111.4     .08       0
#Block Obstruct= 6 ,-1
   137.3  139.05342.1466  214.83  218.71342.9147   60.66   71.88342.8853
  308.26  312.29343.4149  259.38  272.25 343.048       0    1.87347.0369
Bank Sta=99.48,111.4
XS Rating Curve= 0 ,0
Exp/Cntr=0.5,0.3

Type RM Length L Ch R = 1 ,15729.91,23.06,22.01,19.38
XS GIS Cut Line= 6
    -611281.7885   -1046000.8759-611247.89779999   -1045913.8258
    -611243.0385   -1045896.2879    -611241.4543   -1045878.3214
    -611273.2296   -1045770.2109    -611285.8491   -1045607.2642
#Sta/Elev= 30
       0   344.2    5.36  343.93   10.38  341.41   12.22   340.8   34.88  340.79
    34.9  339.36   40.38  339.15    86.3  338.91   97.84  339.94   97.85  337.19
  107.83  337.99  107.89  338.03  107.94  338.63  109.25  338.95  112.92  339.18
  113.68  339.48  124.63  339.37  136.84  338.67  148.48  338.73  164.67  339.97
  212.71  339.75  226.96   340.2  236.88  339.96   300.3   340.2  317.72  339.79
  346.77  339.76  377.88  340.49   383.6  341.02  387.37  342.52  405.77  343.91
#Mann= 3 , 0 , 0
       0      .1       0   97.84    .035       0  109.25     .08       0
#Block Obstruct= 9 ,-1
  125.59  136.26342.0143  142.44  166.88342.0143     191  212.02 342.868
   56.85   77.08342.0844  300.27  334.05343.0232  253.06  265.89343.0455
  353.72  374.44343.1166  170.09  181.11342.9549   234.7  245.66343.0414
Bank Sta=97.84,109.25
XS Rating Curve= 0 ,0
Exp/Cntr=0.3,0.1

Type RM Length L Ch R = 1 ,15707.91,3.89,3.89,3.9
XS GIS Cut Line= 6
    -611297.0154   -1045997.0692-611269.98739999   -1045907.1252
    -611262.9829    -1045890.143    -611257.7215   -1045872.5269
    -611281.2811   -1045780.8493    -611297.0154   -1045616.4002
#Sta/Elev= 30
       0  346.46     .29  346.47     7.4  342.56   11.53  340.63   31.45  340.72
   31.46  339.07   57.35  339.29   68.02  338.94   95.25  338.87   97.93  339.43
   98.03  337.07   101.3  337.03  107.88  337.16  107.95  338.03  108.02  338.39
  115.25  338.84  130.67   338.9  143.77  338.47  159.13  339.67  174.73  339.56
  190.03  339.85  221.21  339.84  238.26  340.07  316.29  339.76  333.17  339.53
  357.76  340.21  371.62  340.94  372.23  340.76  386.69  343.84  390.53   344.3
#Mann= 3 , 0 , 0
       0      .1       0   97.93    .035       0  108.02     .08       0
#Block Obstruct= 6 ,-1
   39.03   57.74342.1694  291.09  330.12342.7108  195.81   209.7342.8094
  151.82  178.41342.3976  137.81  146.51341.7051  230.44  238.06343.0097
Bank Sta=97.93,108.02
XS Rating Curve= 0 ,0
Exp/Cntr=0.3,0.1

Type RM Length L Ch R = 1 ,15704.01,5.49,5.67,5.52
XS GIS Cut Line= 6
    -611300.6086    -1045995.581    -611273.5806   -1045905.6369
-611266.57609999   -1045888.6548    -611261.3147   -1045871.0387
    -611284.8744   -1045779.3611    -611300.6086    -1045614.912
#Sta/Elev= 30
       0  346.44    9.31  341.93   12.04  341.08   12.75  342.14   12.76  340.56
   27.69  340.72   27.71  339.12   53.73  339.25   63.09   338.9   96.92  338.75
   97.39  338.08   97.86  338.22   97.92   336.7   97.99  336.25  102.33  336.09
  107.55  336.22  107.65  336.28  107.66  336.99  107.71  338.56   108.6338.6232
  130.67  338.75  142.36  338.44  157.56  339.58  173.15  339.46  188.47  339.83
  236.17     340  329.33  339.46  368.94  340.58  385.12  344.26  390.53  344.91
#Mann= 3 , 0 , 0
       0      .1       0   96.92    .035       0   108.6     .08       0
#Block Obstruct= 5 ,-1
   35.12   53.83342.1467  288.59  327.61342.6234  193.44  207.33342.8185
  150.16  176.82342.3174  133.64  145.02341.6818
Bank Sta=96.92,108.6
XS Rating Curve= 0 ,0
Exp/Cntr=0.3,0.1

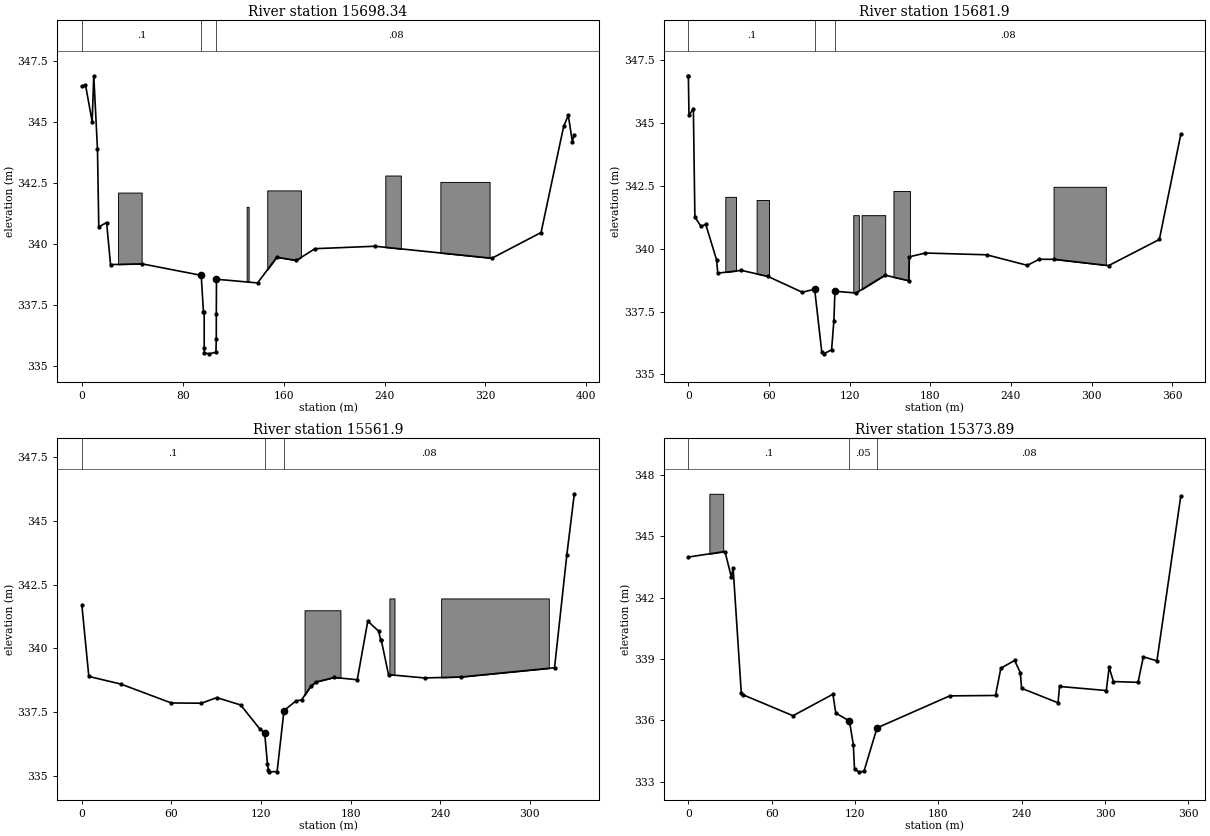
Type RM Length L Ch R = 1 ,15698.34,15.5,16.44,16.98
XS GIS Cut Line= 6
-611305.45039999   -1045992.6441-611278.42249999      -1045902.7
    -611271.4179   -1045885.7179    -611266.1565   -1045868.1018
    -611289.7162   -1045776.4242-611305.45039999   -1045611.9751
#Sta/Elev= 30
       0  346.46    2.89  346.51    8.18     345    9.45  346.88   12.39  343.88
   13.42   340.7   19.64  340.88   22.74  339.16   47.73  339.19   94.65  338.72
   96.42  337.23      97  337.23   97.03  335.75   97.05  335.55  101.17  335.51
  106.33  335.58  106.61  336.13  106.62  337.12  106.77  338.56   139.4  338.41
  154.52  339.46  170.07  339.33  184.92  339.81  232.43  339.91  325.16  339.42
  364.15  340.47  382.07  344.81  385.76  345.26  388.95  344.19  390.53  344.47
#Mann= 3 , 0 , 0
       0      .1       0   94.65    .035       0  106.77     .08       0
#Block Obstruct= 5 ,-1
   28.71   47.42342.1049  284.31  323.33  342.54  240.64  252.95342.8019
     147  173.73342.1931  130.67  132.27  341.52
Bank Sta=94.65,106.77
XS Rating Curve= 0 ,0
Exp/Cntr=0.3,0.1

Type RM Length L Ch R = 1 ,15681.9 ,45.84,50,51.56
XS GIS Cut Line= 4
-611311.56309999   -1045988.0799    -611292.5808   -1045894.7576
-611286.29859999   -1045878.4296-611316.05409999   -1045626.6029
#Sta/Elev= 30
       0  346.88     .04  346.88     .49  345.31    3.76  345.57    4.88  341.26
    9.43  340.89   12.96  340.97   21.06  339.55   21.88  339.03   39.45  339.14
    59.2   338.9   84.71  338.27   93.97  338.39   99.23  335.91  100.76  335.82
  106.56  335.98  108.28  337.14  109.04  338.31  124.79  338.24  146.31  338.95
   163.9  338.73  164.34  339.68  176.38  339.83   221.8  339.76  252.17  339.34
  260.89  339.58  272.13  339.58  312.67  339.33  350.37  340.37  366.31  344.55
#Mann= 3 , 0 , 0
       0      .1       0   93.97    .035       0  109.04     .08       0
#Block Obstruct= 6 ,-1
   27.52   35.49342.0646  271.67  310.54342.4639  152.57  164.87342.2979
    50.8   60.03341.9404  122.69  126.81341.3354  128.89  146.45341.3354
Bank Sta=93.97,109.04
XS Rating Curve= 0 ,0
Exp/Cntr=0.3,0.1

Type RM Length L Ch R = 1 ,15561.9 ,53.46,64.01,67.42
XS GIS Cut Line= 4
    -611358.8707   -1045988.0799    -611405.7524    -1045878.675
    -611406.3202   -1045860.2644    -611458.7895   -1045675.2631
#Sta/Elev= 30
       0   341.7    4.67   338.9   26.16   338.6   59.88  337.86   80.08  337.85
   90.31  338.07  106.36  337.78  119.03  336.85  122.37   336.7  124.27  335.48
  124.95  335.22  125.54  335.16  130.74  335.17  135.33  337.56  143.34  337.94
  147.09  337.98  153.27  338.51  156.65  338.68  168.99  338.86  184.41  338.77
  191.45  341.07  198.78  340.67  200.07  340.32   200.5  340.32  205.32  338.97
  229.63  338.84  253.98  338.88  316.49  339.24  324.73  343.67  329.74  346.06
#Mann= 3 , 0 , 0
       0      .1       0  122.37     .05       0  135.33     .08       0
#Block Obstruct= 3 ,-1
  205.92  209.34341.9575  240.57  312.66341.9575  149.11  173.16341.4943
Bank Sta=122.37,135.33
XS Rating Curve= 0 ,0
Exp/Cntr=0.3,0.1

Type RM Length L Ch R = 1 ,15373.89,10.94,373.89,55.99
XS GIS Cut Line= 4
    -611518.3532   -1046080.6446    -611558.4674   -1045974.2846
    -611559.0168   -1045956.5783    -611651.2961   -1045753.4009
#Sta/Elev= 30
       0  343.98   26.39  344.25   30.94  343.01   32.25  343.44   38.14  337.33
   39.14  337.26   75.35  336.23  104.09  337.28  106.16  336.36  115.99335.9734
  118.79  334.82  119.65  333.61  122.73  333.49  126.44  333.51  135.86335.6363
  188.19   337.2  221.15  337.22     225  338.55  234.88  338.93  238.98  338.34
  239.94  337.57  266.18  336.86  267.23  337.66  300.91  337.46  302.96  338.59
  306.04   337.9  323.77  337.86  327.58  339.11  337.36  338.91  354.54  346.96
#Mann= 3 , 0 , 0
       0      .1       0  115.99     .05       0  135.86     .08       0
#Block Obstruct= 1 ,-1
   15.15   25.12347.0693
Bank Sta=115.99,135.86
XS Rating Curve= 0 ,0
Exp/Cntr=0.3,0.1
LCMann Table=0

--- PPO_Kvasiny_efektiv.g08 (geometry) ---

Geom Title=S-Q20
Program Version=5.03

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
River Reach=Bela            ,Bela_reach

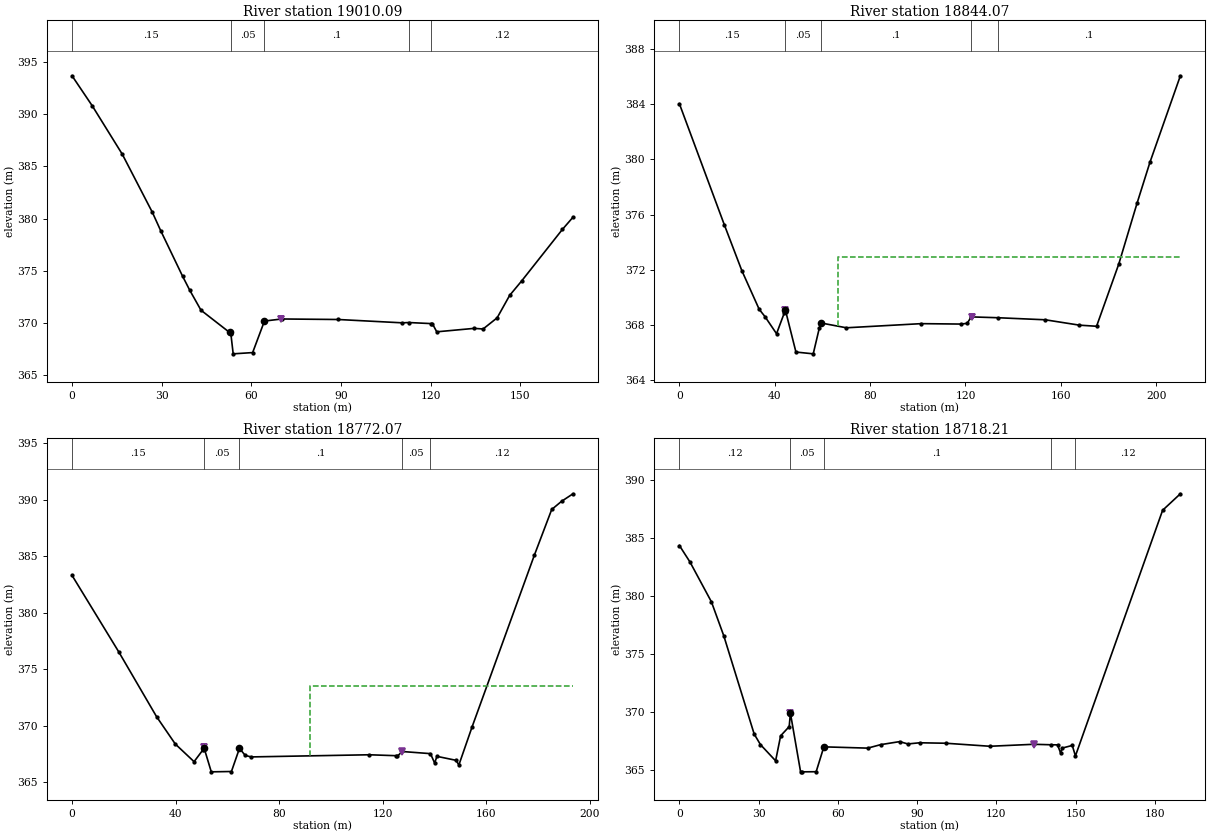
Type RM Length L Ch R = 1 ,19010.09,63.81,66.01,58.86
XS GIS Cut Line= 5
-608502.66209999   -1044593.6857    -608536.6251   -1044560.8986
     -608549.118   -1044545.2805    -608586.5786   -1044508.0775
     -608607.896   -1044465.4426
#Sta/Elev= 27
       0  393.68    6.75  390.81   16.83  386.16    26.9  380.59   29.66  378.85
   36.98  374.49   39.39  373.14   43.16  371.22   52.73  369.09   53.15 368.985
   53.94  367.04   60.45  367.16    64.4370.1805   70.18  370.38   89.09  370.33
   110.6  370.01  112.68  370.04     120  369.94  120.58  369.94  122.07  369.15
  134.59  369.48  137.58  369.42  142.28  370.49  146.47  372.64  150.45  374.01
  164.12  378.96  167.67  380.13
#Mann= 5 ,-1 , 0
       0     .15       0   53.15     .05       0    64.4      .1       0
  112.68     .05       0     120     .12       0
Levee=0,,,-1,69.94,370.38,,
Bank Sta=52.73,64.4
XS Rating Curve= 0 ,0
Exp/Cntr=0.3,0.1

Type RM Length L Ch R = 1 ,18844.07,72.16,72,73.34
XS GIS Cut Line= 6
-608649.34349999   -1044712.1427    -608661.1943   -1044671.2681
    -608666.6842   -1044652.0363-608687.57959999     -1044587.96
    -608711.2657   -1044551.4157    -608740.0273   -1044528.7448
#Sta/Elev= 27
       0  384.04   18.89  375.24   26.18  371.94   33.47  369.13    35.9   368.6
   40.75  367.36   44.03  368.88   44.35  369.09   44.67  368.93   48.88  366.03
   56.14   365.9   58.65  367.74   59.34  368.14   59.46368.1367   70.03  367.79
  101.43  368.09     118  368.06  120.69  368.11  122.41  368.58  133.48  368.52
  153.46  368.37  167.81  367.98  174.98   367.9  184.29  372.41  191.95  376.82
  197.36  379.79  210.13  386.07
#Mann= 5 ,-1 , 0
       0     .15       0   44.35     .05       0   59.46      .1       0
  122.41     .05       0  133.48      .1       0
Levee=-1,44.3,369.1,-1,122.55,368.54,,
#XS Ineff= 2 , 0
                            66.4           372.9
Permanent Ineff=
       F       F
Bank Sta=44.35,59.46
XS Rating Curve= 0 ,0
Exp/Cntr=0.3,0.1

Type RM Length L Ch R = 1 ,18772.07,49.5,53.87,46.34
XS GIS Cut Line= 5
-608717.01799999   -1044739.5508    -608729.3973    -1044693.413
    -608735.3242   -1044674.3114    -608762.3599   -1044598.1112
    -608783.6774   -1044558.5216
#Sta/Elev= 27
       0  383.29   18.17  376.48   32.67  370.79   39.91  368.37   47.16  366.81
   50.67  367.88   50.91  368.11   50.99368.0506   53.81  365.91    61.6  365.94
    64.7367.9844   66.95  367.36   69.23  367.23  114.85  367.42     125  367.34
  125.72  367.28   127.5  367.71  138.51  367.52  140.12  366.69  141.02  367.28
  148.38  366.93  149.49  366.52  154.63  369.91  178.71  385.11  185.36  389.12
  189.15  389.84  193.59  390.51
#Mann= 5 ,-1 , 0
       0     .15       0   50.99     .05       0    64.7      .1       0
   127.5     .05       0  138.51     .12       0
Levee=-1,50.87,368.11,-1,127.37,367.79,,
#XS Ineff= 2 , 0
                            91.8          373.46
Permanent Ineff=
       F       F
Bank Sta=50.99,64.7
XS Rating Curve= 0 ,0
Exp/Cntr=0.3,0.1

Type RM Length L Ch R = 1 ,18718.21,29.06,21.79,6.52
XS GIS Cut Line= 5
-608753.54699999   -1044753.4637     -608781.487   -1044705.5211
    -608789.4245   -1044670.2786    -608798.9496    -1044622.336
-608821.80959999   -1044578.8384
#Sta/Elev= 30
       0  384.35    4.01  382.93   12.11  379.51   16.79  376.59   28.31  368.13
   30.69  367.22   36.42  365.83   38.32  367.98   41.56  368.77   42.02  369.93
   45.86   364.9   46.37  364.88   51.77  364.89   54.68  367.03   71.29  366.92
    76.2  367.22   83.37  367.48   86.48  367.28   90.94  367.38  100.86  367.34
  117.53  367.08  134.11  367.25  140.49  367.21  143.13   367.2  144.27  366.52
  144.99  366.93  148.71  367.15  149.91  366.25  182.91  387.38  189.63   388.8
#Mann= 5 ,-1 , 0
       0     .12       0   42.02     .05       0   54.68      .1       0
  140.49     .05       0  149.91     .12       0
Levee=-1,42.02,369.93,-1,134.06,367.22,,
Bank Sta=42.02,54.68
XS Rating Curve= 0 ,0
Exp/Cntr=0.3,0.1