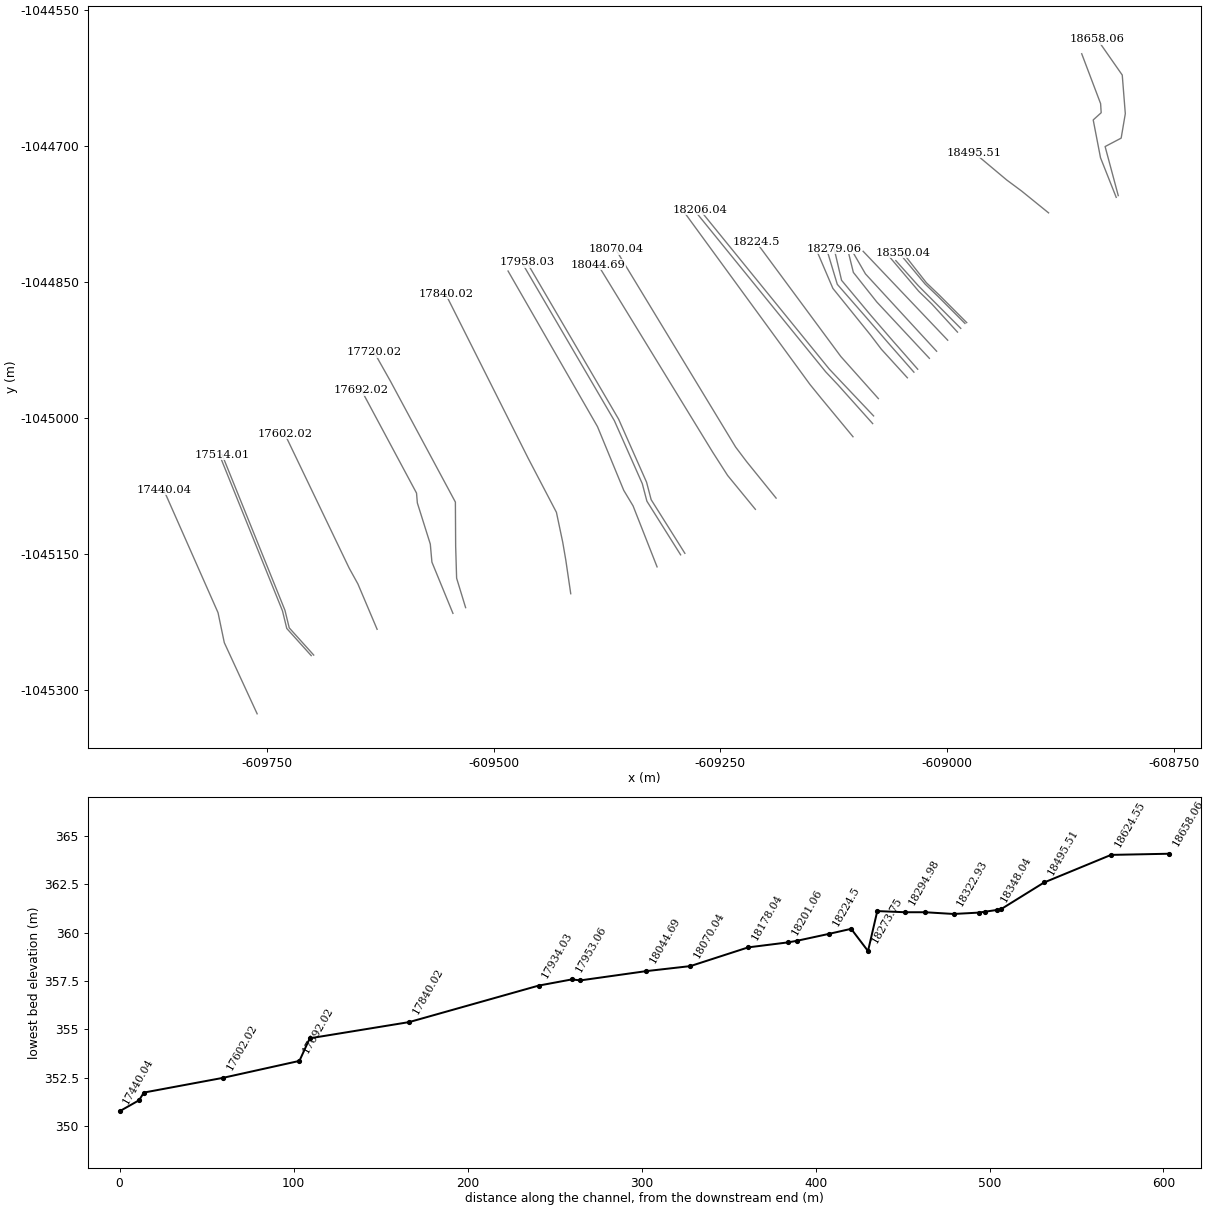
HEC-RAS study PPO_Kvasiny_efektiv.prj: PPO_Kvasiny_efektivita

--- PPO_Kvasiny_efektiv.g08 (geometry) --- (continued)

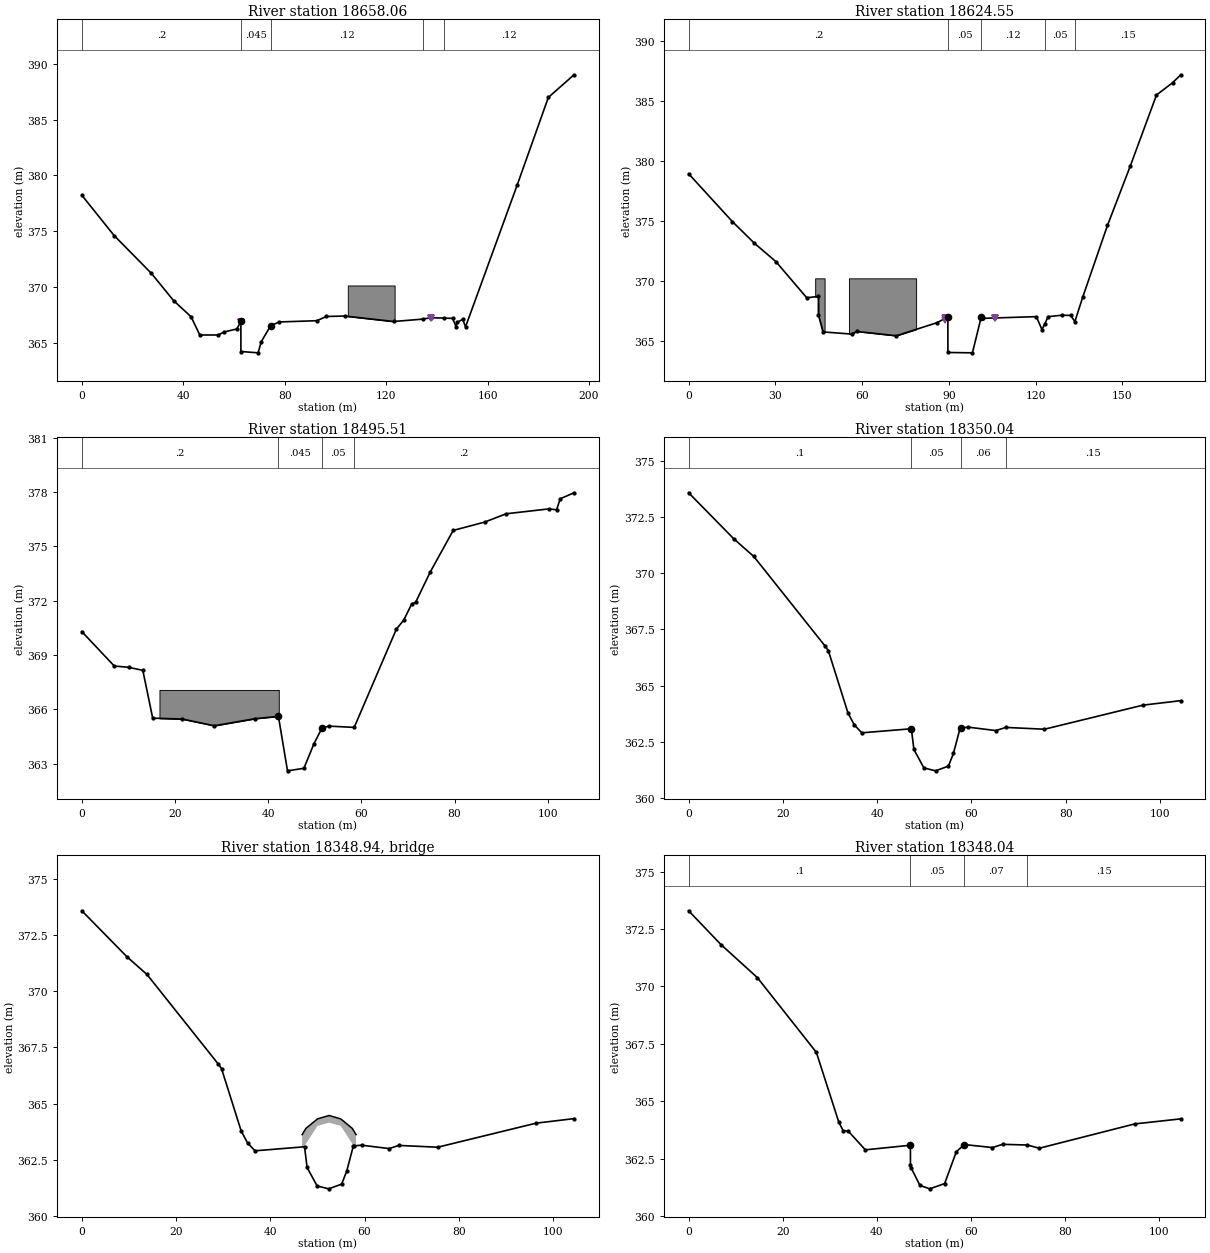
Type RM Length L Ch R = 1 ,18658.06,22,33.51,26.87
XS GIS Cut Line= 6
-608811.08549999    -1044755.116     -608825.589   -1044701.0257
    -608807.8792   -1044691.7325-608803.30299999   -1044664.7705
    -608806.6867   -1044622.1356-608834.09479999   -1044582.8844
#Sta/Elev= 30
       0  378.22   12.72  374.61   27.41  371.22   36.15  368.78    43.1  367.32
    46.5  365.69   53.84  365.69   56.09  365.96   61.11  366.23   62.71   366.9
   62.73  364.21   69.51  364.09   70.75  365.09   74.46366.5206   77.86  366.86
   92.64  366.97   96.45  367.35  103.66  367.39  122.92   366.9  134.34  367.11
  137.58  367.24   142.8367.2064  146.19  367.18  147.55  366.45  148.03  366.83
  150.17  367.09  151.31  366.42  171.67  379.13  183.96  386.99  194.08  389.02
#Mann= 5 ,-1 , 0
       0      .2       0   62.71    .045       0   74.46     .12       0
  134.34     .05       0   142.8     .12       0
Levee=-1,62.62,366.83,-1,137.53,367.18,,
#Block Obstruct= 1 ,-1
  104.88  123.34370.1295
Bank Sta=62.71,74.46
XS Rating Curve= 0 ,0
Exp/Cntr=0.3,0.1

Type RM Length L Ch R = 1 ,18624.55,27.54,38.49,47.2
XS GIS Cut Line= 6
    -608813.3292   -1044757.0751-608830.65819999   -1044713.3605
     -608838.708   -1044671.6675    -608829.9133   -1044663.7088
    -608830.5483   -1044653.6758    -608851.3869   -1044598.6741
#Sta/Elev= 30
       0  378.92   15.14  374.94   22.67  373.16    30.2  371.61   40.84  368.61
   44.87  368.72   44.88  367.19   46.46  365.77   56.35  365.59   58.15  365.81
   71.85  365.45   85.93  366.54   89.66  367.02   89.67  364.06   98.15  364.03
   101.2  367.01  101.96   366.9  120.26  367.04  122.19  365.97  123.18  366.43
  124.31  367.04  129.18  367.16  132.12  367.14  133.58  366.63  136.31  368.67
  144.85  374.62  152.76  379.57  161.81  385.47  167.38  386.49  170.22  387.15
#Mann= 5 ,-1 , 0
       0      .2       0   89.66     .05       0   101.2     .12       0
  123.18     .05       0  133.58     .15       0
Levee=-1,88.75,366.79,-1,105.8,366.93,,
#Block Obstruct= 2 ,-1
   43.76   47.02 370.226   55.44   78.67 370.226
Bank Sta=89.66,101.2
XS Rating Curve= 0 ,0
Exp/Cntr=0.3,0.1

Type RM Length L Ch R = 1 ,18495.51,25.6,24.88,23.57
XS GIS Cut Line= 4
    -608887.9529   -1044774.1613    -608917.6792   -1044750.0879
    -608934.0835    -1044737.917    -608970.0669   -1044707.7544
#Sta/Elev= 27
       0  370.29    6.96  368.39   10.03  368.32   13.09  368.15   15.21  365.51
   21.57  365.46   28.43  365.09   37.14  365.48   42.19  365.61   44.14   362.6
   47.66  362.74   49.82   364.1   51.54  364.96   53.01  365.07   58.45     365
   67.51  370.43    69.1  370.93    70.8  371.82   71.62   371.9   74.81   373.6
    79.7  375.88   86.45  376.34   91.06   376.8  100.25  377.07  101.89  377.02
  102.68  377.63  105.63  377.96
#Mann= 4 ,-1 , 0
       0      .2       0   42.19    .045       0   51.54     .05       0
   58.45      .2       0
#Block Obstruct= 1 ,-1
   16.66   42.27367.0693
Bank Sta=42.19,51.54
XS Rating Curve= 0 ,0
Exp/Cntr=0.3,0.1

Type RM Length L Ch R = 1 ,18350.04,2,2,2.21
XS GIS Cut Line= 4
    -608978.2241   -1044895.2065    -609008.2817   -1044865.0536
-609022.72899999   -1044851.2234-609048.56549999   -1044818.2857
#Sta/Elev= 22
       0  373.57     9.6  371.52   13.82  370.74   28.98  366.75   29.65  366.55
    33.8  363.79   35.16  363.25   36.75   362.9   47.26  363.08    47.8  362.16
   49.92  361.34   52.39  361.21   55.13  361.42    56.2  361.99   57.62  363.12
   57.71  363.12   59.38  363.15    65.2     363    67.3  363.14   75.51  363.06
   96.41  364.13  104.44  364.33
#Mann= 4 ,-1 , 0
       0      .1       0   47.26     .05       0   57.71     .06       0
    67.3     .15       0
Bank Sta=47.26,57.71
XS Rating Curve= 0 ,0
Exp/Cntr=0.5,0.3

Type RM Length L Ch R = 3 ,18348.94,,,
BEGIN DESCRIPTION:
NOVE NAVRHOVANA LAVKA
END DESCRIPTION:
Bridge Culvert--1,0,-1,-1, 0
Deck Dist Width WeirC Skew NumUp NumDn MinLoCord MaxHiCord MaxSubmerge Is_Ogee
0.2,1.5,1.4,0, 7, 7, , , 0.98, 0, 0,0,,
   46.75   47.56   50.02   52.47   54.93   57.38   58.19
  363.62   363.9  364.32  364.47  364.32   363.9  363.62
       0  363.22  364.01  364.15  364.01  363.22       0
    46.3   47.11   49.57   52.02   54.48   56.93   57.74
  363.62   363.9  364.32  364.47  364.32   363.9  363.62
       0  363.22  364.01  364.15  364.01  363.22       0
BR Coef=-1 , 0 , 0 ,, 0 ,,,0.8,-1,,0,
WSPro=,,,, 1 ,,,, 0 ,,,, 0 ,,,,-1 ,-1 ,-1 , 0 , 0 , 0 , 0 , 0
BC Design=,, 0 ,, 0 ,,,,,,
BC Use User HTab Curves=0
BC User HTab FreeFlow(D)= 0

Type RM Length L Ch R = 1 ,18348.04,7.11,6.87,7.11
XS GIS Cut Line= 4
    -608980.1664   -1044896.0904     -609009.671   -1044866.4922
-609024.11829999    -1044852.662-609051.48649999   -1044819.8097
#Sta/Elev= 22
       0   373.3    6.85  371.83   14.58  370.39   27.13  367.13   31.91  364.08
   32.82  363.72   33.93  363.69   37.54  362.88   47.11  363.08   47.12  362.22
    47.3  362.08   49.13  361.33   51.22  361.18   54.38  361.41   56.87   362.8
   58.56  363.11   64.54  362.98   66.68  363.12   71.95  363.09   74.49  362.95
   94.77  364.01  104.55  364.23
#Mann= 4 ,-1 , 0
       0      .1       0   47.11     .05       0   58.56     .07       0
   71.95     .15       0
Bank Sta=47.11,58.56
XS Rating Curve= 0 ,0
Exp/Cntr=0.5,0.3

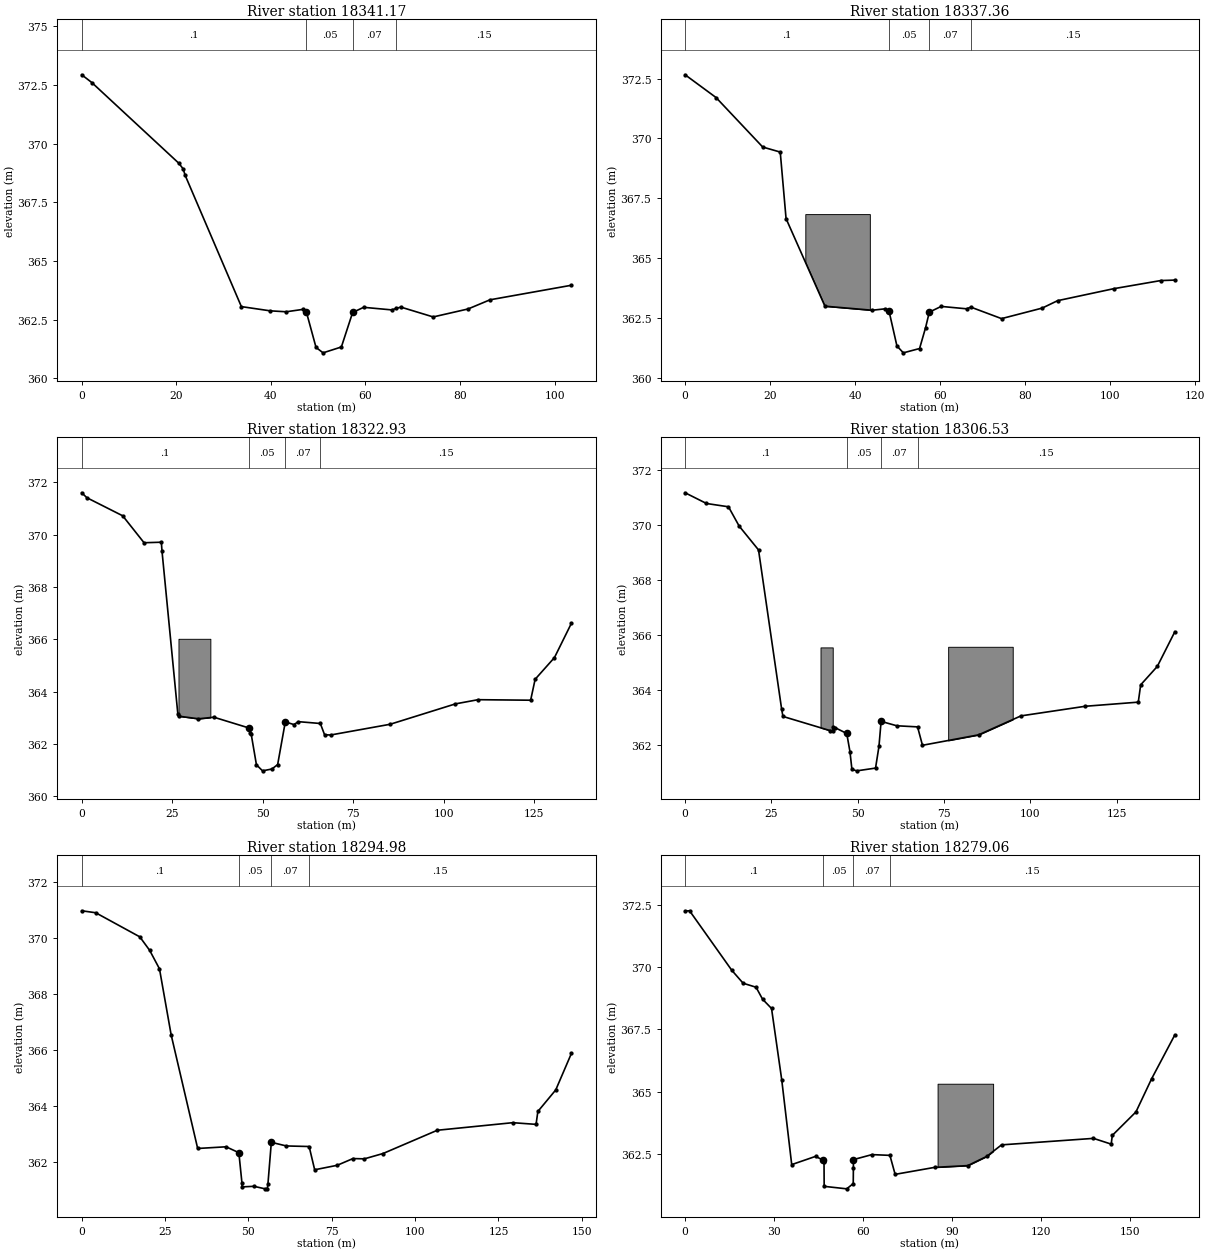
Type RM Length L Ch R = 1 ,18341.17,3.64,3.82,3.48
XS GIS Cut Line= 3
    -608984.7855   -1044901.5539    -609031.6963   -1044854.4518
    -609056.4353   -1044826.8159
#Sta/Elev= 22
       0  372.94    2.13  372.61   20.54  369.17   21.45  368.93   21.89  368.65
   33.77  363.06   39.86  362.88   43.25  362.84   46.71  362.94   47.49  362.85
   49.56  361.32   51.05  361.09   54.92  361.34    57.3  362.81   59.63  363.03
   65.57  362.92   66.48  362.98   67.49  363.04   74.34  362.62   81.72  362.96
   86.35  363.35  103.57  363.97
#Mann= 4 ,-1 , 0
       0      .1       0   47.49     .05       0    57.3     .07       0
   66.48     .15       0
Bank Sta=47.49,57.3
XS Rating Curve= 0 ,0
Exp/Cntr=0.3,0.1

Type RM Length L Ch R = 1 ,18337.36,14.84,14.42,14.55
XS GIS Cut Line= 4
     -608988.397   -1044905.6744    -609016.6957   -1044874.6581
-609031.05539999   -1044860.7368-609065.50409999   -1044820.1635
#Sta/Elev= 23
       0  372.66    7.27  371.71   18.26  369.64   22.38  369.43   23.75  366.65
   32.89  362.99   44.01  362.82   47.08  362.88   47.98  362.78   49.83  361.33
   51.34  361.04   55.16  361.22   56.57  362.09   57.45  362.74   60.24  362.98
   66.23  362.88   67.23  362.95   74.45  362.47   84.01  362.91   87.64  363.22
  100.82  363.72  111.88  364.06  115.21  364.08
#Mann= 4 ,-1 , 0
       0      .1       0   47.98     .05       0   57.45     .07       0
   67.23     .15       0
#Block Obstruct= 1 ,-1
   28.28   43.46366.8377
Bank Sta=47.98,57.45
XS Rating Curve= 0 ,0
Exp/Cntr=0.3,0.1

Type RM Length L Ch R = 1 ,18322.93,16.56,16.4,16.08
XS GIS Cut Line= 2
    -608999.2052   -1044914.5843-609092.44469999   -1044816.5633
#Sta/Elev= 30
       0   371.6    1.44  371.41   11.32  370.72   17.22  369.69      22  369.71
   22.18  369.37   26.56  363.14   26.79  363.06   32.25  362.96   36.52  363.02
   46.17  362.61   46.51  362.42    46.8  362.39   48.27   361.2   49.96  360.97
   52.55  361.04   54.13  361.21   56.24  362.84   58.62  362.74   59.86  362.85
   65.92  362.78   67.09  362.35   68.75  362.34    85.2  362.75  103.25  363.53
   109.5  363.69  124.02  363.67  125.26  364.47   130.6   365.3  135.28  366.61
#Mann= 4 ,-1 , 0
       0      .1       0   46.17     .05       0   56.24     .07       0
   65.92     .15       0
#Block Obstruct= 1 ,-1
   26.73   35.54366.0181
Bank Sta=46.17,56.24
XS Rating Curve= 0 ,0
Exp/Cntr=0.3,0.1

Type RM Length L Ch R = 1 ,18306.53,11.47,11.55,11.69
XS GIS Cut Line= 3
-609011.42359999   -1044926.7722     -609089.892   -1044841.4859
-609102.89469999   -1044819.0525
#Sta/Elev= 28
       0  371.18    6.19  370.79   12.56  370.67   15.64  369.97   21.26   369.1
   27.95  363.31   28.33  363.04    42.1  362.52   42.75  362.52   42.97  362.64
   43.45  362.63   46.81  362.42   47.74  361.76   48.31  361.11   49.74  361.06
   55.15  361.16   56.14  361.95   56.76  362.86   61.31   362.7   67.32  362.66
   68.74  361.99   85.01  362.37   97.26  363.06  115.89  363.41  131.24  363.56
  131.94  364.19  136.75  364.86  141.82  366.12
#Mann= 4 ,-1 , 0
       0      .1       0   46.81     .05       0   56.76     .07       0
   67.32     .15       0
#Block Obstruct= 2 ,-1
   39.21   42.75365.5524   76.18   94.88 365.575
Bank Sta=46.81,56.76
XS Rating Curve= 0 ,0
Exp/Cntr=0.3,0.1

Type RM Length L Ch R = 1 ,18294.98,16.32,15.92,15.19
XS GIS Cut Line= 4
    -609019.4125   -1044934.5905    -609077.4164   -1044872.4435
    -609103.2397   -1044839.8467    -609108.1081   -1044820.1617
#Sta/Elev= 29
       0  370.98    4.19  370.91   17.42  370.05   20.37  369.57   23.32  368.91
   26.83  366.55   34.78   362.5    43.3  362.56   47.13  362.35   48.05  361.28
    48.1  361.13   51.66  361.15   55.02  361.06   55.67  361.07   55.85  361.23
   56.87  362.72   61.37  362.59   68.21  362.57   69.87  361.74   76.63   361.9
   81.35  362.14   84.78  362.13   90.37  362.32  106.65  363.15  129.28  363.42
  136.27  363.36  136.81  363.82  142.18  364.59  146.87  365.89
#Mann= 4 ,-1 , 0
       0      .1       0   47.13     .05       0   56.87     .07       0
   68.21     .15       0
Bank Sta=47.13,56.87
XS Rating Curve= 0 ,0
Exp/Cntr=0.3,0.1

Type RM Length L Ch R = 1 ,18279.06,5.31,5.32,5.33
BEGIN DESCRIPTION:
PETRUV JEZ (NADJEZI)
END DESCRIPTION:
XS GIS Cut Line= 5
-609032.27279999   -1044946.5812    -609059.4153   -1044915.6818
     -609083.818   -1044887.4375-609116.26419999   -1044848.5425
-609124.47399999   -1044813.5362
#Sta/Elev= 30
       0  372.24     1.5  372.25   15.72  369.87   19.55  369.35   23.91  369.19
   26.11  368.71   29.13  368.34   32.56  365.49   35.93  362.09   43.99  362.42
   46.63  362.26   46.82   362.2   46.87  361.22   54.47  361.12   56.67  361.33
   56.72  361.94   56.73  362.29   62.98  362.49   69.03  362.46   70.79   361.7
   84.14  361.98   95.28  362.05  101.69  362.42  106.65  362.88  137.65  363.14
  143.62  362.91     144  363.26  151.97   364.2  157.22  365.52  165.06  367.28
#Mann= 4 ,-1 , 0
       0      .1       0   46.63     .05       0   56.73     .07       0
   69.03     .15       0
#Block Obstruct= 1 ,-1
    85.1  103.82365.3277
Bank Sta=46.63,56.73
XS Rating Curve= 0 ,0
Exp/Cntr=0.3,0.1

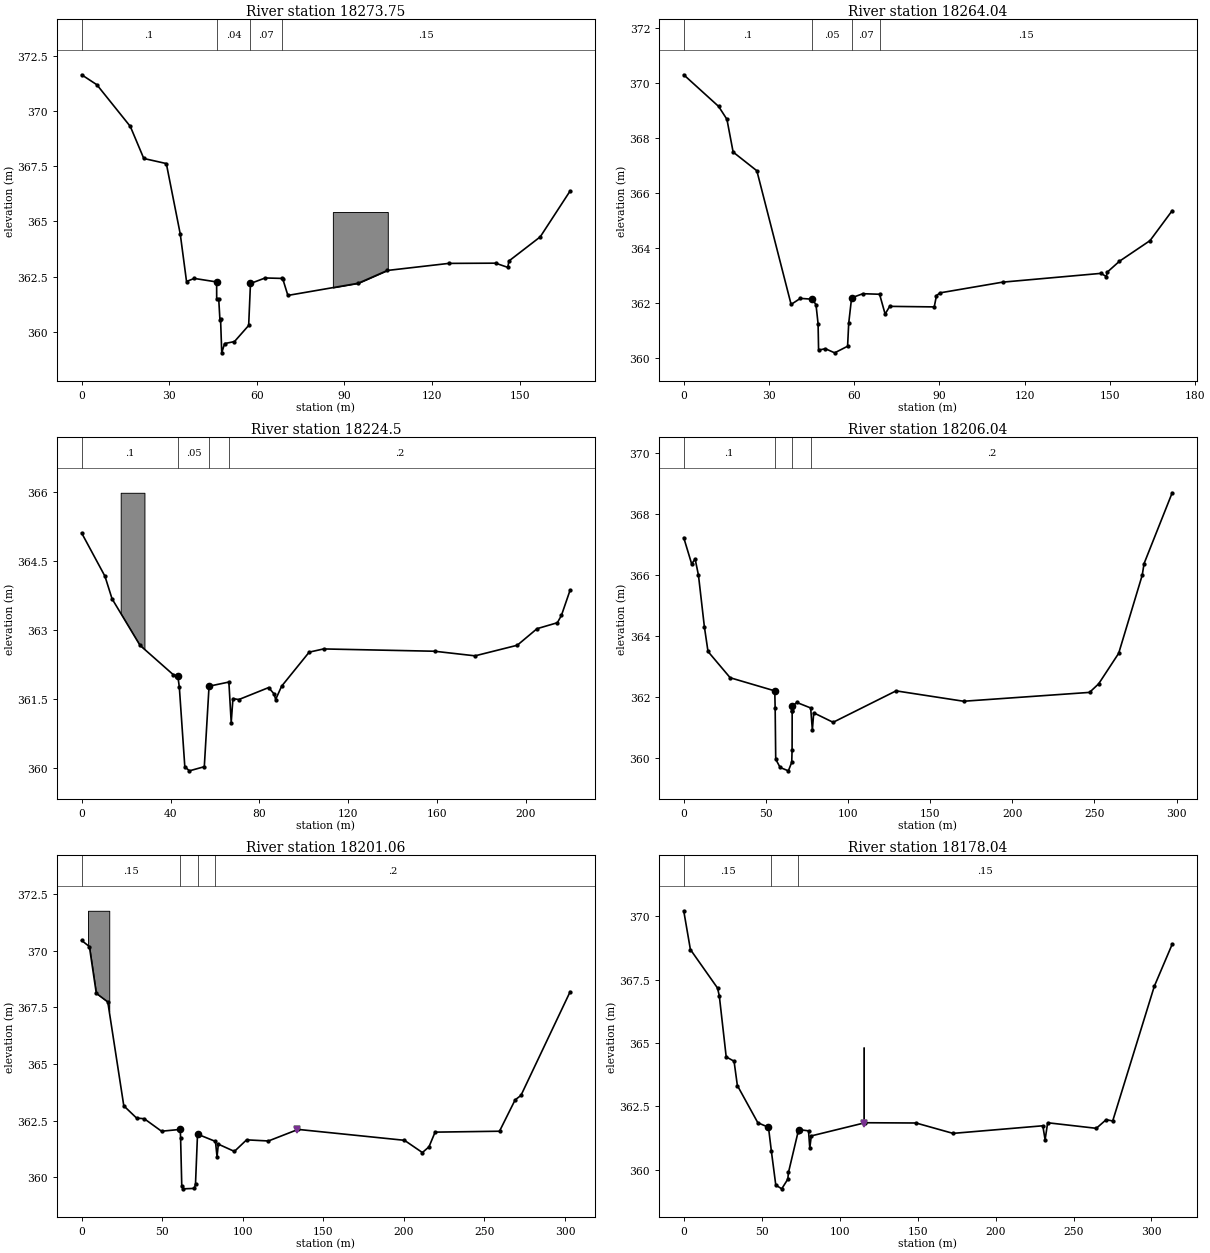
Type RM Length L Ch R = 1 ,18273.75,10.28,9.7,8.84
XS GIS Cut Line= 5
    -609036.4443   -1044949.8598-609064.65399999   -1044917.7456
-609089.05669999   -1044889.5013-609120.98169999   -1044852.9628
    -609132.1506   -1044815.9045
#Sta/Elev= 30
       0  371.64     5.2  371.19   16.67   369.3   21.28  367.85      29  367.62
   33.77  364.43   35.92  362.28   38.55  362.42   46.23  362.26   46.25  361.49
   46.94   361.5   47.36  360.55   47.57   360.6   47.98  359.05   48.96  359.47
   52.34  359.56    57.2  360.29   57.82  362.19   62.85  362.44    68.5  362.42
   68.85  362.41   70.63  361.65   94.71   362.2  104.69  362.78  125.75   363.1
  141.77  363.11  145.94  362.92  146.35  363.21  157.05   364.3   167.3  366.38
#Mann= 4 ,-1 , 0
       0      .1       0   46.23     .04       0   57.82     .07       0
    68.5     .15       0
#Block Obstruct= 1 ,-1
   86.04  104.85365.4245
Bank Sta=46.23,57.82
XS Rating Curve= 0 ,0
Exp/Cntr=0.3,0.1

Type RM Length L Ch R = 1 ,18264.04,12.48,12.71,12.7
XS GIS Cut Line= 5
    -609043.6799   -1044956.0504    -609072.4114   -1044924.5346
-609084.51969999   -1044908.6165    -609125.8273   -1044857.4816
-609142.94559999   -1044817.4285
#Sta/Elev= 30
       0  370.31   12.28  369.16   15.21  368.69   17.39   367.5   25.74  366.82
    37.8  361.96   41.05  362.18   45.27  362.15   46.56  361.95   47.29  361.26
   47.47   360.3   49.85  360.35   53.13   360.2   57.68  360.44   58.07  361.27
   59.09   362.2   63.06  362.35   68.94  362.33   70.89  361.61    72.5  361.89
   88.18  361.87   88.96  362.28   90.18  362.38  112.24  362.77  146.92  363.09
  148.75  362.97  149.04  363.13  153.37  363.53  164.13  364.28  171.94  365.37
#Mann= 4 ,-1 , 0
       0      .1       0   45.27     .05       0   59.09     .07       0
   68.94     .15       0
Bank Sta=45.27,59.09
XS Rating Curve= 0 ,0
Exp/Cntr=0.3,0.1

Type RM Length L Ch R = 1 ,18224.5 ,18.07,18.46,18.77
XS GIS Cut Line= 3
    -609075.6612   -1044979.0075    -609117.0775    -1044932.579
-609210.79199999   -1044805.8233
#Sta/Elev= 28
       0  365.11   10.49  364.17   13.68  363.68   26.24  362.67   41.24  362.03
   43.28     362   43.96  361.76   46.43  360.03   48.49  359.94    55.2  360.03
   57.34  361.78   66.26  361.87   67.31  360.99   68.09  361.51   70.76  361.49
   84.16  361.75   86.64  361.61    87.3  361.49      90  361.78   102.4  362.52
  108.88  362.59  158.83  362.54  177.06  362.44  196.05  362.67  204.95  363.03
  214.11  363.16  215.94  363.32  219.85  363.87
#Mann= 4 ,-1 , 0
       0      .1       0   43.28     .05       0   57.34     .07       0
   66.26      .2       0
#Block Obstruct= 1 ,-1
   17.57   28.26365.9847
Bank Sta=43.28,57.34
XS Rating Curve= 0 ,0
Exp/Cntr=0.3,0.1

Type RM Length L Ch R = 1 ,18206.04,5.09,4.98,4.99
XS GIS Cut Line= 4
     -609080.951    -1044998.105    -609116.2027    -1044960.872
    -609129.9171   -1044946.3148-609272.49179999   -1044770.8857
#Sta/Elev= 30
       0  367.22    4.83  366.36    6.94  366.52    8.97  365.99   12.57   364.3
   14.78  363.49   28.27  362.63   55.41   362.2   55.65  361.65      56  359.96
    58.7  359.69   63.69  359.58   65.74  359.86   65.96  360.26   66.01  361.53
   66.11  361.55   66.12   361.7   68.84  361.82   77.27  361.64    78.3  360.92
   79.13  361.48   90.93  361.17  129.25   362.2  170.35  361.86     247  362.15
  252.55  362.43  264.74  363.43  279.08  365.99   280.2  366.37  297.33  368.69
#Mann= 4 ,-1 , 0
       0      .1       0   55.41     .05       0   66.12     .07       0
   77.27      .2       0
Bank Sta=55.41,66.12
XS Rating Curve= 0 ,0
Exp/Cntr=0.5,0.3

Type RM Length L Ch R = 1 ,18201.06,23.86,23.02,22.09
XS GIS Cut Line= 4
     -609081.967   -1045006.5717-609120.09479999    -1044964.001
    -609133.8092   -1044949.4436    -609276.3839   -1044774.0146
#Sta/Elev= 30
       0  370.45     4.8  370.18    9.09  368.12   16.22  367.74   26.16  363.16
    34.1  362.62   38.88  362.59   49.59  362.04   61.21  362.12   61.43  361.72
   62.15  359.61   63.21   359.5   70.02  359.52   70.68  359.73   71.92  361.91
   83.07  361.59   84.04  360.91   84.84  361.47   94.82  361.15  102.39  361.66
  115.93  361.61  134.35  362.12  200.36  361.64   211.5   361.1  215.58  361.35
  219.39     362  259.37  362.04  269.05  363.42  272.69  363.62  303.21  368.19
#Mann= 4 ,-1 , 0
       0     .15       0   61.21     .05       0   71.92     .07       0
   83.07      .2       0
Levee=0,,,-1,133.77,362.12,,
#Block Obstruct= 1 ,-1
    3.93   17.13371.7588
Bank Sta=61.21,71.92
XS Rating Curve= 0 ,0
Exp/Cntr=0.5,0.3

Type RM Length L Ch R = 1 ,18178.04,32.9,33.23,33.2
XS GIS Cut Line= 4
    -609103.6508   -1045021.0811-609138.55079999   -1044978.8772
    -609151.1605   -1044963.3531    -609291.7859   -1044770.6855
#Sta/Elev= 30
       0  370.22    4.28  368.69   21.67  367.17   22.82  366.86   27.24  364.45
   32.28  364.28    34.4  363.32   47.53  361.85   54.36  361.67   56.22360.7247
   59.04  359.39   62.85  359.24   66.74  359.62   67.19  359.89   73.29 361.474
   73.82  361.58   80.03  361.53   80.86  360.85   81.81  361.33  116.27  361.85
  148.98  361.84   172.7  361.43   230.3  361.73  231.77  361.18  233.41  361.85
   264.6  361.63  270.94  361.97  275.13  361.92  301.82  367.24  313.29   368.9
#Mann= 3 ,-1 , 0
       0     .15       0   56.22     .05       0   73.29     .15       0
Levee=0,,,-1,115.79,361.81,,
#Block Obstruct= 1 ,-1
  115.17  115.55 364.834
Bank Sta=54.36,73.82
XS Rating Curve= 0 ,0
Exp/Cntr=0.3,0.1

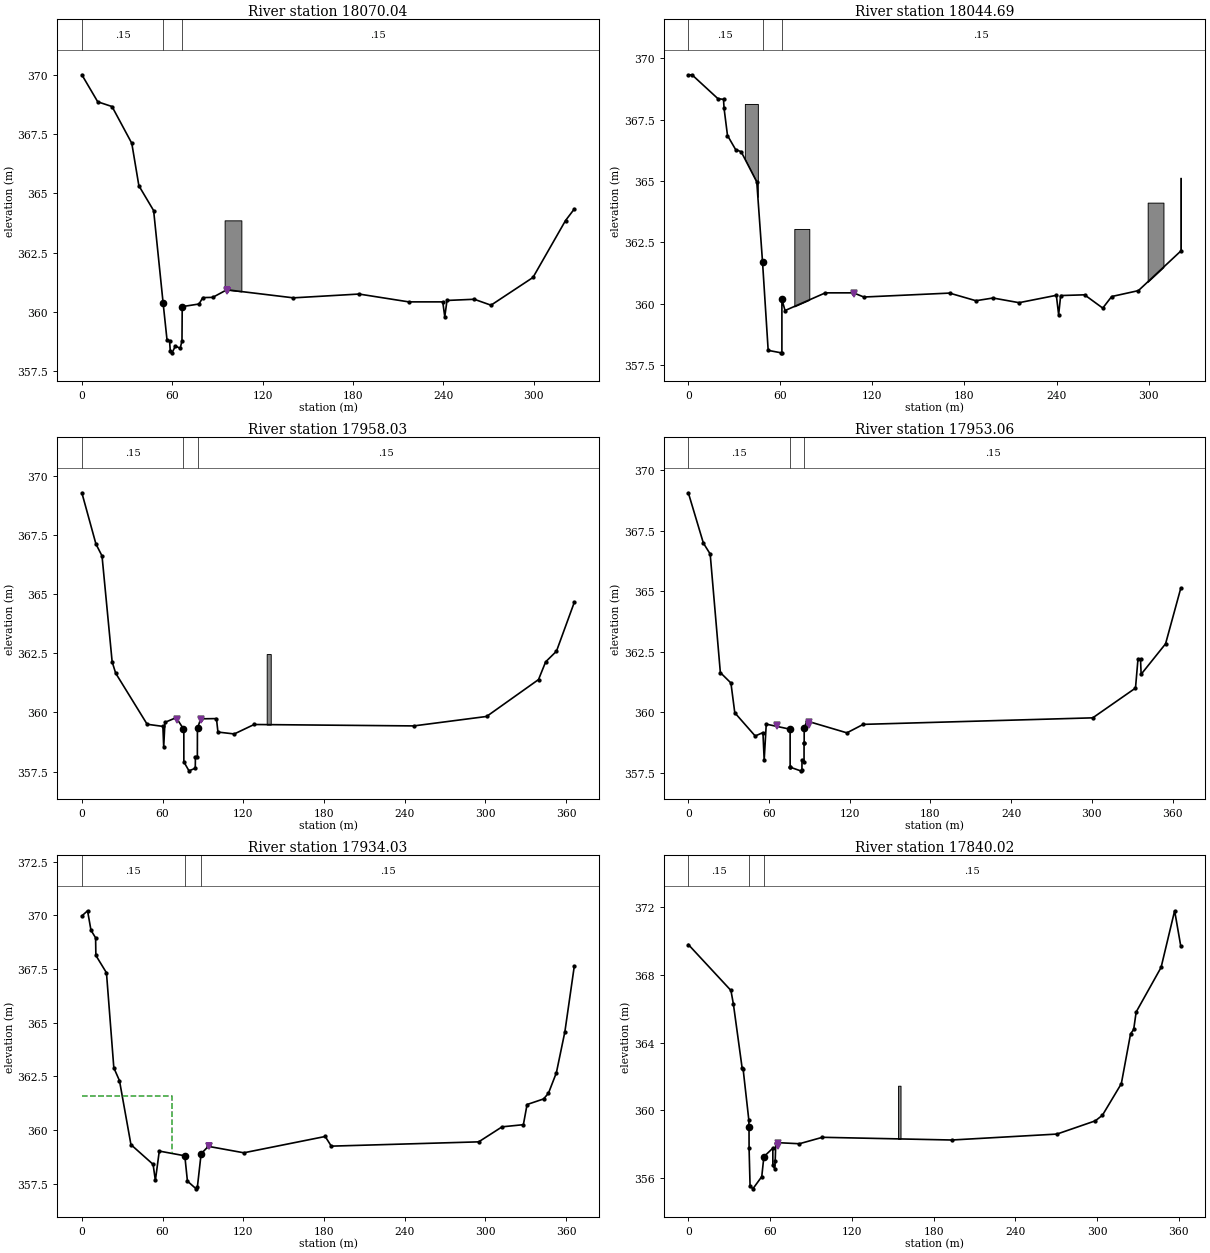
Type RM Length L Ch R = 1 ,18070.04,26.03,25.34,24.56
XS GIS Cut Line= 4
    -609188.4695   -1045088.7556-609221.08839999   -1045048.4074
    -609233.1209    -1045032.432    -609365.3255   -1044814.4483
#Sta/Elev= 30
       0     370   10.54  368.86   20.03  368.66   33.14  367.11   37.84  365.32
   47.64  364.27    53.9360.3909   56.53  358.81   58.19  358.78    58.7  358.34
   59.86  358.27   62.11  358.56   65.23  358.46   66.45  358.77   66.61  360.22
   77.76  360.33   80.25   360.6   86.85  360.61   96.19  360.93  140.38  360.59
  183.97  360.75  216.94  360.42  239.52  360.42  240.85  359.79  242.33  360.48
  260.41  360.53  271.53  360.28  299.39  361.45  320.98  363.85  326.83  364.34
#Mann= 3 ,-1 , 0
       0     .15       0    53.9     .05       0   66.61     .15       0
Levee=0,,,-1,96.59,360.86,,
#Block Obstruct= 1 ,-1
   94.75  105.86363.8593
Bank Sta=53.9,66.61
XS Rating Curve= 0 ,0
Exp/Cntr=0.3,0.1

Type RM Length L Ch R = 1 ,18044.69,39.68,37.85,34.98
XS GIS Cut Line= 4
    -609211.3246   -1045101.1375    -609241.9703   -1045063.7315
    -609258.5068   -1045037.9345    -609384.8456   -1044831.5591
#Sta/Elev= 30
       0  369.31    2.39  369.32   19.27  368.35   22.94  368.32   23.29  367.96
   25.53  366.85   30.81  366.28   34.45  366.19   44.62  364.96   48.36  361.71
   52.05  358.11   60.57  358.01   60.99  358.01      61  360.18   63.04  359.73
   89.32  360.45  107.65  360.45   114.4  360.28  170.26  360.44  187.43  360.13
  198.58  360.24  215.58  360.05  239.86  360.35  241.36  359.56  242.68  360.34
  258.25  360.37  270.11  359.83  275.91   360.3  293.32  360.54  320.97  362.15
#Mann= 3 , 0 , 0
       0     .15       0   48.36     .05       0      61     .15       0
Levee=0,,,-1,107.71,360.41,,
#Block Obstruct= 4 ,-1
   69.09   78.84363.0494   36.85   45.32 368.134  320.66  320.97365.1357
  299.39  309.67364.1195
Bank Sta=48.36,61
XS Rating Curve= 0 ,0
Exp/Cntr=0.3,0.1

Type RM Length L Ch R = 1 ,17958.03,4.98,4.96,5.01
XS GIS Cut Line= 5
-609289.07889999   -1045149.6626    -609326.2672   -1045090.5068
    -609331.3531   -1045071.1643-609362.16739999   -1045001.6811
     -609463.228   -1044828.8855
#Sta/Elev= 30
       0  369.29   10.49  367.12   14.99  366.62   22.52  362.14   25.14  361.66
   48.53   359.5   60.23  359.41   60.84  358.54   61.76  359.58   70.13  359.78
   75.55 359.302    75.8   359.3   75.82  357.91   79.63  357.53    84.3  357.64
   84.42  358.13   85.85  358.13   85.91  359.33   86.02359.3391   88.33  359.73
  100.05  359.74  101.16  359.17  113.29  359.09  128.04  359.49  246.69  359.43
  300.86  359.83  339.45  361.39  344.75  362.14  352.79  362.59  366.06  364.66
#Mann= 3 ,-1 , 0
       0     .15       0   75.55     .04       0   86.02     .15       0
Levee=-1,70.67,359.7,-1,88.68,359.7,,
#Block Obstruct= 1 ,-1
   137.4   140.4362.4691
Bank Sta=75.55,86.02
XS Rating Curve= 0 ,0
Exp/Cntr=0.5,0.3

Type RM Length L Ch R = 1 ,17953.06,18.09,19.04,21.99
XS GIS Cut Line= 5
    -609293.7773   -1045151.3166    -609330.9657   -1045092.1607
    -609336.0515   -1045072.8183    -609366.8658   -1045003.3351
-609467.92639999   -1044830.5395
#Sta/Elev= 30
       0  369.07    11.2  366.99   16.25  366.54   23.81  361.64   31.67  361.21
   34.54  359.98   49.71  359.02   55.47  359.16   56.39  358.03   57.93  359.51
   75.67   359.3   75.68  357.75   75.77  357.73   83.46  357.58   84.45  357.61
   84.51  358.04   86.02  357.94   86.03  358.73   86.12  358.74   86.13  359.33
   88.09  359.64  117.88  359.15     130   359.5  300.62  359.77  332.39     361
  334.26  362.21  336.13  362.19  336.58  361.57  354.75  362.83  366.06  365.13
#Mann= 3 , 0 , 0
       0     .15       0   75.67     .04       0   86.13     .15       0
Levee=-1,66.05,359.48,-1,89.61,359.48,,
Bank Sta=75.67,86.13
XS Rating Curve= 0 ,0
Exp/Cntr=0.5,0.3

Type RM Length L Ch R = 1 ,17934.03,65.98,74.44,72.11
XS GIS Cut Line= 5
    -609319.7439   -1045164.6074-609346.21489999    -1045097.348
    -609356.5102   -1045080.2014-609385.44929999   -1045009.9555
    -609484.1037    -1044838.313
#Sta/Elev= 30
       0  369.98    4.24  370.22     6.8  369.31   10.23  368.96   10.42  368.14
    18.3  367.33   23.78   362.9   27.99   362.3   36.51  359.32   52.99   358.4
   54.67  357.65   57.58  359.02   76.56   358.8   78.51  357.62   84.98  357.26
   85.93  357.35    88.7358.8978   94.07  359.24  120.45  358.94  180.97   359.7
   185.5  359.25  295.12  359.45   312.5  360.15  328.34  360.25  331.09  361.19
  343.38  361.45  347.01  361.72  352.88  362.67   359.2  364.58  366.23  367.65
#Mann= 3 ,-1 , 0
       0     .15       0   76.56     .04       0    88.7     .15       0
Levee=0,,,-1,94.23,359.25,,
#XS Ineff= 2 , 0
           66.97  361.58
Permanent Ineff=
       F       F
Bank Sta=76.56,88.7
XS Rating Curve= 0 ,0
Exp/Cntr=0.3,0.1

Type RM Length L Ch R = 1 ,17840.02,57.92,57.13,54.77
XS GIS Cut Line= 6
-609414.96049999    -1045194.222    -609420.4036   -1045157.2118
-609423.78489999   -1045137.4997    -609430.7512   -1045104.4406
    -609461.8814    -1045044.887    -609553.0165   -1044863.5194
#Sta/Elev= 30
       0  369.78   31.27  367.07   33.07  366.27   39.48   362.5   40.23  362.42
   44.37  359.45   44.54  359.04   44.59  357.75   45.31  355.55   47.35  355.37
   53.89  356.09   55.44357.2657   62.02  357.77   62.03  356.76   63.43  356.55
   63.75  357.01   64.18   358.1   81.51  358.03   98.41  358.41   193.3  358.25
   270.5   358.6  298.63  359.38  303.86  359.71  317.73  361.57  324.51  364.51
   326.8  364.77  328.62   365.8  346.91  368.43  356.85  371.77  361.37  369.68
#Mann= 3 ,-1 , 0
       0     .15       0   44.37     .05       0   55.44     .15       0
Levee=0,,,-1,66.05,357.88,,
#Block Obstruct= 1 ,-1
   153.9  155.72361.4517
Bank Sta=44.54,55.44
XS Rating Curve= 0 ,0
Exp/Cntr=0.3,0.1

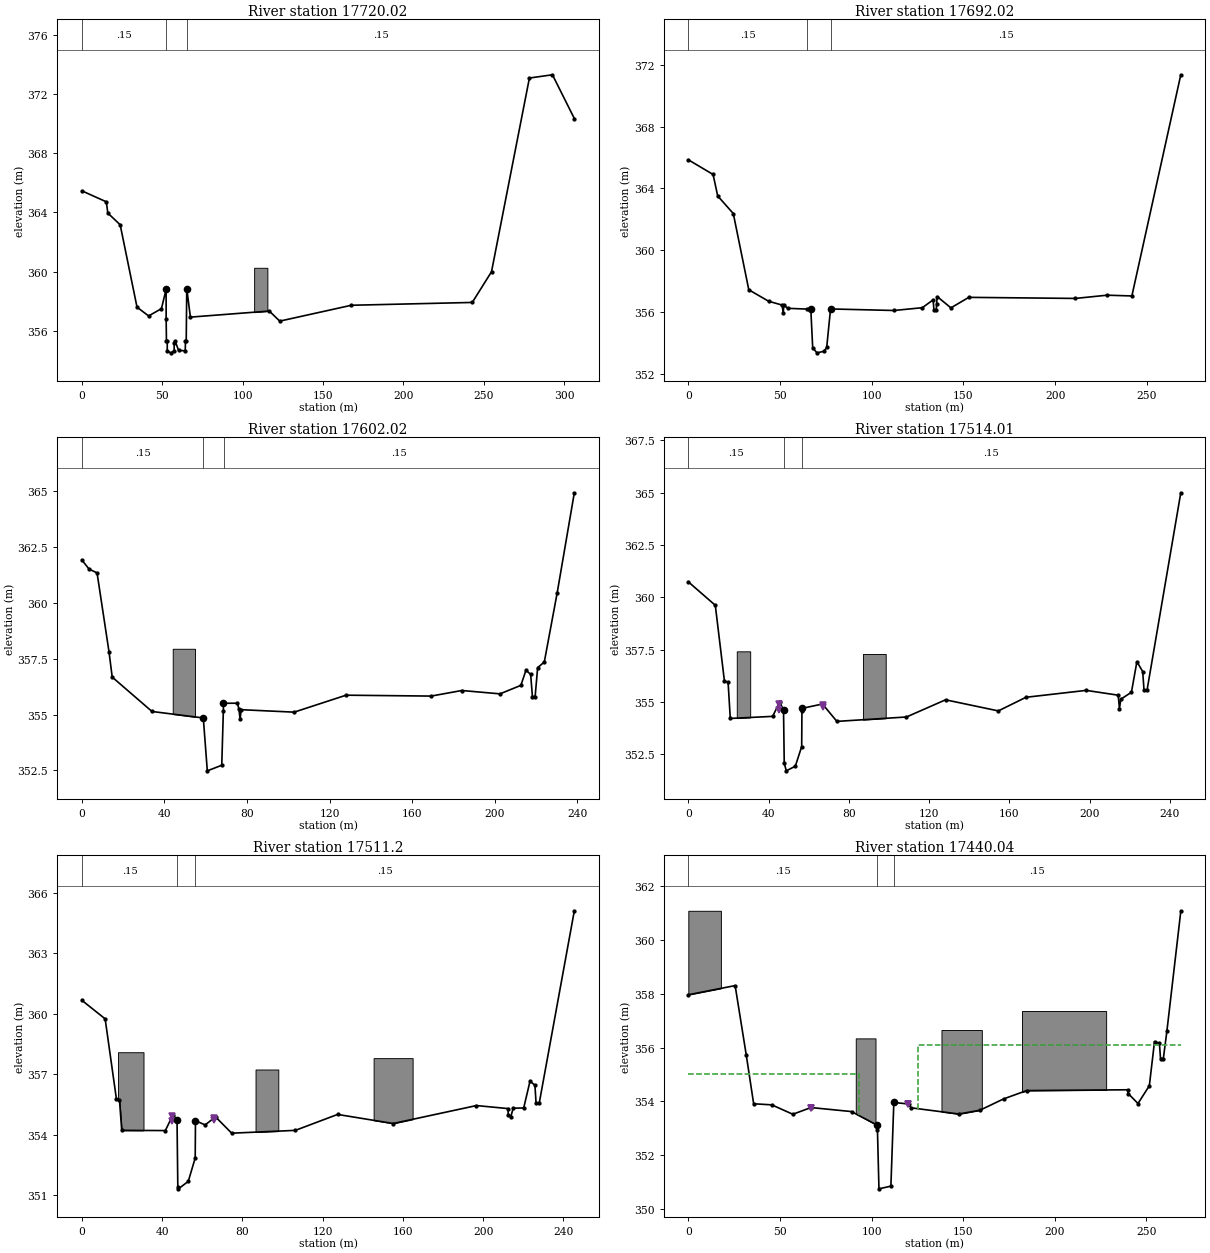
Type RM Length L Ch R = 1 ,17720.02,5.95,5.94,5.93
XS GIS Cut Line= 6
-609530.90949999   -1045209.5616-609540.83509999   -1045177.0778
     -609541.896   -1045141.5778    -609542.1886   -1045093.1615
    -609613.9235   -1044959.6171    -609631.9701   -1044927.5846
#Sta/Elev= 30
       0  365.46   15.22  364.72   16.15  363.96   23.83  363.17   34.31  357.61
   41.52  357.02    49.5  357.51    52.4  358.81   52.43  356.79   52.61  355.32
   53.11  355.32   53.12  354.64   55.31  354.53   57.39  354.66   57.44  355.22
   57.94  355.34   60.19  354.69   64.31  354.67   64.44  355.31   64.91  355.32
   65.24  358.87    67.5  356.94  116.56  357.35  123.08  356.67  167.63  357.74
  242.81  357.93  254.77     360  278.34  373.07  292.67  373.29  306.28  370.34
#Mann= 3 ,-1 , 0
       0     .15       0    52.4     .04       0   65.24     .15       0
#Block Obstruct= 1 ,-1
  107.15  115.38360.2692
Bank Sta=52.4,65.24
XS Rating Curve= 0 ,0
Exp/Cntr=0.5,0.3

Type RM Length L Ch R = 1 ,17692.02,41.2,44.05,46.63
XS GIS Cut Line= 6
-609544.89559999   -1045215.8779-609568.07849999   -1045159.3655
-609569.86809999   -1045139.4457    -609584.1468   -1045094.0638
-609585.04899999   -1045083.2359-609645.95609999   -1044969.5427
#Sta/Elev= 30
       0  365.85    13.5   364.9   16.02  363.51   24.53  362.37   32.97  357.44
   43.75   356.7   51.15  356.45   51.73  355.95   52.11  356.46   54.11  356.24
   64.97  356.19   66.77  356.21   67.81  353.69   70.12  353.36   74.01  353.46
   75.45  353.71   77.54   356.2   112.1   356.1  127.58  356.28  133.49  356.79
  133.91  356.12   135.2  356.12  135.36  356.53   135.7     357  143.17  356.27
  152.93  356.95  211.03  356.88  228.34  357.09  241.83  357.04   268.5  371.35
#Mann= 3 ,-1 , 0
       0     .15       0   64.97    .045       0   77.54     .15       0
Bank Sta=66.77,77.54
XS Rating Curve= 0 ,0
Exp/Cntr=0.3,0.1

Type RM Length L Ch R = 1 ,17602.02,44.99,45.33,43.77
XS GIS Cut Line= 4
    -609628.5299    -1045233.445-609649.70439999   -1045183.4506
    -609659.3708   -1045165.9417    -609730.4928    -1045017.789
#Sta/Elev= 30
       0  361.93     3.5  361.52    7.37  361.35   13.18   357.8   14.71  356.68
   33.99  355.14   58.85  354.85   60.79  352.48   67.79  352.73   68.56  355.16
   68.63  355.51   68.66355.5085   75.39  355.51   76.07  355.26   76.69   354.8
   77.19  355.22  102.87  355.11  128.03  355.87  169.26  355.83  184.11  356.08
   202.6  355.93  212.73  356.31   215.2  356.99  217.47   356.8  218.32  355.81
  219.64  355.81  220.85   357.1  224.09  357.36  230.35  360.47  238.63  364.94
#Mann= 3 ,-1 , 0
       0     .15       0   58.85     .04       0   68.66     .15       0
#Block Obstruct= 1 ,-1
   44.03   54.82357.9499
Bank Sta=58.85,68.63
XS Rating Curve= 0 ,0
Exp/Cntr=0.3,0.1

Type RM Length L Ch R = 1 ,17514.01,2.8,2.8,2.82
BEGIN DESCRIPTION:
17708  PF 227 ŽELEZNÝ MOSTEK V KVASINÁCH (F39)
END DESCRIPTION:
XS GIS Cut Line= 4
    -609698.4602   -1045261.8683     -609725.443   -1045231.8903
-609730.18059999   -1045212.4594-609799.52079999   -1045040.7983
#Sta/Elev= 30
       0  360.74   13.45  359.62   17.99  356.01   19.82  355.95   20.92  354.22
   42.05  354.32   45.47     355   47.45354.6392   47.81  352.09   48.83  351.72
   53.33  351.94   56.51  352.88   56.63  354.56   56.64   354.7   66.87  354.91
   74.05  354.08  108.73  354.29  128.22  355.11  154.53  354.58  168.29  355.23
  198.31  355.56  214.27  355.33  214.89  354.69  215.58  355.14  220.87  355.47
  223.59  356.93  226.48  356.46  227.14  355.57  228.65  355.57  245.47  364.99
#Mann= 3 ,-1 , 0
       0     .15       0   47.45     .04       0   56.63     .15       0
Levee=-1,45.03,354.64,-1,67.26,354.77,,
#Block Obstruct= 2 ,-1
   87.04   98.39357.2969   24.15   30.84357.4231
Bank Sta=47.45,56.64
XS Rating Curve= 0 ,0
Exp/Cntr=0.5,0.3

Type RM Length L Ch R = 1 ,17511.2 ,12.67,11.2,9.7
XS GIS Cut Line= 4
    -609701.1935   -1045262.4972-609728.17619999   -1045232.5193
-609732.91389999   -1045213.0884-609802.25409999   -1045041.4272
#Sta/Elev= 30
       0  360.67   11.61  359.75   17.21  355.79   18.74  355.74   19.88  354.22
   41.62  354.21   45.47     355   47.44  354.71   47.83  351.43   48.13  351.32
   53.04  351.69    56.5  352.85   56.64   354.7   61.45  354.49   66.63  354.89
   74.68  354.08  106.42  354.22  127.47  355.01  155.19  354.56  196.68  355.45
  212.48   355.3  212.49  354.98  213.78  354.89  215.01  355.32  220.24  355.33
  223.38  356.66  225.83  356.46   226.4  355.57  227.98  355.57  245.47  365.11
#Mann= 3 , 0 , 0
       0     .15       0   47.44     .04       0   56.64     .15       0
Levee=-1,45.03,354.7,-1,65.82,354.72,,
#Block Obstruct= 3 ,-1
   86.57   97.92357.2387  145.42  164.87357.8016   18.01   30.73358.0956
Bank Sta=47.44,56.64
XS Rating Curve= 0 ,0
Exp/Cntr=0.5,0.3

Type RM Length L Ch R = 1 ,17440.04,41.3,46.93,51.33
XS GIS Cut Line= 4
-609760.83949999    -1045326.651-609797.06219999   -1045248.2126
    -609803.9891   -1045215.1089    -609864.0548   -1045079.3023
#Sta/Elev= 29
       0  357.96   25.55   358.3   31.64  355.71   35.65  353.91   45.53  353.87
   57.03  353.52   66.93  353.77   89.06  353.62  103.17  353.11   103.2  352.94
  104.02  350.75  110.53  350.85  112.14  353.96  120.22   353.9  121.54  353.76
  147.61  353.53  159.11  353.67     172  354.09  184.58   354.4  239.73  354.43
  240.01  354.29  245.36  353.92  251.56  354.58  254.38  356.22  257.06  356.15
  257.65  355.59   259.2  355.59  261.12   356.6  268.72  361.06
#Mann= 3 , 0 , 0
       0     .15       0  103.17     .04       0  112.14     .15       0
Levee=-1,66.86,353.76,-1,119.86,353.89,,
#XS Ineff= 2 , 0
           93.01  355.01  125.06          356.08
Permanent Ineff=
       F       F
#Block Obstruct= 4 ,-1
       0   17.78361.0793  182.05  227.99357.3547  138.13  160.15356.6496
   91.36  102.14356.3394
Bank Sta=103.17,112.14
XS Rating Curve= 0 ,0
Exp/Cntr=0.3,0.1