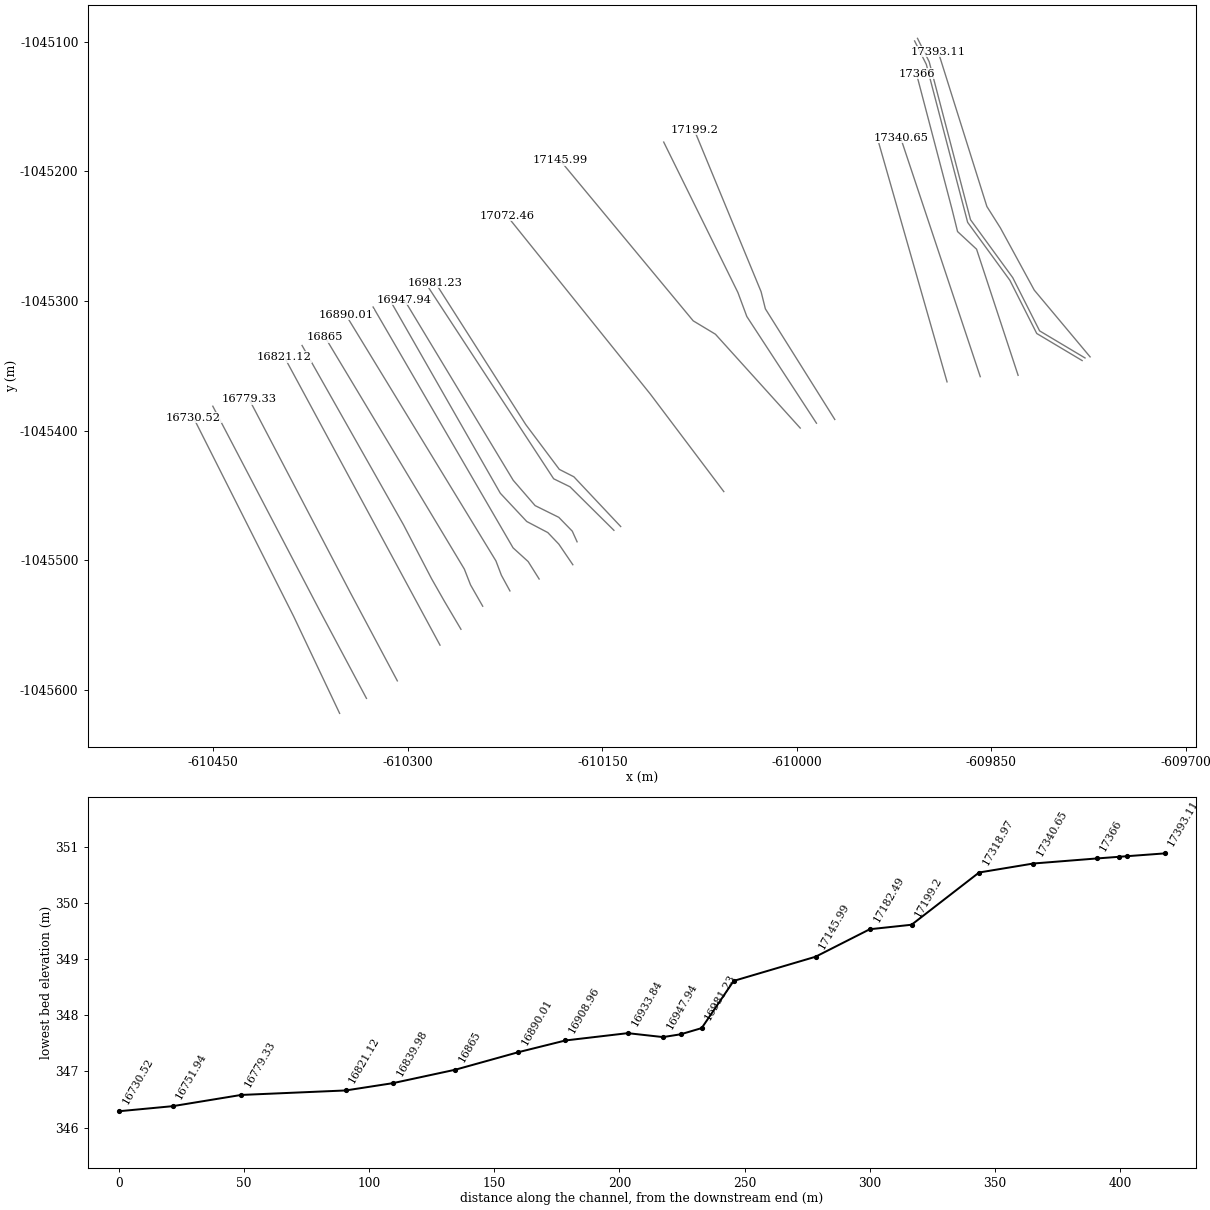
HEC-RAS study PPO_Kvasiny_efektiv.prj: PPO_Kvasiny_efektivita

--- PPO_Kvasiny_efektiv.g08 (geometry) --- (continued)

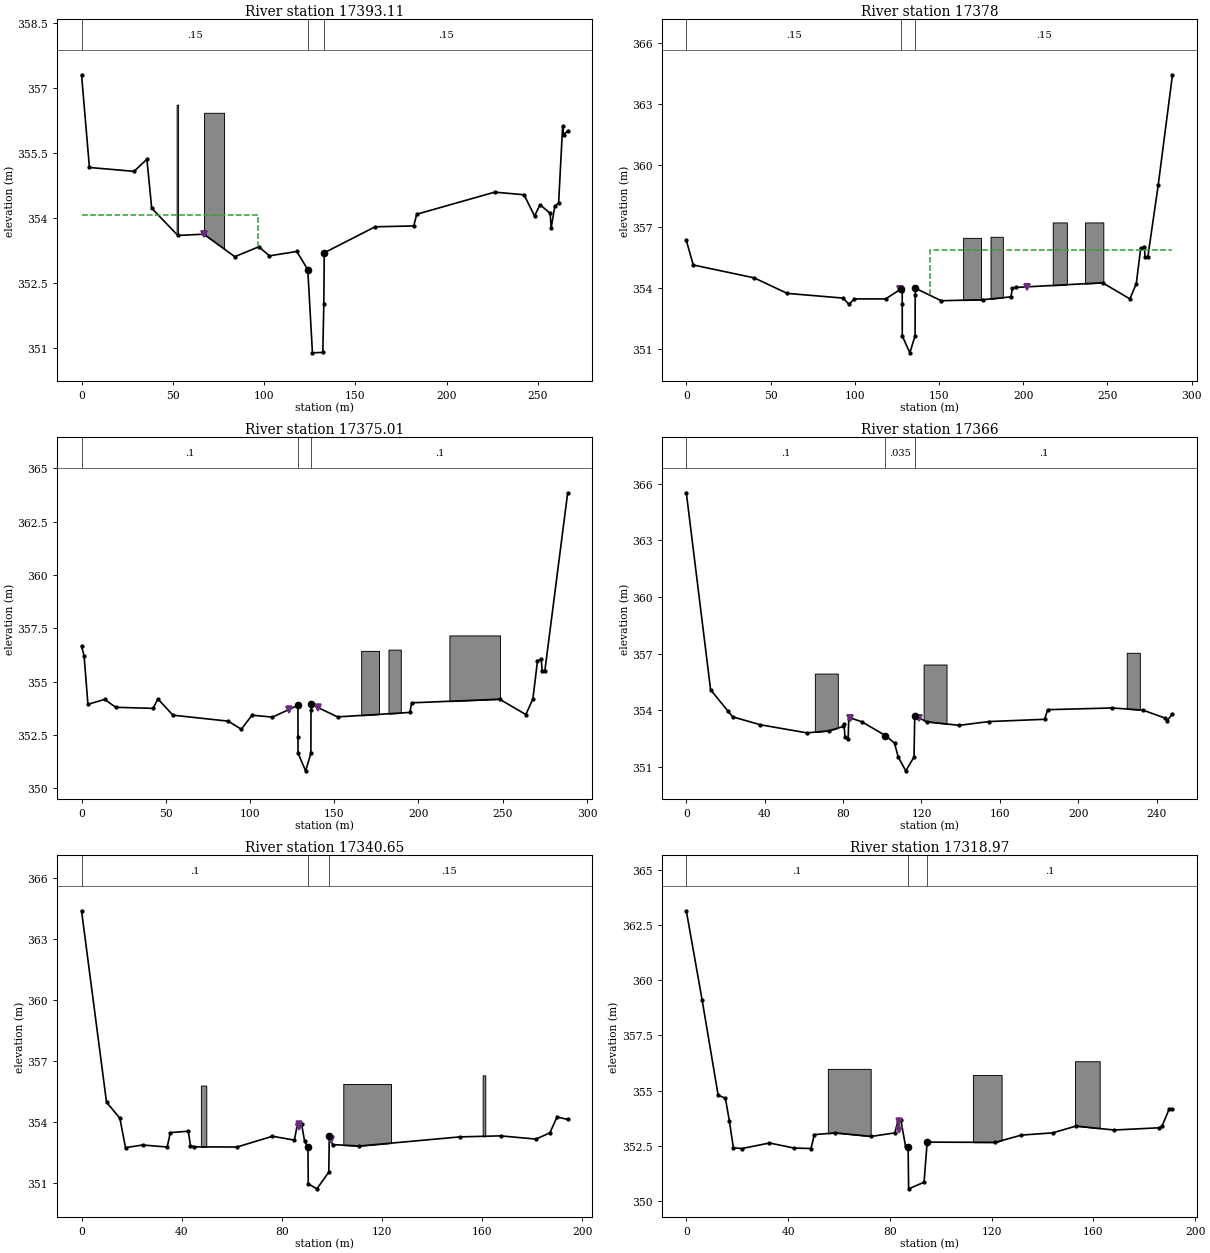
Type RM Length L Ch R = 1 ,17393.11,13.26,15.1,14.97
XS GIS Cut Line= 5
    -609773.9127   -1045343.0054    -609816.9842   -1045291.5139
-609843.09259999   -1045243.5518-609853.51619999   -1045227.0443
    -609891.0705   -1045107.7374
#Sta/Elev= 30
       0   357.3    4.31  355.16   28.77  355.07   35.81  355.35   38.43  354.22
   52.76  353.59   67.02  353.62   83.96   353.1   97.17  353.33  102.89  353.12
  117.97  353.22  123.95   352.8   126.5  350.88  132.18  350.89  132.74  352.01
  132.96  353.19  160.85  353.79  182.01  353.81  183.61  354.08  226.35  354.59
  242.41  354.53  248.19  354.04   251.2   354.3  256.76   354.1  257.29  353.76
   259.3  354.27  261.37  354.34  263.58  356.12  264.05  355.92  266.34     356
#Mann= 3 , 0 , 0
       0     .15       0  123.95     .04       0  132.96     .15       0
Levee=-1,67.02,353.62,0,,,,
#XS Ineff= 2 , 0
            96.6  354.06
Permanent Ineff=
       F       F
#Block Obstruct= 2 ,-1
   52.09    52.9356.6096   67.13    78.1356.4224
Bank Sta=123.95,132.96
XS Rating Curve= 0 ,0
Exp/Cntr=0.3,0.1

Type RM Length L Ch R = 1 ,17378   ,2.96,2.99,2.78
XS GIS Cut Line= 6
     -609777.842   -1045343.8274-609812.85159999     -1045322.95
    -609833.5683   -1045281.9181    -609866.1356    -1045237.247
    -609898.0165   -1045115.3894    -609907.0396   -1045097.3429
#Sta/Elev= 30
       0  356.33    4.12  355.13   40.29   354.5   59.87  353.74   93.02  353.51
   96.51  353.21   99.77  353.47  118.31  353.47  127.69  353.97  128.16  353.84
  128.17  353.23  128.18  351.66  132.69  350.83  135.79  351.67  135.87  353.64
  136.03  353.99   151.3  353.38  175.95  353.43  192.67  353.57  193.59  353.99
  195.42  354.03  247.07  354.26  263.29  353.47  267.08  354.21  269.69  355.94
  271.77  356.02  272.35  355.51  273.92  355.51  280.14  359.06  288.57  364.44
#Mann= 3 , 0 , 0
       0     .15       0  127.69     .04       0  136.03     .15       0
Levee=-1,127,353.97,-1,202.48,354.04,,
#XS Ineff= 2 , 0
                           144.8          355.87
Permanent Ineff=
       F       F
#Block Obstruct= 4 ,-1
   164.3  174.89356.4578  180.57  187.88356.5107   217.5   225.9357.2125
  236.65  247.52357.2125
Bank Sta=127.69,136.03
XS Rating Curve= 0 ,0
Exp/Cntr=0.5,0.3

Type RM Length L Ch R = 1 ,17375.01,8.74,9.01,9.67
XS GIS Cut Line= 6
    -609780.0582   -1045345.8438    -609815.0678   -1045324.9665
-609835.78449999   -1045283.9345-609868.35179999   -1045239.2635
    -609900.2327   -1045117.4058     -609909.256   -1045099.3593
#Sta/Elev= 30
       0  356.66    1.51  356.22     3.8  353.94   13.71  354.17   20.31   353.8
   42.47  353.75   45.33  354.19   54.28  353.43   87.05  353.15   94.83  352.77
   101.2  353.43  113.33  353.34  128.45  353.89  128.49  352.43   128.5  351.65
  133.03  350.82  136.13  351.64   136.2  353.67  136.27  353.94  152.01  353.35
  194.94  353.56  195.97  354.01  248.13  354.18  263.75  353.46  267.91  354.19
  270.65  355.98  272.83  356.06  273.43  355.51  275.01  355.51  288.57  363.86
#Mann= 3 , 0 , 0
       0      .1       0  128.45     .04       0  136.27      .1       0
Levee=-1,123.15,353.68,-1,140.13,353.75,,
#Block Obstruct= 3 ,-1
  165.99  176.58 356.446  182.19   189.5356.5049  218.36  248.38357.1706
Bank Sta=128.45,136.27
XS Rating Curve= 0 ,0
Exp/Cntr=0.5,0.3

Type RM Length L Ch R = 1 ,17366   ,28.61,25.35,19.86
XS GIS Cut Line= 5
    -609829.4397   -1045357.2129    -609861.4726   -1045259.9622
    -609876.1358   -1045246.3611    -609880.4211   -1045229.0826
    -609907.8099   -1045124.7443
#Sta/Elev= 30
       0  365.52   12.38  355.09   21.35  353.94   23.66  353.65    37.8  353.23
    61.6   352.8    72.7  352.91   79.98  353.14   80.52  353.26   80.93  352.56
   82.58   352.5    82.9  353.53    83.5   353.6   89.54  353.39   101.6  352.66
  106.24  352.26  108.13  351.52  111.97  350.79  116.19  351.52  116.56  353.71
   122.6  353.39  139.25   353.2  154.31   353.4  182.83  353.52  184.41  354.03
  217.23  354.12  232.88  354.01  244.41  353.58   245.3  353.44  248.07  353.81
#Mann= 3 , 0 , 0
       0      .1       0   101.6    .035       0  116.56      .1       0
Levee=-1,83.57,353.57,-1,118.79,353.57,,
#Block Obstruct= 3 ,-1
   65.59   77.29355.9429  224.73  231.42357.0443  121.07  132.79 356.422
Bank Sta=101.6,116.56
XS Rating Curve= 0 ,0
Exp/Cntr=0.3,0.1

Type RM Length L Ch R = 1 ,17340.65,22.16,21.68,21.33
XS GIS Cut Line= 2
    -609858.6317   -1045358.2556    -609920.0152   -1045174.1052
#Sta/Elev= 30
       0   364.4    9.97  354.97    15.3  354.18   17.56  352.73   24.41  352.86
   34.21  352.76   35.44  353.47   42.65  353.54   43.48  352.83   44.98  352.77
   62.04  352.76   76.22  353.29      85   353.1   86.18  353.89   87.07   353.9
   87.83   353.9   89.06  353.05   90.41  352.74   90.52  350.95   93.96   350.7
   98.72  351.52   98.92  353.29  100.25  352.88  110.89  352.81  151.11  353.26
  167.41  353.31  181.44  353.15  187.01  353.46  189.85  354.24  194.11  354.12
#Mann= 3 , 0 , 0
       0      .1       0   90.41    .037       0   98.92     .15       0
Levee=-1,86.84,353.75,-1,99.42,353.11,,
#Block Obstruct= 3 ,-1
  104.51  123.54355.8673   47.65   49.81355.7874  160.17   161.2356.2895
Bank Sta=90.41,98.92
XS Rating Curve= 0 ,0
Exp/Cntr=0.3,0.1

Type RM Length L Ch R = 1 ,17318.97,27.08,26.98,26.72
XS GIS Cut Line= 2
    -609884.2434   -1045362.2772    -609936.7369   -1045178.5502
#Sta/Elev= 30
       0  363.16    6.23   359.1   12.51  354.79   15.36  354.65   16.89  353.64
   18.51   352.4   21.88  352.37   32.69  352.62    42.4  352.39   49.01  352.37
   50.32     353   58.54  353.08   72.71  352.92   81.96  353.08   83.21  353.62
   84.33  353.65   86.16  352.48   87.18  352.44   87.38  350.54   93.44  350.84
   94.66  352.66  121.45  352.65  131.72  352.98  143.99  353.08  153.18  353.39
  168.15  353.21  185.65  353.31  186.95  353.38  189.85  354.18  191.08  354.15
#Mann= 3 , 0 , 0
       0      .1       0   87.18    .045       0   94.66      .1       0
Levee=-1,83.6,353.22,0,,,,
#Block Obstruct= 3 ,-1
   55.63   72.46355.9849  152.78  162.47356.3312  112.64  123.92355.7037
Bank Sta=87.18,94.66
XS Rating Curve= 0 ,0
Exp/Cntr=0.3,0.1

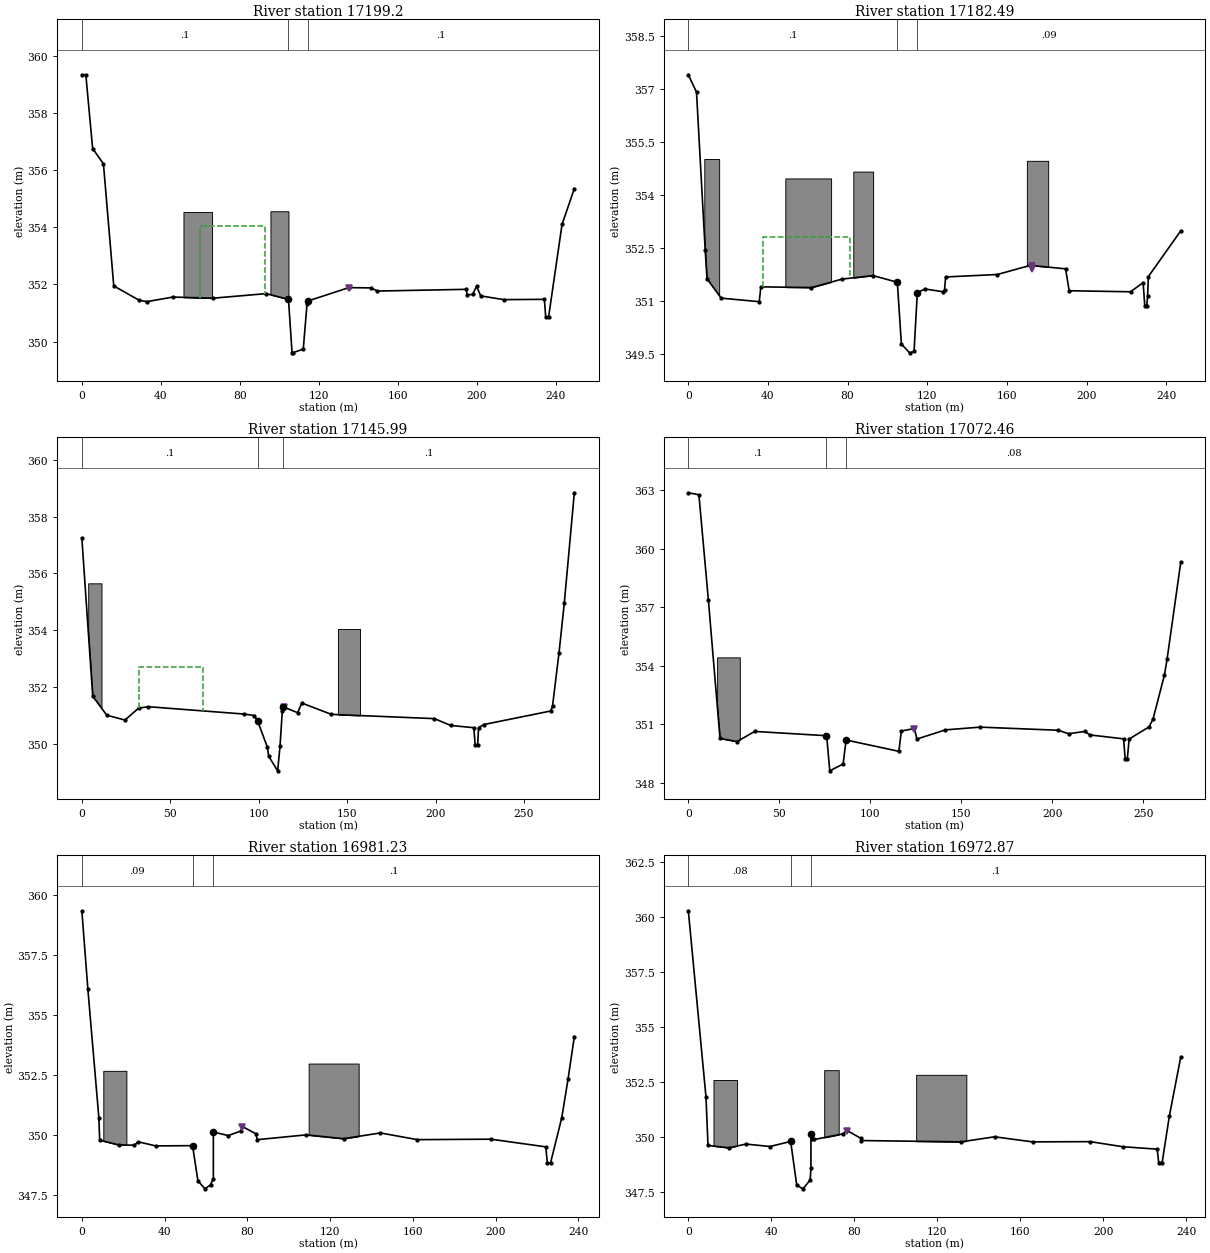
Type RM Length L Ch R = 1 ,17199.2 ,15.17,16.71,17.13
XS GIS Cut Line= 4
-609970.81529999   -1045391.2756-610024.34479999    -1045305.958
    -610027.6521   -1045292.7288-610079.25149999   -1045167.8199
#Sta/Elev= 30
       0  359.33    2.01  359.33    5.47  356.75   10.93  356.22   16.16  351.95
   28.98  351.45   32.98   351.4   46.06  351.56   66.39  351.52    93.4  351.68
  104.68  351.48  106.49  349.62  106.73  349.61  112.17  349.74  114.08  351.32
  114.43  351.42  135.27  351.89  146.56  351.88  149.72  351.77  194.77  351.83
  195.14  351.64  197.92  351.65  200.02  351.94  202.05   351.6  213.74  351.47
  234.32  351.48  235.01  350.86  236.43  350.85  243.28   354.1   249.5  355.35
#Mann= 3 , 0 , 0
       0      .1       0  104.68     .05       0  114.43      .1       0
Levee=0,,,-1,135.25,351.89,,
#XS Ineff= 1 ,-1
   60.05   92.96  354.04
Permanent Ineff=
       F
#Block Obstruct= 2 ,-1
   51.48   65.97354.5328   95.54  104.67354.5594
Bank Sta=104.68,114.43
XS Rating Curve= 0 ,0
Exp/Cntr=0.3,0.1

Type RM Length L Ch R = 1 ,17182.49,12.56,21.69,26.56
XS GIS Cut Line= 4
-609984.94399999   -1045394.1508-610038.65459999   -1045311.8652
    -610045.5337   -1045293.3443    -610102.7465   -1045177.3449
#Sta/Elev= 30
       0  357.41    4.11  356.92    8.48  352.44    9.38  351.63   16.51  351.08
    35.6  350.98   36.46   351.4   61.86  351.38   77.25  351.62   92.75  351.72
  104.98  351.53  107.02  349.78  111.16  349.53  113.38  349.57  115.02  351.23
  118.76  351.34  128.15  351.26   128.7  351.32  129.24  351.68  155.18  351.75
  171.85  352.01  189.49  351.91   191.3  351.29  222.11  351.26  228.44  351.52
  229.27  350.86  230.26  350.86   230.7  351.14  231.06  351.69  247.36  352.99
#Mann= 3 , 0 , 0
       0      .1       0  104.98     .05       0  115.02     .09       0
Levee=0,,,-1,172.78,351.92,,
#XS Ineff= 1 ,-1
   37.53   81.12   352.8
Permanent Ineff=
       F
#Block Obstruct= 4 ,-1
   82.86   92.82354.6667    8.03   15.49355.0234   48.72   71.72354.4726
  170.04  180.75354.9718
Bank Sta=104.98,115.02
XS Rating Curve= 0 ,0
Exp/Cntr=0.3,0.1

Type RM Length L Ch R = 1 ,17145.99,27.89,32.71,30.59
XS GIS Cut Line= 4
-609997.46979999   -1045397.9022-610062.86769999   -1045325.5206
    -610080.0049   -1045315.2094    -610182.7567   -1045191.3149
#Sta/Elev= 30
       0  357.24    6.15  351.67    14.1     351   24.39  350.83   32.11  351.25
   37.64   351.3   91.97  351.04   97.39  350.99   99.35  350.81  104.81  349.89
  105.71  349.55  110.73  349.04  112.06   349.9  113.36  351.14  113.98  351.29
  122.05  351.09  124.36  351.43  141.11  351.03  199.41  350.88  208.51  350.64
  221.71  350.56  222.39  349.96  223.87  349.96  224.34  350.56  227.21  350.67
  265.19  351.15  266.17  351.32  269.86   353.2  272.83  354.95  278.51  358.84
#Mann= 3 , 0 , 0
       0      .1       0   99.35     .05       0  113.98      .1       0
Levee=0,,,-1,114.15,351.27,,
#XS Ineff= 1 ,-1
   32.39   68.76  352.71
Permanent Ineff=
       F
#Block Obstruct= 2 ,-1
  144.81  157.32 354.041    3.59   11.11355.6489
Bank Sta=99.35,113.98
XS Rating Curve= 0 ,0
Exp/Cntr=0.3,0.1

Type RM Length L Ch R = 1 ,17072.46,16.25,12.79,10.07
XS GIS Cut Line= 3
    -610056.4079   -1045446.8883    -610113.0288   -1045371.7464
-610223.62489999   -1045234.1628
#Sta/Elev= 30
       0  362.86    5.81  362.76   11.04  357.35   17.41  350.27   26.76  350.11
   36.49  350.63   75.89  350.41   76.02  350.41   77.72  348.61   85.07  348.96
   86.69  350.19  115.69  349.61  117.06  350.65  124.26  350.78  125.58  350.24
  141.31  350.71  160.37  350.85  203.33  350.69  208.96  350.51  217.84  350.63
  220.67  350.45  239.18  350.25  240.04  349.23  241.23  349.23  242.23  350.24
  253.12  350.86  255.34  351.26  261.63  353.52  263.12  354.36  270.61  359.31
#Mann= 3 , 0 , 0
       0      .1       0   75.89     .05       0   86.69     .08       0
Levee=0,,,-1,124.23,350.77,,
#Block Obstruct= 1 ,-1
   15.82    28.3354.4257
Bank Sta=75.89,86.69
XS Rating Curve= 0 ,0
Exp/Cntr=0.3,0.1

Type RM Length L Ch R = 1 ,16981.23,7.15,8.37,7.3
XS GIS Cut Line= 5
    -610135.9278   -1045473.8311-610172.04879999   -1045435.4654
    -610183.2412   -1045429.7737-610209.17089999   -1045395.1544
    -610278.8182   -1045285.8913
#Sta/Elev= 30
       0  359.36    2.91  356.09    8.22  350.74    8.61   349.8   17.89   349.6
   25.37  349.59   27.28  349.73   35.71  349.56   53.52  349.57   56.11   348.1
   59.56  347.77   62.22  347.94   63.57   348.2   63.58  350.14   70.75  349.99
   76.88  350.18   77.52  350.37   84.05  350.07   84.83  349.82   108.5  350.02
  126.53  349.86  144.31   350.1  162.23  349.82  197.73  349.84  224.27  349.52
  225.05  348.85  226.58  348.85  232.02  350.74  235.04  352.34  238.08  354.11
#Mann= 3 , 0 , 0
       0     .09       0   53.52    .045       0   63.58      .1       0
Levee=0,,,-1,77.51,350.34,,
#Block Obstruct= 2 ,-1
  109.64  133.82352.9926   10.37   21.53352.6887
Bank Sta=53.52,63.58
XS Rating Curve= 0 ,0
Exp/Cntr=0.3,0.1

Type RM Length L Ch R = 1 ,16972.87,6.4,7.07,5.77
XS GIS Cut Line= 4
-610141.14319999    -1045476.769-610175.05779999   -1045443.1728
    -610187.6253   -1045437.0179    -610283.7571   -1045290.0894
#Sta/Elev= 30
       0  360.27    8.52  351.82    9.48  349.63   19.56  349.52   27.77  349.69
   39.38  349.58   49.32  349.81   52.24  347.83   55.24  347.66   58.72  348.06
   59.08  348.59   59.09  350.16    59.6  350.18   59.65  350.16   59.72  349.93
   60.78   349.9   74.43  350.15   76.38  350.31   83.13  349.95   83.39  349.85
  131.46  349.79   147.6  350.02  165.87  349.79  193.69   349.8  209.31  349.57
  225.93  349.46  226.67  348.85  228.32  348.85  231.83  350.98  237.31  353.65
#Mann= 3 , 0 , 0
       0     .08       0   49.32    .045       0   59.09      .1       0
Levee=0,,,-1,76.48,350.29,,
#Block Obstruct= 3 ,-1
   65.48   72.46353.0419  109.79  133.97352.8312   12.12   23.49 352.596
Bank Sta=49.32,59.09
XS Rating Curve= 0 ,0
Exp/Cntr=0.3,0.1

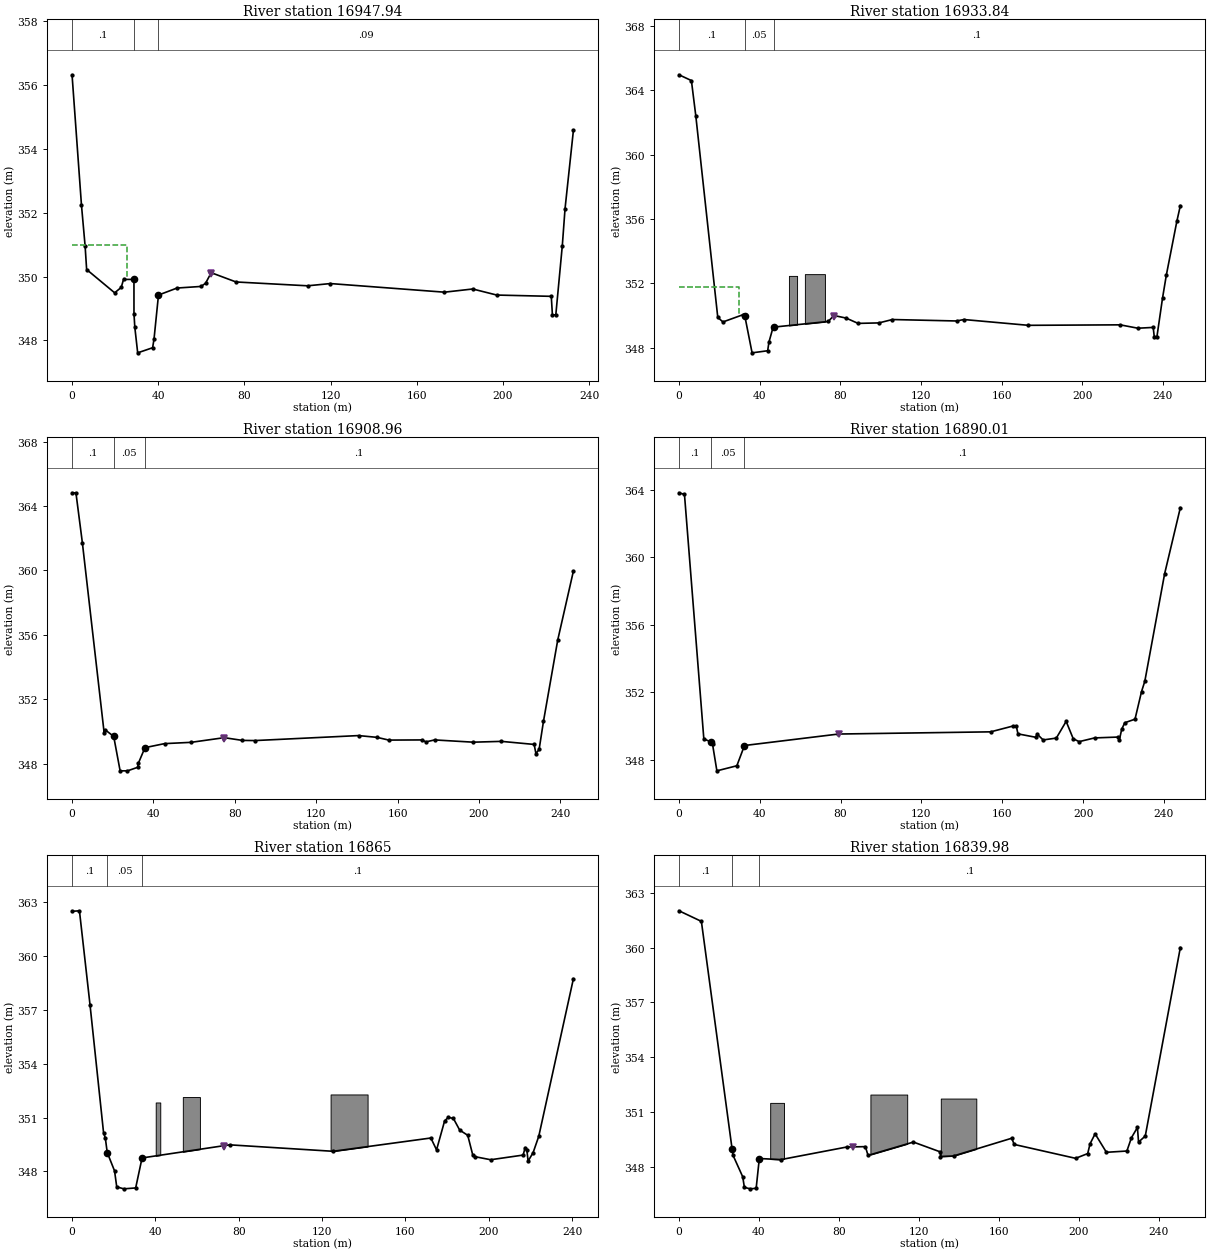
Type RM Length L Ch R = 1 ,16947.94,14.61,14.1,13.66
XS GIS Cut Line= 6
    -610169.5517   -1045485.6161-610173.24989999    -1045477.427
    -610183.6554   -1045466.7471-610201.92269999   -1045457.7056
    -610218.8174   -1045438.1758    -610302.8072   -1045298.9794
#Sta/Elev= 30
       0  356.32    4.38  352.23    6.07  350.95    6.77  350.22   19.78  349.49
   22.82  349.66    23.9  349.91   28.73  349.91   28.74  348.84   29.13  348.41
   30.46  347.61   37.39  347.77   38.04  348.04   40.11  349.42   48.72  349.64
   59.87  349.69   61.96  349.79   64.59  350.12   76.11  349.83  109.33  349.71
  119.86  349.78  172.83  349.51  185.94  349.61  197.09  349.42   222.4  349.38
  222.92   348.8   224.5   348.8  227.52  350.97  228.79  352.13  232.67  354.58
#Mann= 3 , 0 , 0
       0      .1       0   28.73    .045       0   40.11     .09       0
Levee=0,,,-1,64.52,350.09,,
#XS Ineff= 2 , 0
           25.69  350.98
Permanent Ineff=
       F       F
Bank Sta=28.73,40.11
XS Rating Curve= 0 ,0
Exp/Cntr=0.3,0.1

Type RM Length L Ch R = 1 ,16933.84,27.14,24.89,15.43
XS GIS Cut Line= 6
    -610172.8312   -1045503.2958    -610183.6262   -1045487.4208
    -610192.1378   -1045478.4949    -610208.3665   -1045469.9668
    -610228.7441   -1045448.1827    -610312.5439   -1045301.5194
#Sta/Elev= 30
       0  364.96    6.16   364.6    8.34  362.41   19.24  349.88   21.81   349.6
   31.53  350.04   32.63  349.98   36.25  347.68   43.98  347.81    44.6  348.34
    46.6  349.24   47.05  349.28      74  349.63   76.83     350   82.89  349.84
    88.8  349.51   99.14  349.54  105.83  349.75  137.71  349.66  141.24  349.75
  173.25  349.39  218.78  349.42  227.56  349.21  235.14  349.26  235.67  348.69
  237.01  348.69  239.77  351.08  241.66  352.51   246.9  355.87  248.61  356.83
#Mann= 3 , 0 , 0
       0      .1       0   32.63     .05       0   47.05      .1       0
Levee=0,,,-1,76.79,349.93,,
#XS Ineff= 2 , 0
           29.73   351.8
Permanent Ineff=
       F       F
#Block Obstruct= 2 ,-1
   54.52   58.56352.4616   62.43   72.37352.5712
Bank Sta=32.63,47.05
XS Rating Curve= 0 ,0
Exp/Cntr=0.3,0.1

Type RM Length L Ch R = 1 ,16908.96,23.54,18.95,17.48
XS GIS Cut Line= 4
    -610198.8204   -1045514.3025-610207.27569999   -1045500.8694
-610218.91739999    -1045490.286-610326.86769999   -1045304.5481
#Sta/Elev= 30
       0  364.82    1.92  364.81    5.06  361.73   15.76  349.93   16.33  350.09
   20.47  349.69   23.63  347.55   27.25  347.55   32.28  347.77   32.56  348.01
   35.84  348.99   45.46  349.24   58.51  349.32   74.81  349.61   83.76  349.44
   89.85  349.43  140.81  349.74  149.89  349.63   155.7  349.46  171.89  349.47
  173.96  349.35  178.22  349.47  197.19  349.33  211.07  349.38  227.15  349.19
  228.01  348.62  229.58  348.88  231.73  350.63  238.74  355.68  246.44  359.96
#Mann= 3 , 0 , 0
       0      .1       0   20.47     .05       0   35.84      .1       0
Levee=0,,,-1,74.62,349.53,,
Bank Sta=20.47,35.84
XS Rating Curve= 0 ,0
Exp/Cntr=0.3,0.1

Type RM Length L Ch R = 1 ,16890.01,24.27,25.01,24.32
XS GIS Cut Line= 4
-610221.34499999   -1045523.4945-610227.91319999   -1045511.4527
    -610232.1466   -1045500.3402-610348.03429999    -1045310.369
#Sta/Elev= 30
       0  363.81    2.72  363.71    12.3  349.23   15.89  349.05   16.62  348.91
   18.76  347.34   28.64  347.64   32.41  348.84   78.95  349.52  154.27  349.65
  165.49     350  166.92     350  167.77  349.53  176.48  349.33  177.43   349.5
  180.22  349.17  186.76  349.28  191.62  350.27  195.13  349.24  198.05  349.07
   205.7  349.29  217.16  349.34     218  349.19  219.11   349.8  220.63  350.19
   225.7   350.4  228.92  352.03  230.56  352.65  240.37  359.02  248.14  362.93
#Mann= 3 , 0 , 0
       0      .1       0   15.89     .05       0   32.41      .1       0
Levee=0,,,-1,79.1,349.54,,
Bank Sta=15.89,32.41
XS Rating Curve= 0 ,0
Exp/Cntr=0.3,0.1

Type RM Length L Ch R = 1 ,16865   ,23.67,25.02,24.87
XS GIS Cut Line= 4
    -610242.3339   -1045535.2969-610251.72569999   -1045518.8611
-610256.48829999   -1045506.6902-610363.90929999   -1045327.8315
#Sta/Elev= 30
       0  362.48    3.55  362.51    8.65  357.25   15.13  350.15   15.97  349.86
   16.89  349.05    20.4  348.03   21.45  347.14   24.84  347.03   30.54  347.08
    33.6  348.75   75.61  349.48  125.31  349.12  172.22  349.86  174.95   349.2
  178.82  350.81  180.57  351.01  183.03  350.95  186.06   350.3  189.92  350.01
  192.38  348.89  193.39  348.82  200.93  348.65  216.51  348.91  217.48  349.33
  218.28  349.22  218.88  348.57  221.31  349.05  224.02  349.96  240.64  358.73
#Mann= 3 , 0 , 0
       0      .1       0   16.89     .05       0    33.6      .1       0
Levee=0,,,-1,73.04,349.36,,
#Block Obstruct= 3 ,-1
   40.16   42.34351.8377   53.17   61.37352.1396  124.09  141.85352.2846
Bank Sta=16.89,33.6
XS Rating Curve= 0 ,0
Exp/Cntr=0.3,0.1

Type RM Length L Ch R = 1 ,16839.98,20.16,18.86,18.8
XS GIS Cut Line= 5
    -610259.1032   -1045553.0799-610271.81769999   -1045531.5794
    -610281.7151      -1045514.2-610303.42729999   -1045472.5025
-610381.65659999   -1045334.2117
#Sta/Elev= 30
       0  362.01   11.21  361.43    26.6  348.95   27.07  348.62   31.89  347.45
   32.73  346.87   35.66  346.79   38.62  346.82    40.2  348.45   50.96  348.39
   83.99  349.08   93.27   349.1    94.6  348.62  117.31  349.35  130.81  348.81
  130.81  348.56  137.38  348.59   166.5  349.56  167.74  349.22  198.45  348.46
  204.51  348.72   205.7  349.26  208.22   349.8  213.87  348.79  224.12  348.86
  226.41  349.59  229.39  350.15  229.96  349.35  233.32  349.68  250.87     360
#Mann= 3 , 0 , 0
       0      .1       0    26.6     .05       0    40.2      .1       0
Levee=0,,,-1,87.12,349.06,,
#Block Obstruct= 3 ,-1
   45.64   52.53351.4954     131  148.77351.7318   95.79   114.2 351.951
Bank Sta=26.6,40.2
XS Rating Curve= 0 ,0
Exp/Cntr=0.3,0.1

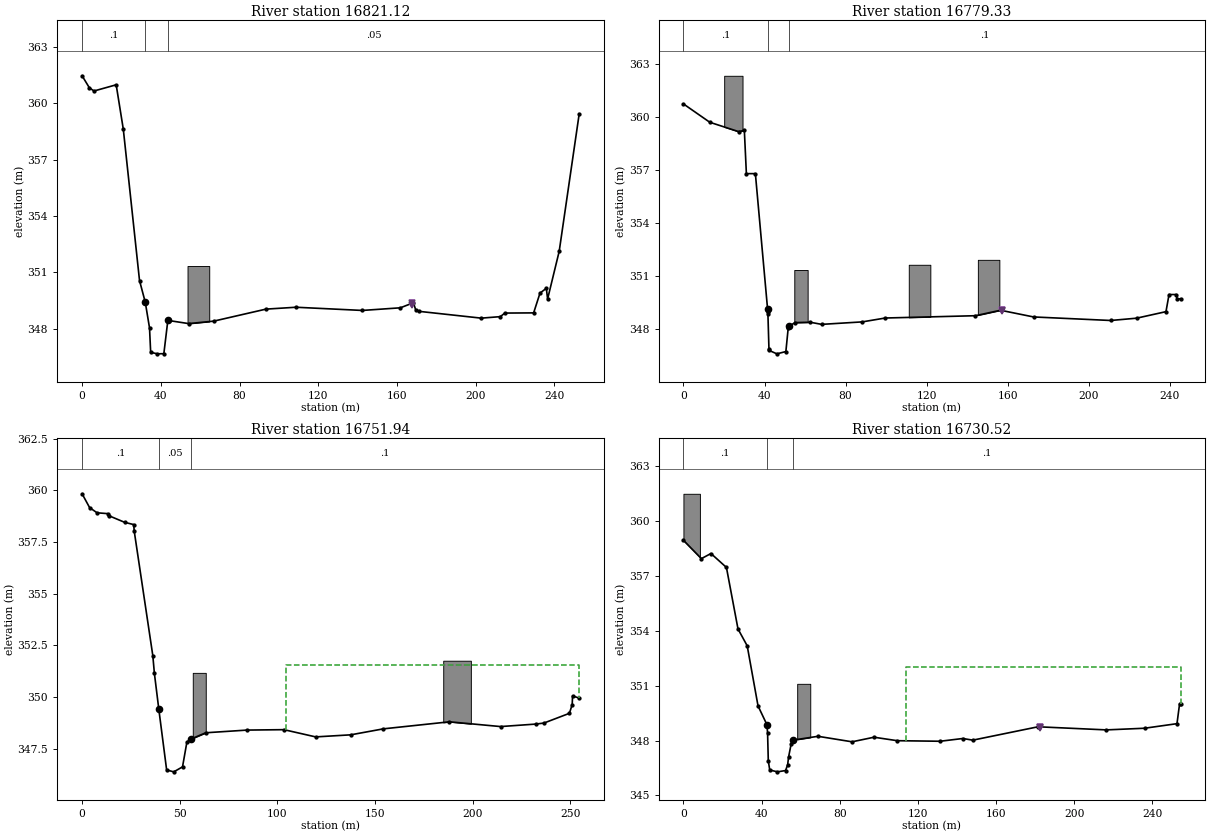
Type RM Length L Ch R = 1 ,16821.12,43.01,41.79,41.65
XS GIS Cut Line= 2
-610275.27459999   -1045565.3143    -610395.3498   -1045343.0538
#Sta/Elev= 30
       0  361.46    3.71  360.82    6.05  360.65   17.33  360.98   20.94  358.62
   29.19  350.56   32.12   349.4   34.27  348.04   34.85  346.74   38.31  346.66
   41.55  346.67   43.58  348.44   54.15  348.27   66.86   348.4   93.44  349.04
  108.69  349.14  142.41  348.97  161.72  349.11  168.37  349.38   169.6  348.98
  171.36  348.92  202.82  348.56  212.54  348.64  214.81  348.83  229.46  348.84
  232.68  349.89   235.9  350.15  236.56  349.58  242.45  352.12  252.62  359.44
#Mann= 3 , 0 , 0
       0      .1       0   32.12     .05       0   43.58     .05       0
Levee=0,,,-1,167.67,349.28,,
#Block Obstruct= 1 ,-1
   53.58   64.61351.3344
Bank Sta=32.12,43.58
XS Rating Curve= 0 ,0
Exp/Cntr=0.3,0.1

Type RM Length L Ch R = 1 ,16779.33,27.37,27.39,27.36
XS GIS Cut Line= 3
-610308.17929999   -1045592.8645    -610344.1895   -1045525.2731
    -610422.3832   -1045375.8722
#Sta/Elev= 30
       0  360.74   13.01   359.7   27.24  359.17   30.05  359.24   31.05  356.79
   35.49  356.79   41.52   349.1   41.67  348.96   41.68  348.82   42.18  346.88
   42.35  346.77    46.1  346.58   50.53  346.71   51.68  348.04   52.23  348.16
   55.08  348.35   62.56  348.37   68.18  348.25   88.19  348.39   99.57  348.61
  144.02  348.74  156.41  349.05   172.7  348.67  210.75  348.47  223.51   348.6
  238.02  348.97  239.52  349.94  243.06  349.94  243.51  349.69  245.21   349.7
#Mann= 3 , 0 , 0
       0      .1       0   41.52     .05       0   52.23      .1       0
Levee=0,,,-1,157.04,349.04,,
#Block Obstruct= 4 ,-1
   54.68   61.27351.3319  145.23  155.83351.9062  111.15  121.79351.6265
    20.1   29.15362.3344
Bank Sta=41.52,52.23
XS Rating Curve= 0 ,0
Exp/Cntr=0.3,0.1

Type RM Length L Ch R = 1 ,16751.94,21.77,21.42,20.49
XS GIS Cut Line= 3
-610331.99179999   -1045606.3583     -610368.002   -1045538.7669
    -610450.4891    -1045381.048
#Sta/Elev= 30
       0  359.83    3.86  359.16    7.68  358.91    13.1  358.87   13.71  358.77
   21.76  358.45   26.44  358.34   26.69  358.03   36.22     352   37.03  351.14
    39.3   349.4    43.3  346.47   46.95  346.38   51.43  346.62   53.67  347.82
   55.59  347.96   63.34  348.27    84.5   348.4  103.36  348.42  119.61  348.07
  137.55  348.17  154.31  348.46  188.11   348.8   214.3  348.57  232.32  348.69
   236.5  348.74  249.53  349.21  250.98  349.63  251.15  350.05  254.57  349.95
#Mann= 3 , 0 , 0
       0      .1       0    39.3     .05       0   55.59      .1       0
#XS Ineff= 2 , 0
                          104.45          351.53
Permanent Ineff=
       F       F
#Block Obstruct= 2 ,-1
  184.93  199.08351.7553   56.68   63.33351.1675
Bank Sta=39.3,55.59
XS Rating Curve= 0 ,0
Exp/Cntr=0.3,0.1

Type RM Length L Ch R = 1 ,16730.52,4.86,4.82,4.85
XS GIS Cut Line= 3
    -610352.6812   -1045617.9347-610388.15709999   -1045543.0952
    -610465.3939   -1045389.8634
#Sta/Elev= 30
       0  358.93    9.19  357.93   14.08  358.21   22.01  357.45   27.93  354.09
   32.64  353.17   38.18  349.89   42.75  348.86   43.07   348.4   43.43   346.9
   44.17  346.39   48.14  346.29   52.25  346.36   53.34  346.67   53.78  347.08
   55.17  347.83   55.91  348.02   68.85  348.23    86.3  347.93   97.54  348.18
  109.47  347.99  131.38  347.96  142.98  348.11   148.1  348.02  181.48  348.75
  216.45  348.58  235.97  348.67  252.59  348.92  253.94  350.02  254.42  350.01
#Mann= 3 , 0 , 0
       0      .1       0   42.75     .05       0   55.91      .1       0
Levee=0,,,-1,182.74,348.68,,
#XS Ineff= 2 , 0
                          113.87          352.02
Permanent Ineff=
       F       F
#Block Obstruct= 2 ,-1
   58.22   64.91351.0959       0    8.43361.4715
Bank Sta=42.75,55.91
XS Rating Curve= 0 ,0
Exp/Cntr=0.5,0.3