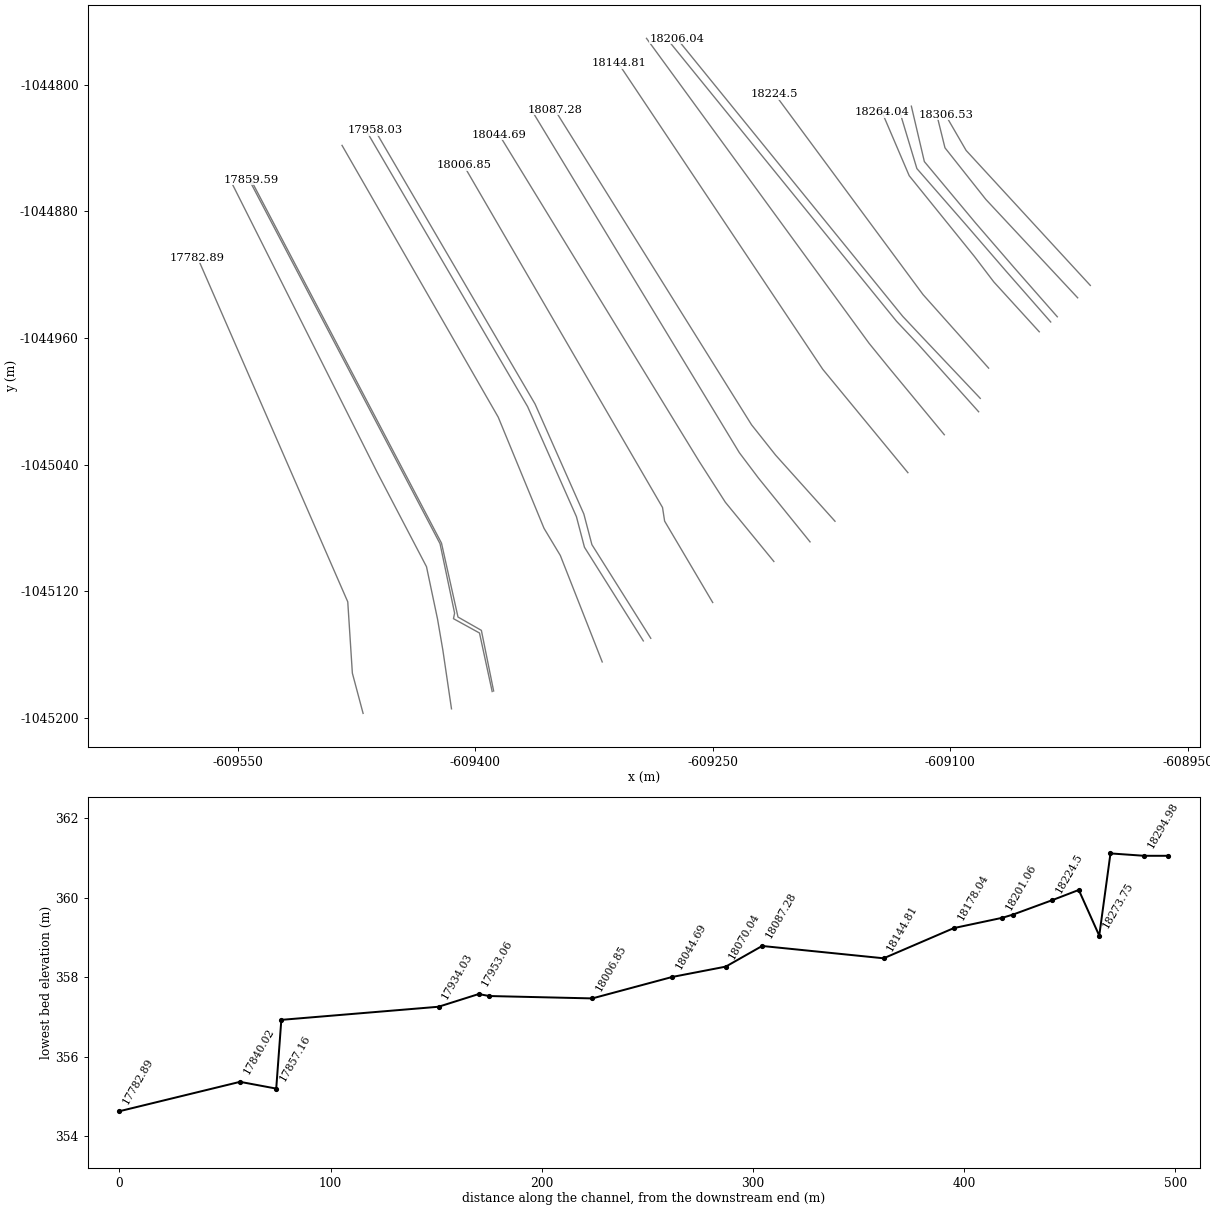
HEC-RAS study PPO_Kvasiny_efektiv.prj: PPO_Kvasiny_efektivita

--- PPO_Kvasiny_efektiv.g09 (geometry) --- (continued)

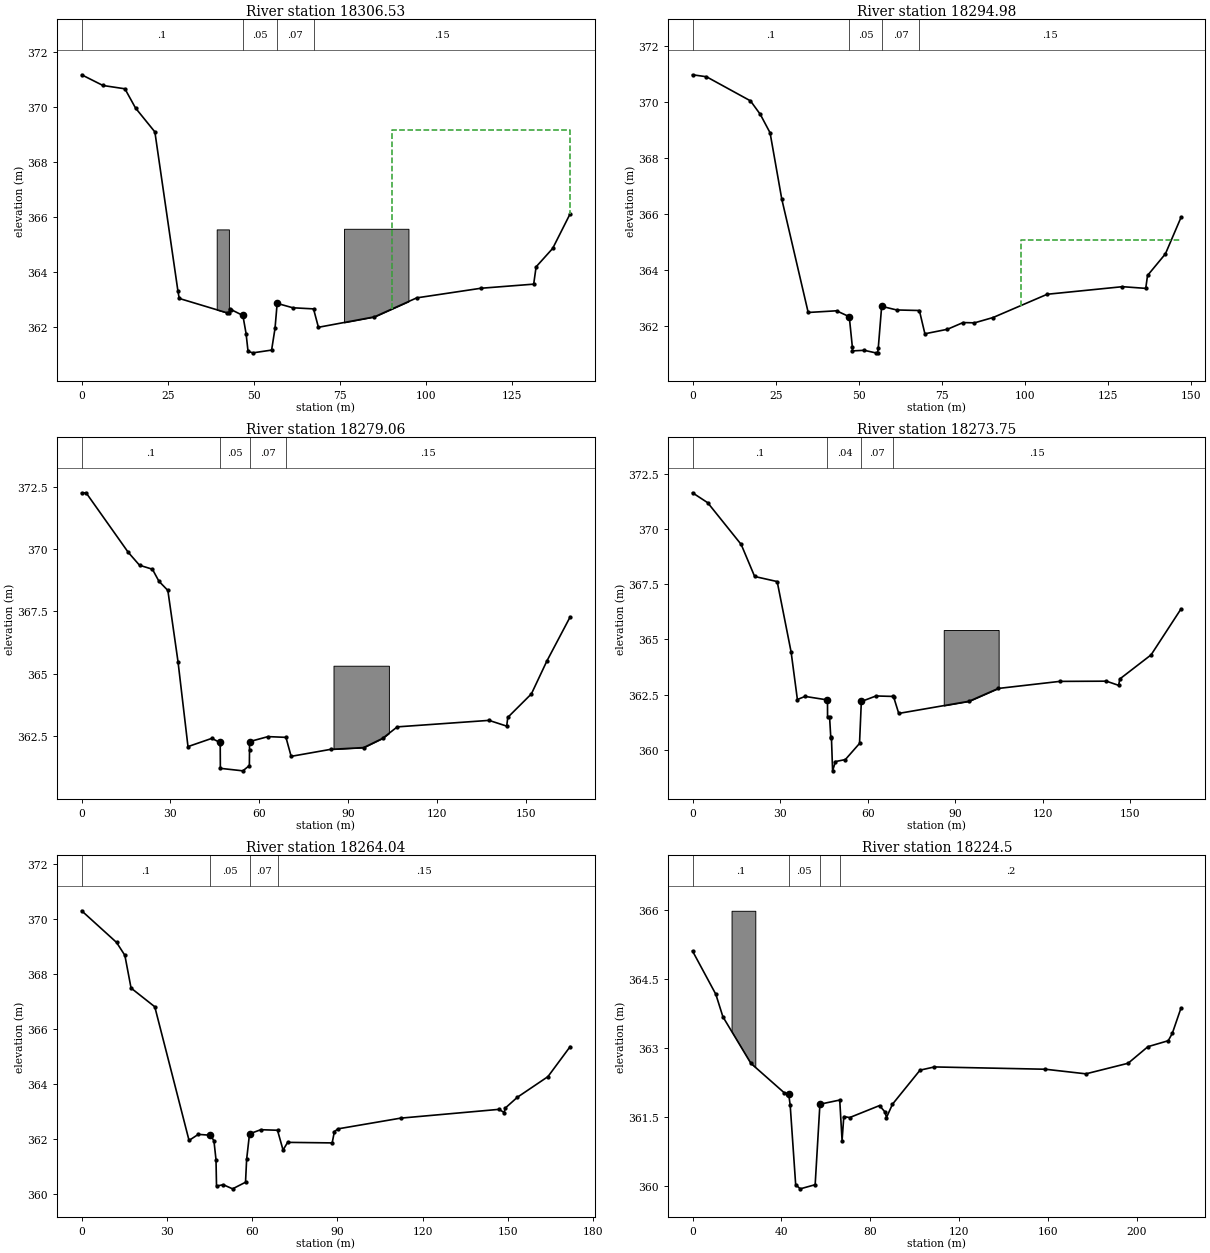
Type RM Length L Ch R = 1 ,18306.53,11.47,11.55,11.69
XS GIS Cut Line= 3
-609011.42359999   -1044926.7722     -609089.892   -1044841.4859
-609102.89469999   -1044819.0525
#Sta/Elev= 28
       0  371.18    6.19  370.79   12.56  370.67   15.64  369.97   21.26   369.1
   27.95  363.31   28.33  363.04    42.1  362.52   42.75  362.52   42.97  362.64
   43.45  362.63   46.81  362.42   47.74  361.76   48.31  361.11   49.74  361.06
   55.15  361.16   56.14  361.95   56.76  362.86   61.31   362.7   67.32  362.66
   68.74  361.99   85.01  362.37   97.26  363.06  115.89  363.41  131.24  363.56
  131.94  364.19  136.75  364.86  141.82  366.12
#Mann= 4 ,-1 , 0
       0      .1       0   46.81     .05       0   56.76     .07       0
   67.32     .15       0
#XS Ineff= 2 , 0
                           90.07          369.16
Permanent Ineff=
       F       F
#Block Obstruct= 2 ,-1
   39.21   42.75365.5524   76.18   94.88 365.575
Bank Sta=46.81,56.76
XS Rating Curve= 0 ,0
Exp/Cntr=0.3,0.1

Type RM Length L Ch R = 1 ,18294.98,16.32,15.92,15.19
XS GIS Cut Line= 4
    -609019.4125   -1044934.5905    -609077.4164   -1044872.4435
    -609103.2397   -1044839.8467    -609108.1081   -1044820.1617
#Sta/Elev= 29
       0  370.98    4.19  370.91   17.42  370.05   20.37  369.57   23.32  368.91
   26.83  366.55   34.78   362.5    43.3  362.56   47.13  362.35   48.05  361.28
    48.1  361.13   51.66  361.15   55.02  361.06   55.67  361.07   55.85  361.23
   56.87  362.72   61.37  362.59   68.21  362.57   69.87  361.74   76.63   361.9
   81.35  362.14   84.78  362.13   90.37  362.32  106.65  363.15  129.28  363.42
  136.27  363.36  136.81  363.82  142.18  364.59  146.87  365.89
#Mann= 4 ,-1 , 0
       0      .1       0   47.13     .05       0   56.87     .07       0
   68.21     .15       0
#XS Ineff= 2 , 0
                           98.75          365.09
Permanent Ineff=
       F       F
Bank Sta=47.13,56.87
XS Rating Curve= 0 ,0
Exp/Cntr=0.3,0.1

Type RM Length L Ch R = 1 ,18279.06,5.31,5.32,5.33
BEGIN DESCRIPTION:
PETRUV JEZ (NADJEZI)
END DESCRIPTION:
XS GIS Cut Line= 5
-609032.27279999   -1044946.5812    -609059.4153   -1044915.6818
     -609083.818   -1044887.4375-609116.26419999   -1044848.5425
-609124.47399999   -1044813.5362
#Sta/Elev= 30
       0  372.24     1.5  372.25   15.72  369.87   19.55  369.35   23.91  369.19
   26.11  368.71   29.13  368.34   32.56  365.49   35.93  362.09   43.99  362.42
   46.63  362.26   46.82   362.2   46.87  361.22   54.47  361.12   56.67  361.33
   56.72  361.94   56.73  362.29   62.98  362.49   69.03  362.46   70.79   361.7
   84.14  361.98   95.28  362.05  101.69  362.42  106.65  362.88  137.65  363.14
  143.62  362.91     144  363.26  151.97   364.2  157.22  365.52  165.06  367.28
#Mann= 4 ,-1 , 0
       0      .1       0   46.63     .05       0   56.73     .07       0
   69.03     .15       0
#Block Obstruct= 1 ,-1
    85.1  103.82365.3277
Bank Sta=46.63,56.73
XS Rating Curve= 0 ,0
Exp/Cntr=0.3,0.1

Type RM Length L Ch R = 1 ,18273.75,10.28,9.7,8.84
XS GIS Cut Line= 5
    -609036.4443   -1044949.8598-609064.65399999   -1044917.7456
-609089.05669999   -1044889.5013-609120.98169999   -1044852.9628
    -609132.1506   -1044815.9045
#Sta/Elev= 30
       0  371.64     5.2  371.19   16.67   369.3   21.28  367.85      29  367.62
   33.77  364.43   35.92  362.28   38.55  362.42   46.23  362.26   46.25  361.49
   46.94   361.5   47.36  360.55   47.57   360.6   47.98  359.05   48.96  359.47
   52.34  359.56    57.2  360.29   57.82  362.19   62.85  362.44    68.5  362.42
   68.85  362.41   70.63  361.65   94.71   362.2  104.69  362.78  125.75   363.1
  141.77  363.11  145.94  362.92  146.35  363.21  157.05   364.3   167.3  366.38
#Mann= 4 ,-1 , 0
       0      .1       0   46.23     .04       0   57.82     .07       0
    68.5     .15       0
#Block Obstruct= 1 ,-1
   86.04  104.85365.4245
Bank Sta=46.23,57.82
XS Rating Curve= 0 ,0
Exp/Cntr=0.3,0.1

Type RM Length L Ch R = 1 ,18264.04,12.48,12.71,12.7
XS GIS Cut Line= 5
    -609043.6799   -1044956.0504    -609072.4114   -1044924.5346
-609084.51969999   -1044908.6165    -609125.8273   -1044857.4816
-609142.94559999   -1044817.4285
#Sta/Elev= 30
       0  370.31   12.28  369.16   15.21  368.69   17.39   367.5   25.74  366.82
    37.8  361.96   41.05  362.18   45.27  362.15   46.56  361.95   47.29  361.26
   47.47   360.3   49.85  360.35   53.13   360.2   57.68  360.44   58.07  361.27
   59.09   362.2   63.06  362.35   68.94  362.33   70.89  361.61    72.5  361.89
   88.18  361.87   88.96  362.28   90.18  362.38  112.24  362.77  146.92  363.09
  148.75  362.97  149.04  363.13  153.37  363.53  164.13  364.28  171.94  365.37
#Mann= 4 ,-1 , 0
       0      .1       0   45.27     .05       0   59.09     .07       0
   68.94     .15       0
Bank Sta=45.27,59.09
XS Rating Curve= 0 ,0
Exp/Cntr=0.3,0.1

Type RM Length L Ch R = 1 ,18224.5 ,18.07,18.46,18.77
XS GIS Cut Line= 3
    -609075.6612   -1044979.0075    -609117.0775    -1044932.579
-609210.79199999   -1044805.8233
#Sta/Elev= 28
       0  365.11   10.49  364.17   13.68  363.68   26.24  362.67   41.24  362.03
   43.28     362   43.96  361.76   46.43  360.03   48.49  359.94    55.2  360.03
   57.34  361.78   66.26  361.87   67.31  360.99   68.09  361.51   70.76  361.49
   84.16  361.75   86.64  361.61    87.3  361.49      90  361.78   102.4  362.52
  108.88  362.59  158.83  362.54  177.06  362.44  196.05  362.67  204.95  363.03
  214.11  363.16  215.94  363.32  219.85  363.87
#Mann= 4 ,-1 , 0
       0      .1       0   43.28     .05       0   57.34     .07       0
   66.26      .2       0
#Block Obstruct= 1 ,-1
   17.57   28.26365.9847
Bank Sta=43.28,57.34
XS Rating Curve= 0 ,0
Exp/Cntr=0.3,0.1

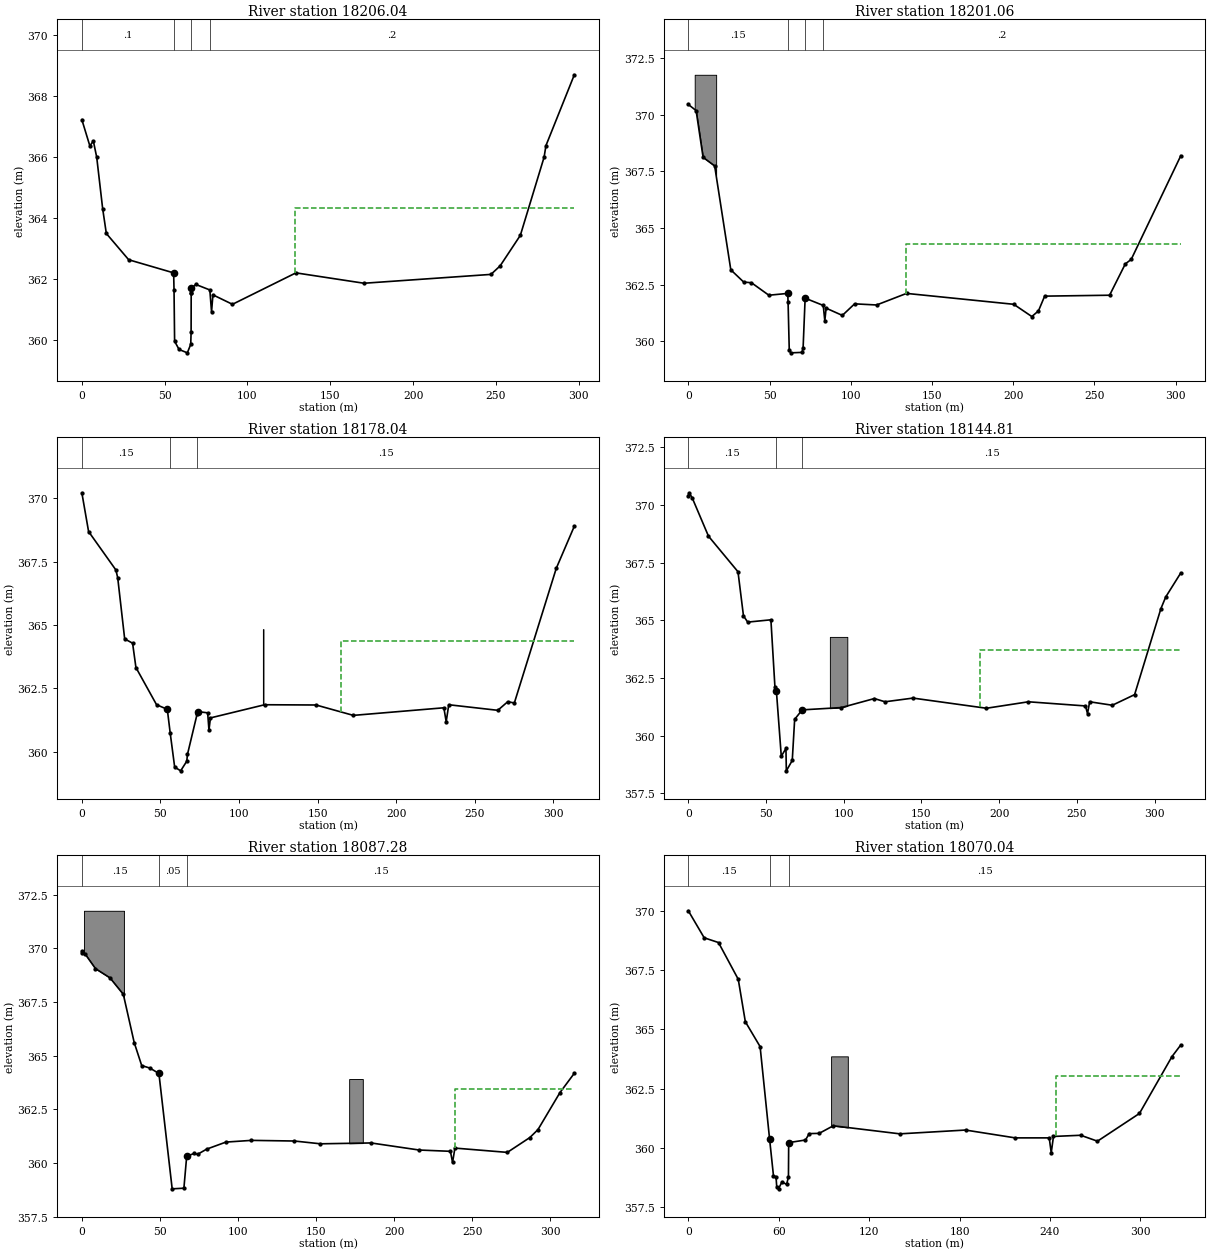
Type RM Length L Ch R = 1 ,18206.04,5.09,4.98,4.99
XS GIS Cut Line= 4
     -609080.951    -1044998.105    -609116.2027    -1044960.872
    -609129.9171   -1044946.3148-609272.49179999   -1044770.8857
#Sta/Elev= 30
       0  367.22    4.83  366.36    6.94  366.52    8.97  365.99   12.57   364.3
   14.78  363.49   28.27  362.63   55.41   362.2   55.65  361.65      56  359.96
    58.7  359.69   63.69  359.58   65.74  359.86   65.96  360.26   66.01  361.53
   66.11  361.55   66.12   361.7   68.84  361.82   77.27  361.64    78.3  360.92
   79.13  361.48   90.93  361.17  129.25   362.2  170.35  361.86     247  362.15
  252.55  362.43  264.74  363.43  279.08  365.99   280.2  366.37  297.33  368.69
#Mann= 4 ,-1 , 0
       0      .1       0   55.41     .05       0   66.12     .07       0
   77.27      .2       0
#XS Ineff= 2 , 0
                           128.7          364.34
Permanent Ineff=
       F       F
Bank Sta=55.41,66.12
XS Rating Curve= 0 ,0
Exp/Cntr=0.5,0.3

Type RM Length L Ch R = 1 ,18201.06,23.86,23.02,22.09
XS GIS Cut Line= 4
     -609081.967   -1045006.5717-609120.09479999    -1044964.001
    -609133.8092   -1044949.4436    -609276.3839   -1044774.0146
#Sta/Elev= 30
       0  370.45     4.8  370.18    9.09  368.12   16.22  367.74   26.16  363.16
    34.1  362.62   38.88  362.59   49.59  362.04   61.21  362.12   61.43  361.72
   62.15  359.61   63.21   359.5   70.02  359.52   70.68  359.73   71.92  361.91
   83.07  361.59   84.04  360.91   84.84  361.47   94.82  361.15  102.39  361.66
  115.93  361.61  134.35  362.12  200.36  361.64   211.5   361.1  215.58  361.35
  219.39     362  259.37  362.04  269.05  363.42  272.69  363.62  303.21  368.19
#Mann= 4 ,-1 , 0
       0     .15       0   61.21     .05       0   71.92     .07       0
   83.07      .2       0
#XS Ineff= 2 , 0
                          133.78          364.29
Permanent Ineff=
       F       F
#Block Obstruct= 1 ,-1
    3.93   17.13371.7588
Bank Sta=61.21,71.92
XS Rating Curve= 0 ,0
Exp/Cntr=0.5,0.3

Type RM Length L Ch R = 1 ,18178.04,32.9,33.23,33.2
XS GIS Cut Line= 4
    -609103.6508   -1045021.0811-609138.55079999   -1044978.8772
    -609151.1605   -1044963.3531    -609291.7859   -1044770.6855
#Sta/Elev= 30
       0  370.22    4.28  368.69   21.67  367.17   22.82  366.86   27.24  364.45
   32.28  364.28    34.4  363.32   47.53  361.85   54.36  361.67   56.22360.7247
   59.04  359.39   62.85  359.24   66.74  359.62   67.19  359.89   73.29 361.474
   73.82  361.58   80.03  361.53   80.86  360.85   81.81  361.33  116.27  361.85
  148.98  361.84   172.7  361.43   230.3  361.73  231.77  361.18  233.41  361.85
   264.6  361.63  270.94  361.97  275.13  361.92  301.82  367.24  313.29   368.9
#Mann= 3 ,-1 , 0
       0     .15       0   56.22     .05       0   73.29     .15       0
#XS Ineff= 2 , 0
                           165.1          364.36
Permanent Ineff=
       F       F
#Block Obstruct= 1 ,-1
  115.17  115.55 364.834
Bank Sta=54.36,73.82
XS Rating Curve= 0 ,0
Exp/Cntr=0.3,0.1

Type RM Length L Ch R = 1 ,18144.81,57.17,57.54,57.11
XS GIS Cut Line= 3
    -609126.6578   -1045045.0457    -609180.4545    -1044979.726
-609309.43919999   -1044786.5799
#Sta/Elev= 30
       0   370.4     .58  370.52     2.5   370.3   12.98  368.64   31.96   367.1
   35.49  365.19   38.21  364.92   53.14  365.02   55.75  362.09   56.66  361.95
   59.82  359.11   62.82  359.45   63.07  358.48   66.88  358.93   68.42  360.71
   73.26  361.12   98.47  361.22  119.71  361.61  126.56  361.47  144.56  361.63
  191.84  361.19  218.85  361.47  255.53  361.29  256.86  360.96  258.24  361.47
  272.83  361.32  287.16  361.78  304.06   365.5   307.2  366.01  316.88  367.05
#Mann= 3 , 0 , 0
       0     .15       0   56.66     .05       0   73.26     .15       0
#XS Ineff= 2 , 0
                          187.93           363.7
Permanent Ineff=
       F       F
#Block Obstruct= 1 ,-1
   91.09   102.3364.2794
Bank Sta=56.66,73.26
XS Rating Curve= 0 ,0
Exp/Cntr=0.3,0.1

Type RM Length L Ch R = 1 ,18087.28,17.9,17.24,16.41
XS GIS Cut Line= 4
    -609172.6953   -1045075.7374-609210.22019999   -1045033.9658
    -609225.4338   -1045014.7835-609349.78819999   -1044815.6841
#Sta/Elev= 30
       0  369.87     .34  369.79     1.9  369.76    8.72  369.06   17.99  368.63
   26.56  367.86   33.53  365.61   38.32  364.54   43.62  364.42   49.35  364.17
   57.84  358.79   65.35  358.82   67.14  360.31   71.92  360.44   74.13   360.4
   79.88  360.64   92.26  360.97  108.58  361.05  136.13  361.02  152.81  360.89
   185.2  360.93  215.99   360.6  236.03  360.54   237.4  360.02  238.91  360.69
  272.48  360.49  286.86  361.18  292.07  361.55  306.19  363.28  315.38  364.18
#Mann= 3 , 0 , 0
       0     .15       0   49.35     .05       0   67.14     .15       0
#XS Ineff= 2 , 0
                          239.06          363.45
Permanent Ineff=
       F       F
#Block Obstruct= 2 ,-1
    1.34   26.94371.7567  171.18  179.93363.9105
Bank Sta=49.35,67.14
XS Rating Curve= 0 ,0
Exp/Cntr=0.3,0.1

Type RM Length L Ch R = 1 ,18070.04,26.03,25.34,24.56
XS GIS Cut Line= 4
    -609188.4695   -1045088.7556-609221.08839999   -1045048.4074
    -609233.1209    -1045032.432    -609365.3255   -1044814.4483
#Sta/Elev= 30
       0     370   10.54  368.86   20.03  368.66   33.14  367.11   37.84  365.32
   47.64  364.27    53.9360.3909   56.53  358.81   58.19  358.78    58.7  358.34
   59.86  358.27   62.11  358.56   65.23  358.46   66.45  358.77   66.61  360.22
   77.76  360.33   80.25   360.6   86.85  360.61   96.19  360.93  140.38  360.59
  183.97  360.75  216.94  360.42  239.52  360.42  240.85  359.79  242.33  360.48
  260.41  360.53  271.53  360.28  299.39  361.45  320.98  363.85  326.83  364.34
#Mann= 3 ,-1 , 0
       0     .15       0    53.9     .05       0   66.61     .15       0
#XS Ineff= 2 , 0
                          243.91          363.04
Permanent Ineff=
       F       F
#Block Obstruct= 1 ,-1
   94.75  105.86363.8593
Bank Sta=53.9,66.61
XS Rating Curve= 0 ,0
Exp/Cntr=0.3,0.1

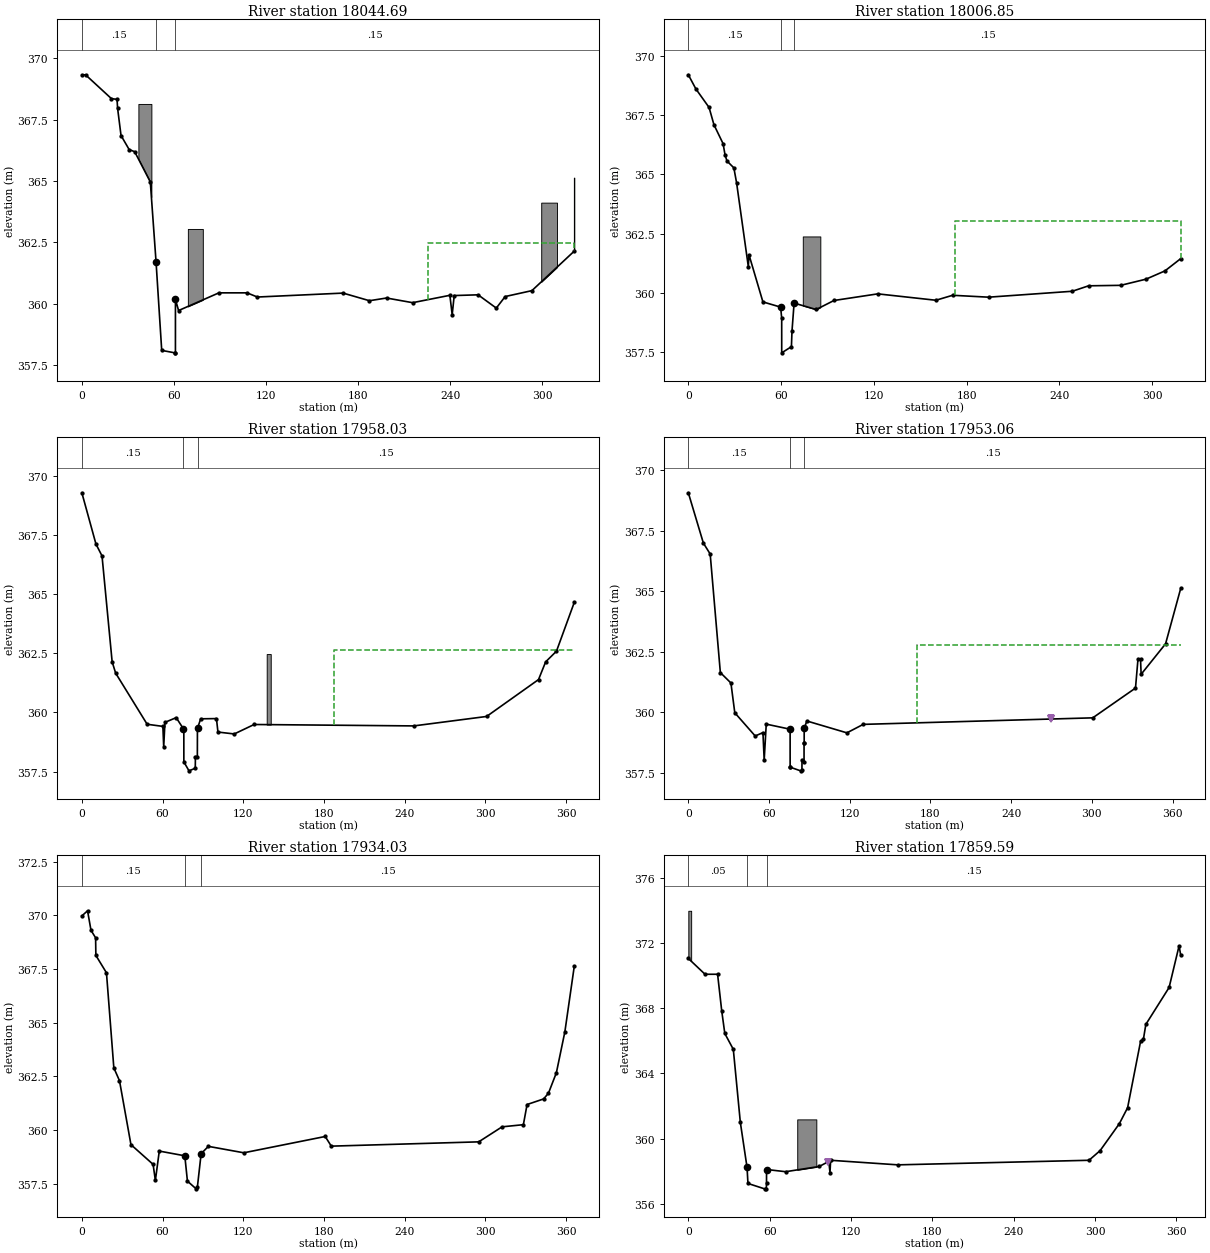
Type RM Length L Ch R = 1 ,18044.69,39.68,37.85,34.98
XS GIS Cut Line= 4
    -609211.3246   -1045101.1375    -609241.9703   -1045063.7315
    -609258.5068   -1045037.9345    -609384.8456   -1044831.5591
#Sta/Elev= 30
       0  369.31    2.39  369.32   19.27  368.35   22.94  368.32   23.29  367.96
   25.53  366.85   30.81  366.28   34.45  366.19   44.62  364.96   48.36  361.71
   52.05  358.11   60.57  358.01   60.99  358.01      61  360.18   63.04  359.73
   89.32  360.45  107.65  360.45   114.4  360.28  170.26  360.44  187.43  360.13
  198.58  360.24  215.58  360.05  239.86  360.35  241.36  359.56  242.68  360.34
  258.25  360.37  270.11  359.83  275.91   360.3  293.32  360.54  320.97  362.15
#Mann= 3 , 0 , 0
       0     .15       0   48.36     .05       0      61     .15       0
#XS Ineff= 2 , 0
                          225.92          362.47
Permanent Ineff=
       F       F
#Block Obstruct= 4 ,-1
   36.85   45.32 368.134   69.09   78.84363.0494  299.39  309.67364.1195
  320.66  320.97365.1357
Bank Sta=48.36,61
XS Rating Curve= 0 ,0
Exp/Cntr=0.3,0.1

Type RM Length L Ch R = 1 ,18006.85,47.57,48.82,45.88
XS GIS Cut Line= 4
-609249.95389999   -1045127.0667-609280.33489999   -1045075.6377
    -609281.6579   -1045067.0388    -609407.3352   -1044850.7415
#Sta/Elev= 30
       0  369.21    4.91  368.61   13.43  367.83   16.58   367.1    22.5   366.3
   23.75  365.83      25  365.57   29.46  365.28   31.22  364.65   38.82  361.11
   39.25  361.61   48.26  359.62   59.73   359.4   60.41  358.92   60.42  357.47
    66.7  357.73   67.07  358.39   68.43  359.57   82.73   359.3   94.22  359.68
  122.56  359.96  160.18  359.69  170.96   359.9  194.24  359.82  248.41  360.07
  258.94   360.3  279.72  360.32  296.07  360.58  308.35  360.93  318.59  361.45
#Mann= 3 , 0 , 0
       0     .15       0   59.73     .05       0   68.43     .15       0
#XS Ineff= 2 , 0
                          172.58          363.03
Permanent Ineff=
       F       F
#Block Obstruct= 1 ,-1
   74.05    85.4362.3846
Bank Sta=59.73,68.43
XS Rating Curve= 0 ,0
Exp/Cntr=0.3,0.1

Type RM Length L Ch R = 1 ,17958.03,4.98,4.96,5.01
XS GIS Cut Line= 5
-609289.07889999   -1045149.6626    -609326.2672   -1045090.5068
    -609331.3531   -1045071.1643-609362.16739999   -1045001.6811
     -609463.228   -1044828.8855
#Sta/Elev= 30
       0  369.29   10.49  367.12   14.99  366.62   22.52  362.14   25.14  361.66
   48.53   359.5   60.23  359.41   60.84  358.54   61.76  359.58   70.13  359.78
   75.55 359.302    75.8   359.3   75.82  357.91   79.63  357.53    84.3  357.64
   84.42  358.13   85.85  358.13   85.91  359.33   86.02359.3391   88.33  359.73
  100.05  359.74  101.16  359.17  113.29  359.09  128.04  359.49  246.69  359.43
  300.86  359.83  339.45  361.39  344.75  362.14  352.79  362.59  366.06  364.66
#Mann= 3 ,-1 , 0
       0     .15       0   75.55     .04       0   86.02     .15       0
#XS Ineff= 2 , 0
                          187.53          362.64
Permanent Ineff=
       F       F
#Block Obstruct= 1 ,-1
   137.4   140.4362.4691
Bank Sta=75.55,86.02
XS Rating Curve= 0 ,0
Exp/Cntr=0.5,0.3

Type RM Length L Ch R = 1 ,17953.06,18.09,19.04,21.99
XS GIS Cut Line= 5
    -609293.7773   -1045151.3166    -609330.9657   -1045092.1607
    -609336.0515   -1045072.8183    -609366.8658   -1045003.3351
-609467.92639999   -1044830.5395
#Sta/Elev= 30
       0  369.07    11.2  366.99   16.25  366.54   23.81  361.64   31.67  361.21
   34.54  359.98   49.71  359.02   55.47  359.16   56.39  358.03   57.93  359.51
   75.67   359.3   75.68  357.75   75.77  357.73   83.46  357.58   84.45  357.61
   84.51  358.04   86.02  357.94   86.03  358.73   86.12  358.74   86.13  359.33
   88.09  359.64  117.88  359.15     130   359.5  300.62  359.77  332.39     361
  334.26  362.21  336.13  362.19  336.58  361.57  354.75  362.83  366.06  365.13
#Mann= 3 , 0 , 0
       0     .15       0   75.67     .04       0   86.13     .15       0
Levee=0,,,-1,269.75,359.76,,
#XS Ineff= 2 , 0
                          169.75           362.8
Permanent Ineff=
       F       F
Bank Sta=75.67,86.13
XS Rating Curve= 0 ,0
Exp/Cntr=0.5,0.3

Type RM Length L Ch R = 1 ,17934.03,65.98,74.44,72.11
XS GIS Cut Line= 5
    -609319.7439   -1045164.6074-609346.21489999    -1045097.348
    -609356.5102   -1045080.2014-609385.44929999   -1045009.9555
    -609484.1037    -1044838.313
#Sta/Elev= 30
       0  369.98    4.24  370.22     6.8  369.31   10.23  368.96   10.42  368.14
    18.3  367.33   23.78   362.9   27.99   362.3   36.51  359.32   52.99   358.4
   54.67  357.65   57.58  359.02   76.56   358.8   78.51  357.62   84.98  357.26
   85.93  357.35    88.7358.8978   94.07  359.24  120.45  358.94  180.97   359.7
   185.5  359.25  295.12  359.45   312.5  360.15  328.34  360.25  331.09  361.19
  343.38  361.45  347.01  361.72  352.88  362.67   359.2  364.58  366.23  367.65
#Mann= 3 ,-1 , 0
       0     .15       0   76.56     .04       0    88.7     .15       0
#XS Ineff= 2 , 0
Permanent Ineff=
       F       F
Bank Sta=76.56,88.7
XS Rating Curve= 0 ,0
Exp/Cntr=0.3,0.1

Type RM Length L Ch R = 1 ,17859.59,2.45,2.42,1.42
XS GIS Cut Line= 5
-609388.34189999    -1045182.943     -609396.089   -1045144.6568
    -609410.8528    -1045136.243-609421.27679999   -1045089.5522
-609541.73739999   -1044859.9101
#Sta/Elev= 30
       0  371.05   12.33  370.08   21.59  370.08   24.63  367.84   26.91  366.45
   33.18  365.48   38.37     361   43.32  358.24   43.98  357.26   56.23  356.93
   57.52  356.95   57.67  357.31    57.7  358.11   58.31  358.11   71.77  357.98
   96.51   358.3  103.64  358.61  104.48  357.93  104.97  358.68  154.54   358.4
  295.51  358.68  303.69  359.27  317.87  360.92  323.98   361.9  333.53  365.96
  335.64   366.1  337.44  367.01  354.59  369.27  361.94  371.82  363.21  371.23
#Mann= 3 , 0 , 0
       0     .05       0   43.32     .05       0   58.31     .15       0
Levee=0,,,-1,103,358.59,,
#Block Obstruct= 2 ,-1
       0     2.1373.9706   80.33   94.41361.1868
Bank Sta=43.32,58.31
XS Rating Curve= 0 ,0
Exp/Cntr=0.3,0.1

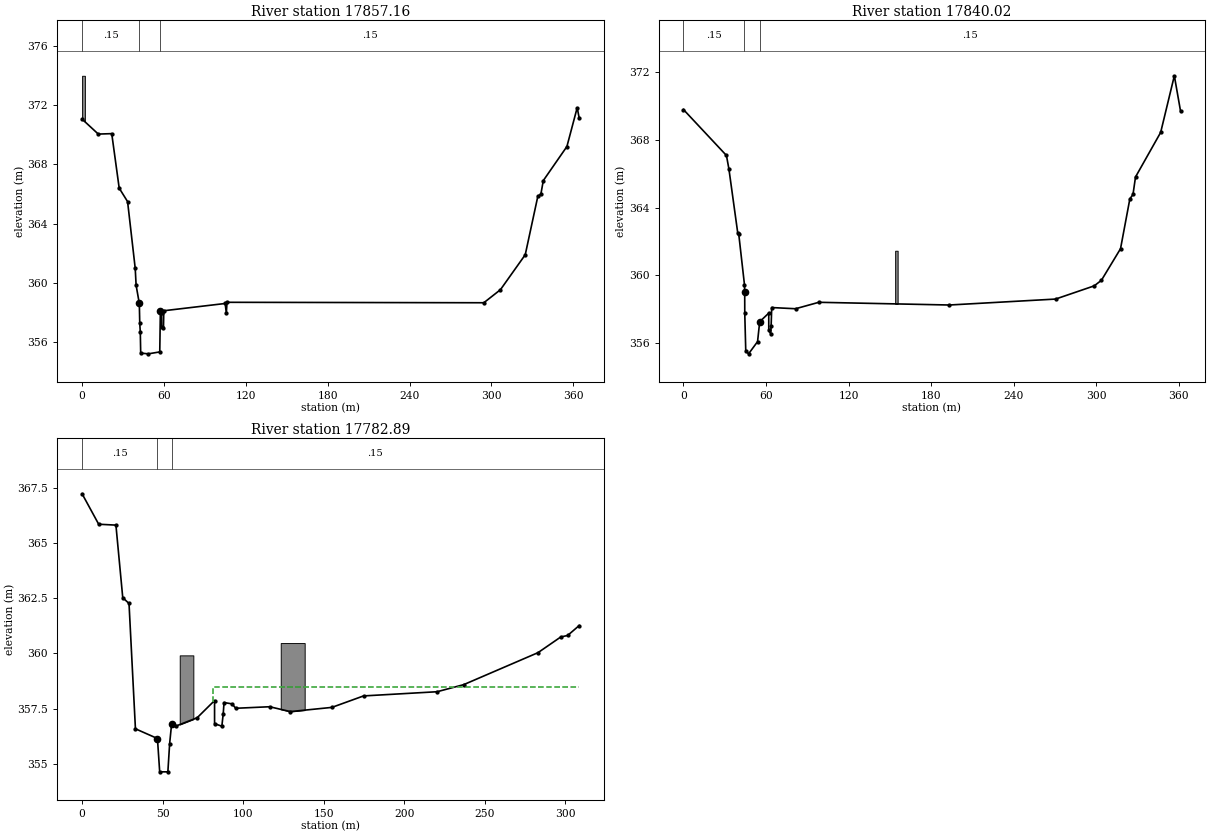
Type RM Length L Ch R = 1 ,17857.16,23.71,17.14,11.38
XS GIS Cut Line= 6
    -609389.2674   -1045183.2983-609397.27959999   -1045146.3236
-609413.71029999   -1045137.2749    -609412.9959   -1045133.7824
-609422.20239999   -1045089.9074    -609542.6629   -1044860.2654
#Sta/Elev= 30
       0  371.05   11.88  370.04   21.73  370.07   27.19  366.39   33.34  365.48
   38.94  360.97   39.59  359.83   41.94   358.6   42.26  357.26   42.66  356.66
   42.95  355.25   48.54   355.2   56.92  355.33   57.37  358.08   58.25  357.99
   58.31  357.04   59.65  356.96   59.87  358.11  104.85   358.6   105.7  357.95
  106.21  358.68  294.39  358.65  306.56  359.53  324.74  361.89     334  365.85
   336.2  365.98  337.98   366.9  355.28   369.2  362.81  371.82   364.3  371.12
#Mann= 3 , 0 , 0
       0     .15       0   41.94     .05       0   57.37     .15       0
#Block Obstruct= 1 ,-1
       0    2.05373.9771
Bank Sta=41.94,57.37
XS Rating Curve= 0 ,0
Exp/Cntr=0.3,0.1

Type RM Length L Ch R = 1 ,17840.02,57.92,57.13,54.77
XS GIS Cut Line= 6
-609414.96049999    -1045194.222    -609420.4036   -1045157.2118
-609423.78489999   -1045137.4997    -609430.7512   -1045104.4406
    -609461.8814    -1045044.887    -609553.0165   -1044863.5194
#Sta/Elev= 30
       0  369.78   31.27  367.07   33.07  366.27   39.48   362.5   40.23  362.42
   44.37  359.45   44.54  359.04   44.59  357.75   45.31  355.55   47.35  355.37
   53.89  356.09   55.44357.2657   62.02  357.77   62.03  356.76   63.43  356.55
   63.75  357.01   64.18   358.1   81.51  358.03   98.41  358.41   193.3  358.25
   270.5   358.6  298.63  359.38  303.86  359.71  317.73  361.57  324.51  364.51
   326.8  364.77  328.62   365.8  346.91  368.43  356.85  371.77  361.37  369.68
#Mann= 3 ,-1 , 0
       0     .15       0   44.37     .05       0   55.44     .15       0
#Block Obstruct= 1 ,-1
   153.9  155.72361.4517
Bank Sta=44.54,55.44
XS Rating Curve= 0 ,0
Exp/Cntr=0.3,0.1

Type RM Length L Ch R = 1 ,17782.89,62.55,62.87,61.97
XS GIS Cut Line= 4
    -609470.8038    -1045197.095-609477.57719999    -1045171.695
    -609480.4835   -1045126.6469    -609575.3674   -1044909.2278
#Sta/Elev= 30
       0  367.23   10.31  365.85   21.01  365.81   25.25  362.52   29.14  362.26
   33.12  356.58   46.79  356.14   48.18  354.63   53.26  354.63   54.36  355.91
   55.59  356.81   58.12   356.7   71.43  357.08   82.25  357.86   82.26  356.81
   86.78   356.7   87.64  357.27   88.13  357.77   93.12  357.71   95.37  357.51
  116.46  357.58  129.29  357.36  155.07  357.55  174.76  358.07  220.41  358.26
  236.89  358.58  283.05  360.03  297.17  360.74  301.47  360.81  308.65  361.26
#Mann= 3 , 0 , 0
       0     .15       0   46.79     .05       0   55.59     .15       0
#XS Ineff= 2 , 0
                           81.03          358.46
Permanent Ineff=
       F       F
#Block Obstruct= 2 ,-1
  123.33   138.2360.4653   60.62   69.08 359.908
Bank Sta=46.79,55.59
XS Rating Curve= 0 ,0
Exp/Cntr=0.3,0.1