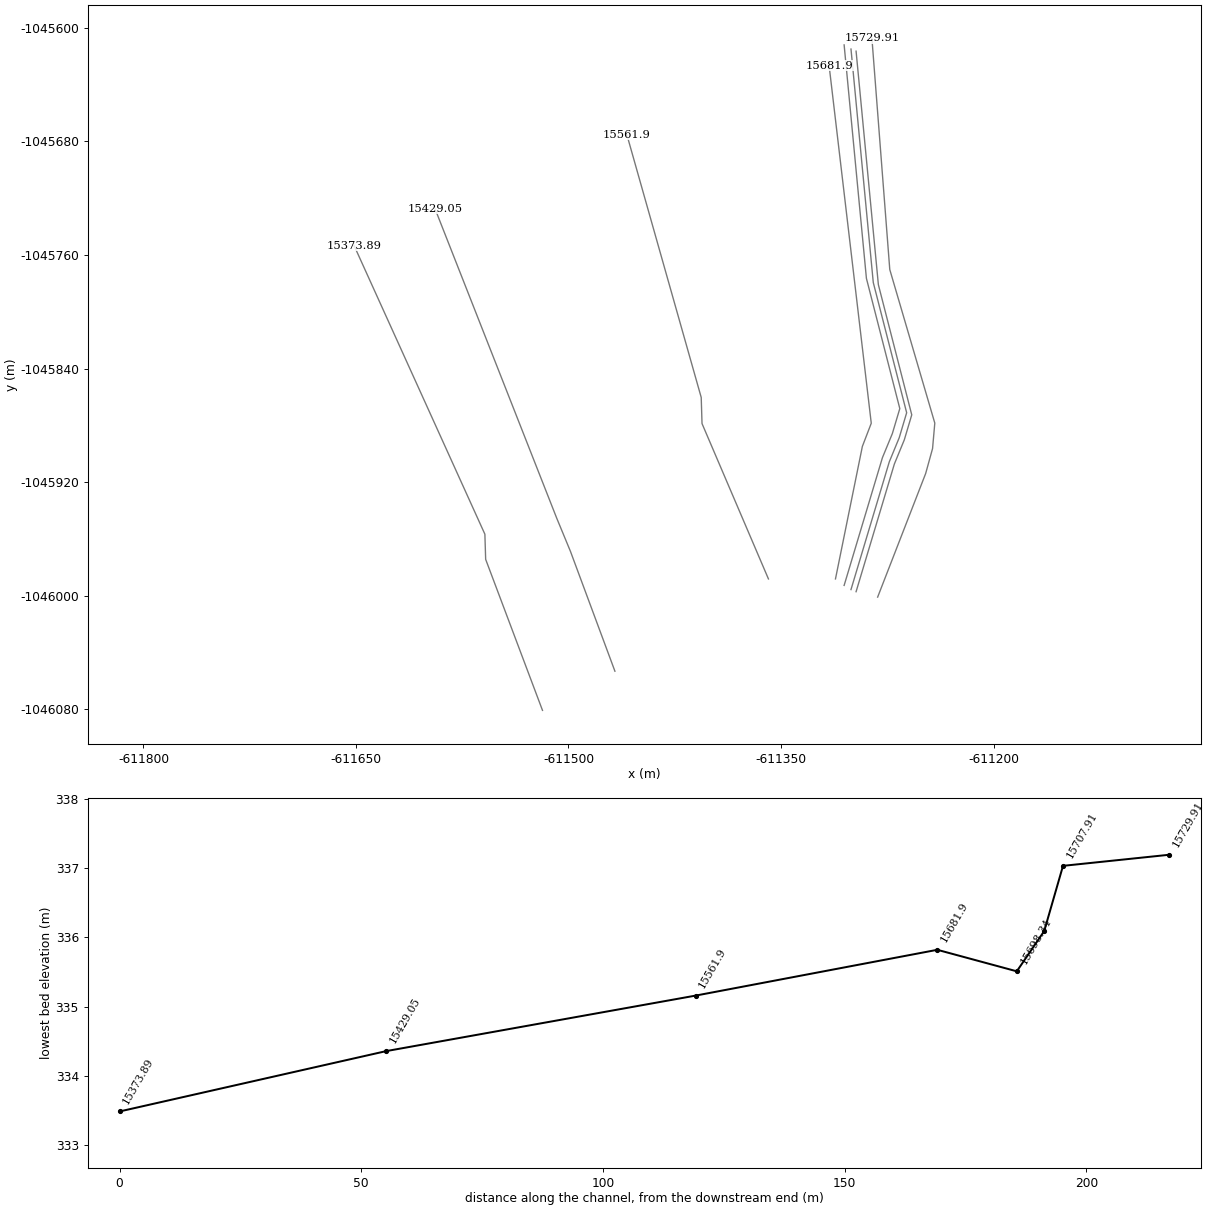
HEC-RAS study PPO_Kvasiny_efektiv.prj: PPO_Kvasiny_efektivita

--- PPO_Kvasiny_efektiv.g10 (geometry) --- (continued)

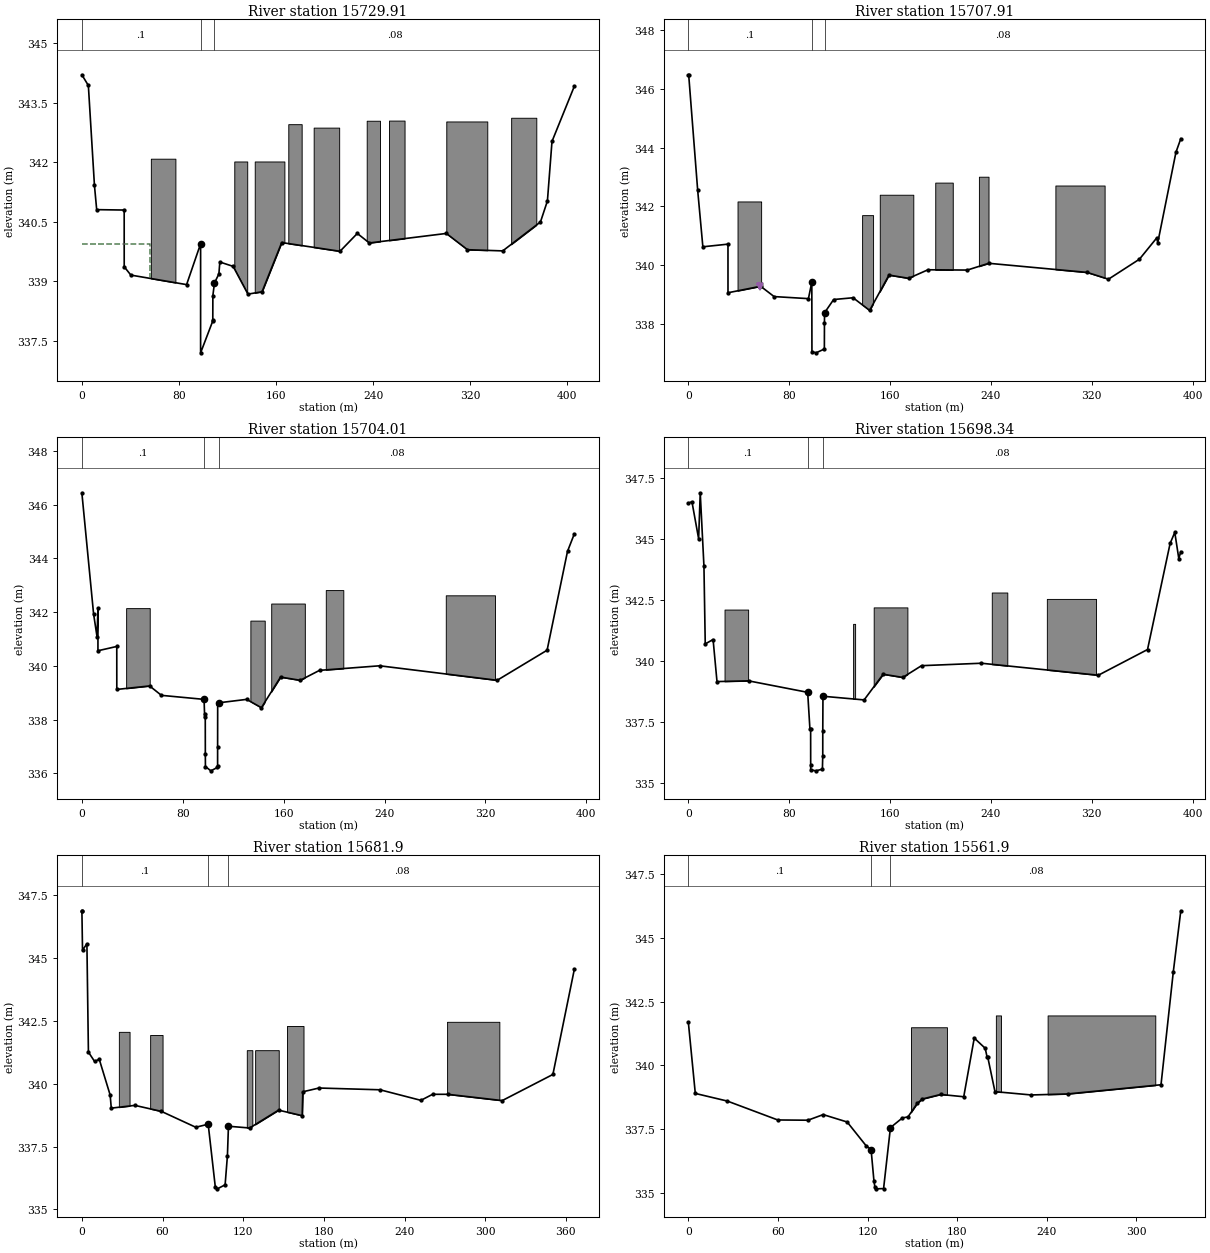
Type RM Length L Ch R = 1 ,15729.91,23.06,22.01,19.38
XS GIS Cut Line= 6
    -611281.7885   -1046000.8759-611247.89779999   -1045913.8258
    -611243.0385   -1045896.2879    -611241.4543   -1045878.3214
    -611273.2296   -1045770.2109    -611285.8491   -1045607.2642
#Sta/Elev= 30
       0   344.2    5.36  343.93   10.38  341.41   12.22   340.8   34.88  340.79
    34.9  339.36   40.38  339.15    86.3  338.91   97.84  339.94   97.85  337.19
  107.83  337.99  107.89  338.03  107.94  338.63  109.25  338.95  112.92  339.18
  113.68  339.48  124.63  339.37  136.84  338.67  148.48  338.73  164.67  339.97
  212.71  339.75  226.96   340.2  236.88  339.96   300.3   340.2  317.72  339.79
  346.77  339.76  377.88  340.49   383.6  341.02  387.37  342.52  405.77  343.91
#Mann= 3 , 0 , 0
       0      .1       0   97.84    .035       0  109.25     .08       0
#XS Ineff= 2 , 0
           56.28  339.94
Permanent Ineff=
       F       F
#Block Obstruct= 9 ,-1
   56.85   77.08342.0844  125.59  136.26342.0143  142.44  166.88342.0143
  170.09  181.11342.9549     191  212.02 342.868   234.7  245.66343.0414
  253.06  265.89343.0455  300.27  334.05343.0232  353.72  374.44343.1166
Bank Sta=97.84,109.25
XS Rating Curve= 0 ,0
Exp/Cntr=0.3,0.1

Type RM Length L Ch R = 1 ,15707.91,3.89,3.89,3.9
BEGIN DESCRIPTION:
15901.9  PF 200 KAMENNÝ PEVNÝ JEZ S NÁPLATKY V KVASINÁCH,NADJEZI
END DESCRIPTION:
XS GIS Cut Line= 6
    -611297.0154   -1045997.0692-611269.98739999   -1045907.1252
    -611262.9829    -1045890.143    -611257.7215   -1045872.5269
    -611281.2811   -1045780.8493    -611297.0154   -1045616.4002
#Sta/Elev= 30
       0  346.46     .29  346.47     7.4  342.56   11.53  340.63   31.45  340.72
   31.46  339.07   57.35  339.29   68.02  338.94   95.25  338.87   97.93  339.43
   98.03  337.07   101.3  337.03  107.88  337.16  107.95  338.03  108.02  338.39
  115.25  338.84  130.67   338.9  143.77  338.47  159.13  339.67  174.73  339.56
  190.03  339.85  221.21  339.84  238.26  340.07  316.29  339.76  333.17  339.53
  357.76  340.21  371.62  340.94  372.23  340.76  386.69  343.84  390.53   344.3
#Mann= 3 , 0 , 0
       0      .1       0   97.93    .035       0  108.02     .08       0
Levee=-1,56.54,339.26,0,,,,
#Block Obstruct= 6 ,-1
   39.03   57.74342.1694  137.81  146.51341.7051  151.82  178.41342.3976
  195.81   209.7342.8094  230.44  238.06343.0097  291.09  330.12342.7108
Bank Sta=97.93,108.02
XS Rating Curve= 0 ,0
Exp/Cntr=0.3,0.1

Type RM Length L Ch R = 1 ,15704.01,5.49,5.67,5.52
XS GIS Cut Line= 6
    -611300.6086    -1045995.581    -611273.5806   -1045905.6369
-611266.57609999   -1045888.6548    -611261.3147   -1045871.0387
    -611284.8744   -1045779.3611    -611300.6086    -1045614.912
#Sta/Elev= 30
       0  346.44    9.31  341.93   12.04  341.08   12.75  342.14   12.76  340.56
   27.69  340.72   27.71  339.12   53.73  339.25   63.09   338.9   96.92  338.75
   97.39  338.08   97.86  338.22   97.92   336.7   97.99  336.25  102.33  336.09
  107.55  336.22  107.65  336.28  107.66  336.99  107.71  338.56   108.6338.6232
  130.67  338.75  142.36  338.44  157.56  339.58  173.15  339.46  188.47  339.83
  236.17     340  329.33  339.46  368.94  340.58  385.12  344.26  390.53  344.91
#Mann= 3 , 0 , 0
       0      .1       0   96.92    .035       0   108.6     .08       0
#Block Obstruct= 5 ,-1
   35.12   53.83342.1467  288.59  327.61342.6234  193.44  207.33342.8185
  150.16  176.82342.3174  133.64  145.02341.6818
Bank Sta=96.92,108.6
XS Rating Curve= 0 ,0
Exp/Cntr=0.3,0.1

Type RM Length L Ch R = 1 ,15698.34,15.5,16.44,16.98
XS GIS Cut Line= 6
-611305.45039999   -1045992.6441-611278.42249999      -1045902.7
    -611271.4179   -1045885.7179    -611266.1565   -1045868.1018
    -611289.7162   -1045776.4242-611305.45039999   -1045611.9751
#Sta/Elev= 30
       0  346.46    2.89  346.51    8.18     345    9.45  346.88   12.39  343.88
   13.42   340.7   19.64  340.88   22.74  339.16   47.73  339.19   94.65  338.72
   96.42  337.23      97  337.23   97.03  335.75   97.05  335.55  101.17  335.51
  106.33  335.58  106.61  336.13  106.62  337.12  106.77  338.56   139.4  338.41
  154.52  339.46  170.07  339.33  184.92  339.81  232.43  339.91  325.16  339.42
  364.15  340.47  382.07  344.81  385.76  345.26  388.95  344.19  390.53  344.47
#Mann= 3 , 0 , 0
       0      .1       0   94.65    .035       0  106.77     .08       0
#Block Obstruct= 5 ,-1
   28.71   47.42342.1049  284.31  323.33  342.54  240.64  252.95342.8019
     147  173.73342.1931  130.67  132.27  341.52
Bank Sta=94.65,106.77
XS Rating Curve= 0 ,0
Exp/Cntr=0.3,0.1

Type RM Length L Ch R = 1 ,15681.9 ,45.84,50,51.56
XS GIS Cut Line= 4
-611311.56309999   -1045988.0799    -611292.5808   -1045894.7576
-611286.29859999   -1045878.4296-611316.05409999   -1045626.6029
#Sta/Elev= 30
       0  346.88     .04  346.88     .49  345.31    3.76  345.57    4.88  341.26
    9.43  340.89   12.96  340.97   21.06  339.55   21.88  339.03   39.45  339.14
    59.2   338.9   84.71  338.27   93.97  338.39   99.23  335.91  100.76  335.82
  106.56  335.98  108.28  337.14  109.04  338.31  124.79  338.24  146.31  338.95
   163.9  338.73  164.34  339.68  176.38  339.83   221.8  339.76  252.17  339.34
  260.89  339.58  272.13  339.58  312.67  339.33  350.37  340.37  366.31  344.55
#Mann= 3 , 0 , 0
       0      .1       0   93.97    .035       0  109.04     .08       0
#XS Ineff= 2 , 0
Permanent Ineff=
       F       F
#Block Obstruct= 6 ,-1
   27.52   35.49342.0646  271.67  310.54342.4639  152.57  164.87342.2979
    50.8   60.03341.9404  122.69  126.81341.3354  128.89  146.45341.3354
Bank Sta=93.97,109.04
XS Rating Curve= 0 ,0
Exp/Cntr=0.3,0.1

Type RM Length L Ch R = 1 ,15561.9 ,53.46,64.01,67.42
XS GIS Cut Line= 4
    -611358.8707   -1045988.0799    -611405.7524    -1045878.675
    -611406.3202   -1045860.2644    -611458.7895   -1045675.2631
#Sta/Elev= 30
       0   341.7    4.67   338.9   26.16   338.6   59.88  337.86   80.08  337.85
   90.31  338.07  106.36  337.78  119.03  336.85  122.37   336.7  124.27  335.48
  124.95  335.22  125.54  335.16  130.74  335.17  135.33  337.56  143.34  337.94
  147.09  337.98  153.27  338.51  156.65  338.68  168.99  338.86  184.41  338.77
  191.45  341.07  198.78  340.67  200.07  340.32   200.5  340.32  205.32  338.97
  229.63  338.84  253.98  338.88  316.49  339.24  324.73  343.67  329.74  346.06
#Mann= 3 , 0 , 0
       0      .1       0  122.37     .05       0  135.33     .08       0
#Block Obstruct= 3 ,-1
  205.92  209.34341.9575  240.57  312.66341.9575  149.11  173.16341.4943
Bank Sta=122.37,135.33
XS Rating Curve= 0 ,0
Exp/Cntr=0.3,0.1

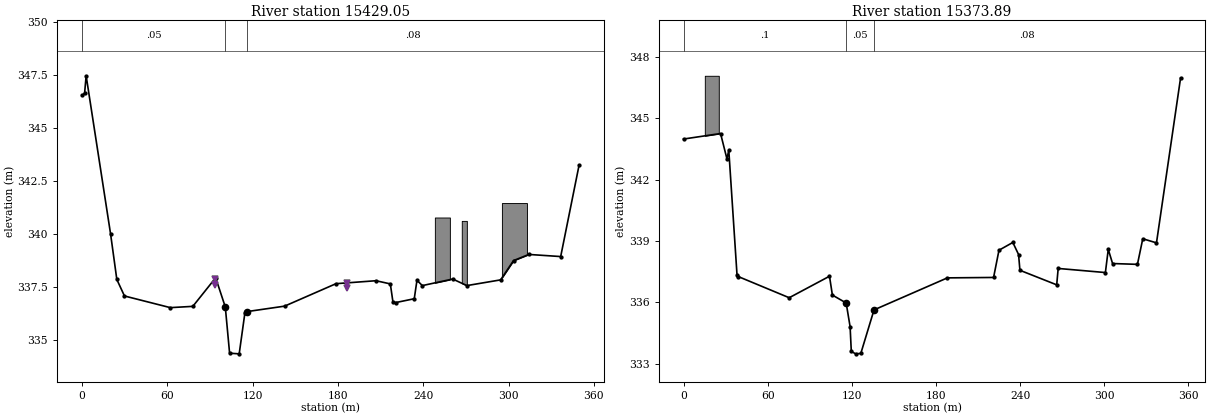
Type RM Length L Ch R = 1 ,15429.05,57.83,55.16,52.38
XS GIS Cut Line= 4
    -611467.2355   -1046053.0626    -611498.6151   -1045968.6868
-611508.26709999   -1045945.4035     -611594.204   -1045727.3864
#Sta/Elev= 30
       0  346.55    1.78  346.66    2.86  347.48   20.04  340.02   24.44  337.87
   29.81  337.09   62.06  336.54   77.89   336.6   93.96  337.95  100.74  336.57
  103.76  334.39  110.51  334.36  114.54   336.3  115.69  336.35  142.43  336.61
   178.6  337.67  206.71  337.81  216.82  337.66  218.69  336.79  220.66  336.78
  233.65  336.96  235.55  337.83  239.34  337.58   260.7  337.89  270.65  337.58
  294.39  337.85  303.46  338.76  314.24  339.05  336.64  338.95  349.57  343.26
#Mann= 3 , 0 , 0
       0     .05       0  100.74     .05       0  115.69     .08       0
Levee=-1,93.46,337.63,-1,185.99,337.47,,
#Block Obstruct= 3 ,-1
  248.14   258.7 340.793  267.07  270.64340.6323   295.3  312.91341.4743
Bank Sta=100.74,115.69
XS Rating Curve= 0 ,0
Exp/Cntr=0.3,0.1

Type RM Length L Ch R = 1 ,15373.89,10.94,373.89,55.99
XS GIS Cut Line= 4
    -611518.3532   -1046080.6446    -611558.4674   -1045974.2846
    -611559.0168   -1045956.5783    -611651.2961   -1045753.4009
#Sta/Elev= 30
       0  343.98   26.39  344.25   30.94  343.01   32.25  343.44   38.14  337.33
   39.14  337.26   75.35  336.23  104.09  337.28  106.16  336.36  115.99335.9734
  118.79  334.82  119.65  333.61  122.73  333.49  126.44  333.51  135.86335.6363
  188.19   337.2  221.15  337.22     225  338.55  234.88  338.93  238.98  338.34
  239.94  337.57  266.18  336.86  267.23  337.66  300.91  337.46  302.96  338.59
  306.04   337.9  323.77  337.86  327.58  339.11  337.36  338.91  354.54  346.96
#Mann= 3 , 0 , 0
       0      .1       0  115.99     .05       0  135.86     .08       0
#Block Obstruct= 1 ,-1
   15.15   25.12347.0693
Bank Sta=115.99,135.86
XS Rating Curve= 0 ,0
Exp/Cntr=0.3,0.1
LCMann Table=0

--- PPO_Kvasiny_efektiv.g11 (geometry) ---

Geom Title=N-Q20
Program Version=5.03

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
River Reach=Bela            ,Bela_reach

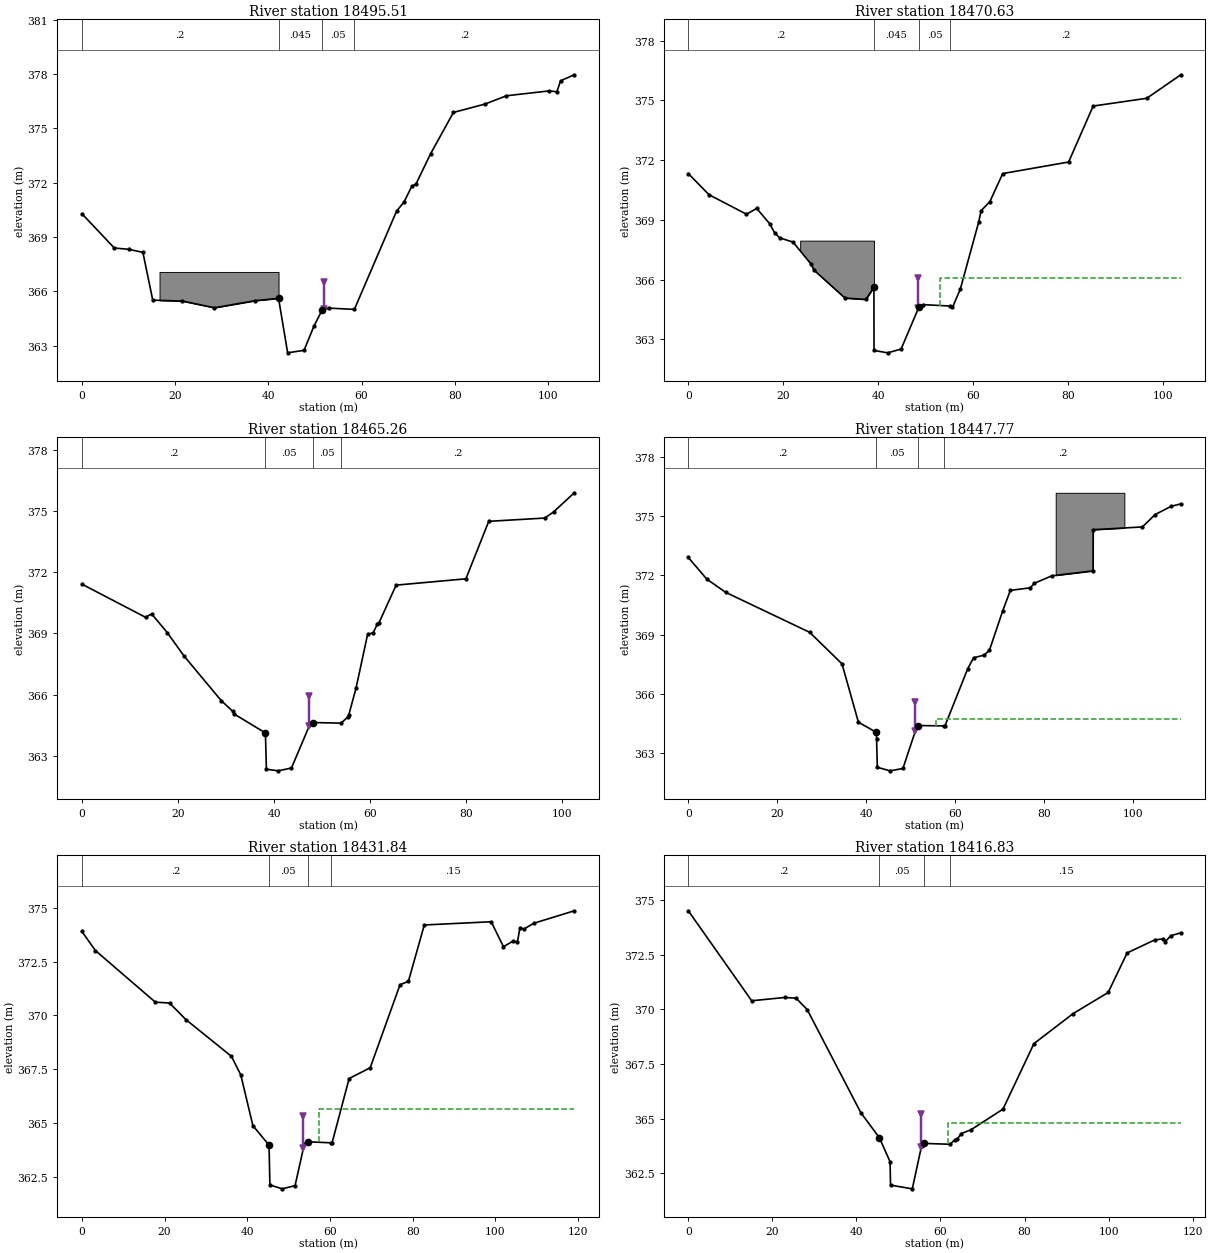
Type RM Length L Ch R = 1 ,18495.51,25.6,24.88,23.57
XS GIS Cut Line= 4
    -608887.9529   -1044774.1613    -608917.6792   -1044750.0879
    -608934.0835    -1044737.917    -608970.0669   -1044707.7544
#Sta/Elev= 27
       0  370.29    6.96  368.39   10.03  368.32   13.09  368.15   15.21  365.51
   21.57  365.46   28.43  365.09   37.14  365.48   42.19  365.61   44.14   362.6
   47.66  362.74   49.82   364.1   51.54  364.96   53.01  365.07   58.45     365
   67.51  370.43    69.1  370.93    70.8  371.82   71.62   371.9   74.81   373.6
    79.7  375.88   86.45  376.34   91.06   376.8  100.25  377.07  101.89  377.02
  102.68  377.63  105.63  377.96
#Mann= 4 ,-1 , 0
       0      .2       0   42.19    .045       0   51.54     .05       0
   58.45      .2       0
Levee=0,,,-1,52.01,366.5074,,	2157
#Block Obstruct= 1 ,-1
   16.66   42.19 367.069
Bank Sta=42.19,51.54
XS Rating Curve= 0 ,0
Exp/Cntr=0.3,0.1

Type RM Length L Ch R = 1 ,18470.63,5.16,5.37,5.75
XS GIS Cut Line= 4
-608906.65179999   -1044793.0242    -608930.3372   -1044772.7807
-608945.32779999   -1044759.5411    -608983.9917   -1044723.9844
#Sta/Elev= 30
       0  371.32    4.35  370.26   12.24  369.28    14.4  369.57   17.14   368.8
   18.23  368.32   19.27  368.09   22.05  367.88   25.79  366.79   26.47  366.47
   32.99  365.07   37.38     365      39365.5917   39.08  365.61    39.1  362.44
   41.97  362.32    44.8  362.51   48.59  364.64   49.46  364.74   55.09  364.67
   55.62   364.6   57.27  365.52   61.13  368.88   61.66  369.46   63.49  369.91
    66.2  371.32   80.07   371.9   85.24  374.71   96.53   375.1  103.69  376.28
#Mann= 4 ,-1 , 0
       0      .2       0      39    .045       0   48.59     .05       0
   55.09      .2       0
Levee=0,,,-1,48.46,366.0615,,	2157
#XS Ineff= 2 , 0
                           53.07          366.06
Permanent Ineff=
       F       F
#Block Obstruct= 1 ,-1
   23.55   39.08 367.954
Bank Sta=39.08,48.59
XS Rating Curve= 0 ,0
Exp/Cntr=0.3,0.1

Type RM Length L Ch R = 1 ,18465.26,17.65,17.49,17.14
XS GIS Cut Line= 2
    -608910.5632   -1044796.3117    -608988.7089   -1044730.0063
#Sta/Elev= 28
       0  371.42   13.27  369.79   14.51  369.96   17.78  369.04   21.24   367.9
   29.02   365.7   31.41  365.18   31.74  365.04    38.2  364.12    38.4  362.34
   40.87  362.26   43.62   362.4    47.5  364.56   48.04  364.63   53.93   364.6
    55.3  364.89   55.55  365.01   57.04   366.3   59.46  368.95   60.65  369.04
   61.48  369.46   61.85  369.53    65.4  371.37   79.92  371.68   84.67   374.5
   96.34  374.66   98.15  374.96  102.48   375.9
#Mann= 4 ,-1 , 0
       0      .2       0    38.2     .05       0   48.04     .05       0
   53.93      .2       0
Levee=0,,,-1,47.29,365.9167,,	2157
Bank Sta=38.2,48.04
XS Rating Curve= 0 ,0
Exp/Cntr=0.3,0.1

Type RM Length L Ch R = 1 ,18447.77,15.66,15.93,16.64
XS GIS Cut Line= 4
-608918.60229999   -1044812.6923-608948.38219999   -1044787.3387
    -608962.1406   -1044775.1678    -609000.7698   -1044738.6552
#Sta/Elev= 30
       0  372.91    4.15  371.81     8.4  371.14   27.27  369.11   34.52  367.51
   38.21  364.55   42.26  364.03   42.29  363.69   42.46  362.26   45.32  362.08
   48.21   362.2   51.24  364.26   51.65  364.38   57.48  364.36   57.63  364.35
   62.76  367.26   64.08  367.82   66.39  367.95   67.64   368.2   70.61  370.19
   72.34  371.24   76.82  371.37   77.73   371.6   81.68  371.98   90.92  372.23
   90.94  374.32     102  374.46  104.88  375.09  108.48  375.51  110.63  375.63
#Mann= 4 ,-1 , 0
       0      .2       0   42.26     .05       0   51.65     .05       0
   57.48      .2       0
Levee=0,,,-1,51.03,365.5753,,	2157
#XS Ineff= 2 , 0
                           55.69          364.73
Permanent Ineff=
       F       F
#Block Obstruct= 1 ,-1
   82.53   97.95376.1941
Bank Sta=42.26,51.65
XS Rating Curve= 0 ,0
Exp/Cntr=0.3,0.1

Type RM Length L Ch R = 1 ,18431.84,14.94,15.01,15.06
XS GIS Cut Line= 4
-608926.42619999   -1044827.1558    -608957.9395   -1044799.6768
-608973.81459999   -1044786.9768    -609015.6187   -1044748.3474
#Sta/Elev= 30
       0   373.9    3.28  373.01   17.77  370.61    21.2  370.57   25.16   369.8
   36.17  368.09   38.42  367.23   41.35  364.87   45.17  363.98   45.26  363.94
   45.46  362.11   48.45  361.93   51.55  362.08   53.78  364.01   54.56  364.12
   60.23  364.07   60.48  364.06   64.62  367.06   69.71  367.56   76.92  371.42
   78.95  371.58   82.79   374.2   98.96  374.35  101.93  373.19  104.34  373.46
  105.32  373.41  105.89  374.06  106.87  374.01  109.27  374.28  119.06  374.86
#Mann= 4 ,-1 , 0
       0      .2       0   45.17     .05       0   54.56     .05       0
   60.23     .15       0
Levee=0,,,-1,53.56,365.304,,	2157
#XS Ineff= 2 , 0
                           57.23          365.62
Permanent Ineff=
       F       F
Bank Sta=45.17,54.56
XS Rating Curve= 0 ,0
Exp/Cntr=0.3,0.1

Type RM Length L Ch R = 1 ,18416.83,19.51,19.31,18.8
XS GIS Cut Line= 4
    -608933.7448   -1044840.0106    -608967.9937   -1044810.7893
-608985.98539999   -1044796.5017    -609023.5562   -1044764.7517
#Sta/Elev= 27
       0  374.51   15.08  370.39   22.91  370.54   25.64  370.51   28.28  369.99
   41.04  365.27   45.46  364.12   48.01  363.02   48.12  361.95    53.3  361.78
   55.49  363.73   56.19  363.86   62.29  363.82   63.37  364.02   64.02  364.06
   64.91  364.31   67.23  364.48   74.88  365.43   82.25  368.43   91.55   369.8
   99.91  370.77  104.42  372.58  111.02  373.18  112.87  373.22  113.53   373.1
   114.8  373.37  117.19   373.5
#Mann= 4 ,-1 , 0
       0      .2       0   45.46     .05       0   56.19     .05       0
   62.29     .15       0
Levee=0,,,-1,55.47,365.2081,,	2157
#XS Ineff= 2 , 0
                            61.8          364.79
Permanent Ineff=
       F       F
Bank Sta=45.46,56.19
XS Rating Curve= 0 ,0
Exp/Cntr=0.3,0.1

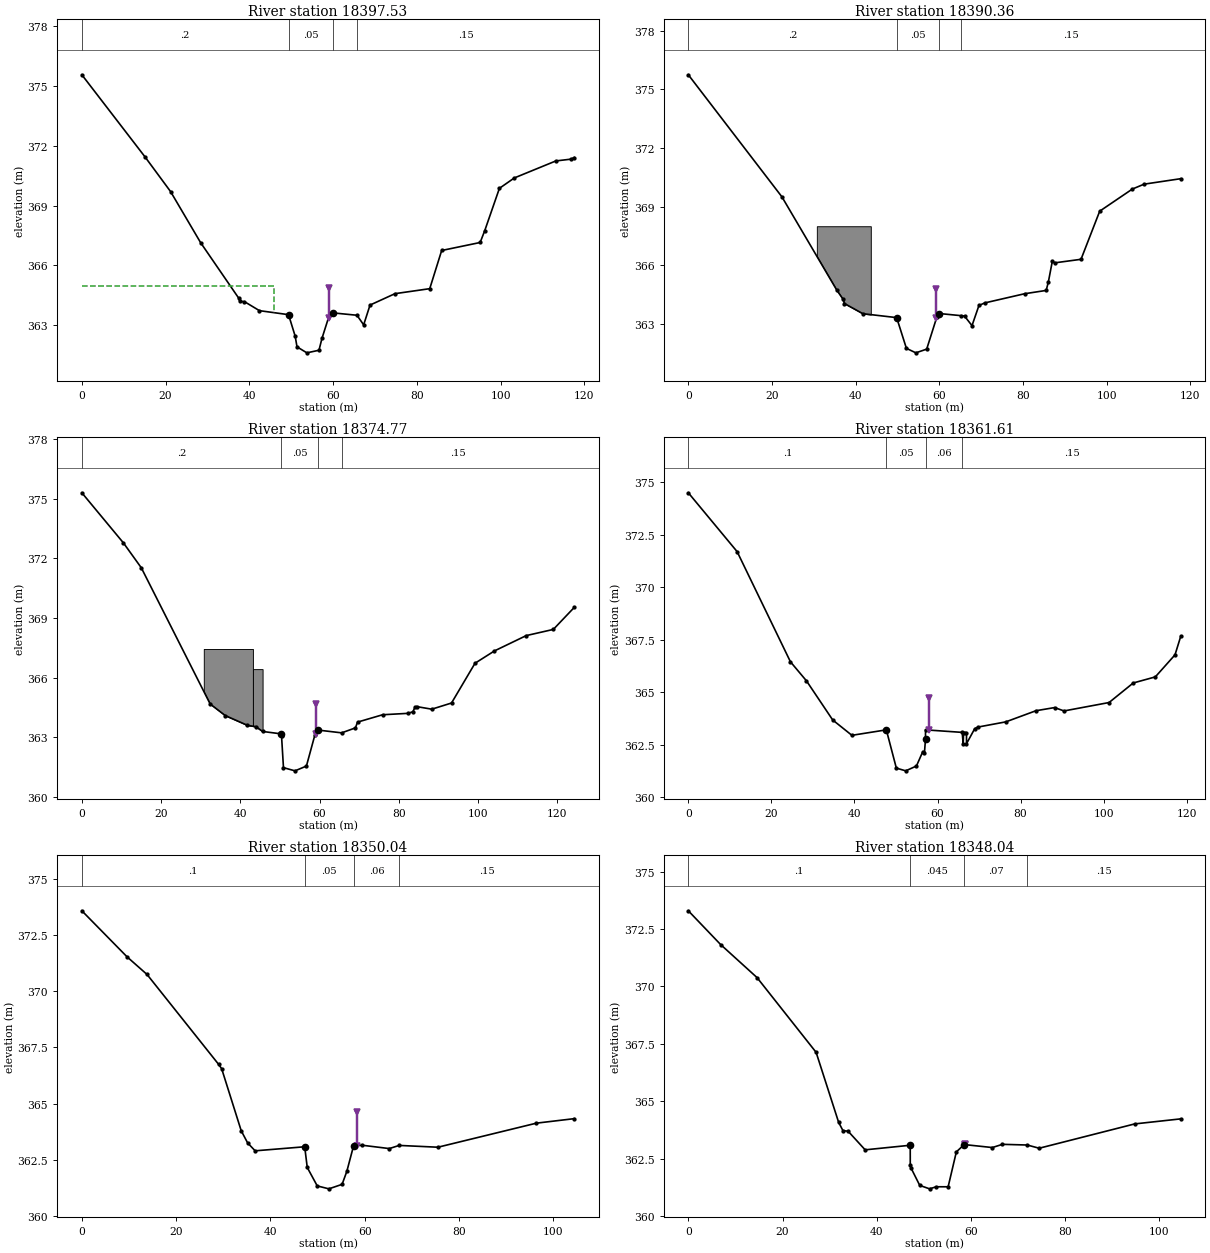
Type RM Length L Ch R = 1 ,18397.53,7.24,7.17,6.9
XS GIS Cut Line= 4
-608943.77299999   -1044858.6939-608978.04789999   -1044827.7227
    -608998.6854   -1044810.2602    -609033.0813   -1044782.2143
#Sta/Elev= 29
       0  375.54   15.13  371.42   21.18   369.7   28.37  367.14   37.48  364.36
   37.74   364.2   38.84  364.19   42.41  363.74   49.36  363.54   50.95  362.46
   51.38  361.93   53.74  361.63   56.63  361.76   57.34  362.35   59.02  363.46
   59.91  363.63    65.7  363.51    67.3  363.03   68.82  364.02   74.78  364.59
   83.08  364.84   85.93  366.75   95.12  367.15   96.23  367.75   99.72  369.86
  103.29  370.38   113.2  371.23  116.84  371.32  117.61   371.4
#Mann= 4 ,-1 , 0
       0      .2       0   49.36     .05       0   59.91     .05       0
    65.7     .15       0
Levee=0,,,-1,58.91,364.8894,,	2157
#XS Ineff= 2 , 0
            45.8  364.98
Permanent Ineff=
       F       F
Bank Sta=49.36,59.91
XS Rating Curve= 0 ,0
Exp/Cntr=0.3,0.1

Type RM Length L Ch R = 1 ,18390.36,15.99,15.59,15.07
XS GIS Cut Line= 2
    -608947.5425   -1044864.1187-609036.10399999   -1044786.5639
#Sta/Elev= 27
       0  375.74   22.38   369.5    35.5  364.73   36.92  364.29   37.32  364.05
   41.73  363.53    49.8  363.33   52.13  361.76   54.39  361.53   56.98  361.72
   59.42  363.37   59.95  363.54   65.19  363.43   66.02  363.41   67.81  362.92
   69.47  363.95   70.84  364.08   80.38  364.55   85.55  364.72   86.08  365.17
      87   366.2   87.62  366.13   93.87  366.31   98.34  368.77  106.14   369.9
  108.95  370.15  117.72  370.43
#Mann= 4 ,-1 , 0
       0      .2       0    49.8     .05       0   59.95     .05       0
   65.19     .15       0
Levee=0,,,-1,59.32,364.8086,,	2157
#Block Obstruct= 1 ,-1
   30.72   43.62368.0001
Bank Sta=49.8,59.95
XS Rating Curve= 0 ,0
Exp/Cntr=0.3,0.1

Type RM Length L Ch R = 1 ,18374.77,12.72,13.16,13.09
XS GIS Cut Line= 3
-608959.05689999   -1044877.1776-609013.50209999   -1044826.1352
-609048.81949999   -1044791.2347
#Sta/Elev= 30
       0   375.3   10.49  372.78      15  371.53   32.38  364.68   36.18   364.1
   41.76  363.61   43.91  363.54   45.61   363.3   50.25  363.18    50.4  363.05
   50.88  361.48   53.79  361.32   56.67  361.56   58.83  363.14   59.59  363.37
   65.56  363.23   69.04  363.48   69.57  363.77   75.91  364.14   82.26  364.21
   83.54  364.29   84.04  364.51   84.48  364.55    88.3  364.42   93.29  364.73
   99.22  366.73  104.13  367.35  112.15  368.12  118.98  368.43  124.28  369.54
#Mann= 4 ,-1 , 0
       0      .2       0   50.25     .05       0   59.59     .05       0
   65.56     .15       0
Levee=0,,,-1,59.01,364.6792,,	2157
#Block Obstruct= 2 ,-1
   30.77   43.17367.4476   43.17   45.61366.4337
Bank Sta=50.25,59.59
XS Rating Curve= 0 ,0
Exp/Cntr=0.3,0.1

Type RM Length L Ch R = 1 ,18361.61,12.22,11.56,10.47
XS GIS Cut Line= 3
    -608967.6932   -1044884.2694     -609015.221   -1044843.1214
-609052.62759999   -1044801.8585
#Sta/Elev= 30
       0  374.49   11.75  371.69   24.58  366.45   28.45  365.54   34.76  363.68
   39.38  362.95   47.67  363.21   50.08  361.39   52.34  361.26   54.92  361.49
   56.46  362.18   56.84   362.1    57.1  362.77    57.1  363.21   65.93  363.09
   66.18  362.54   66.26  363.08   66.97  363.08   66.97  362.55   68.93  363.26
   69.65  363.34   76.43  363.59   83.69  364.12   88.17  364.27   90.45  364.11
  101.29  364.51  107.11  365.44  112.43  365.73  117.17  366.78  118.56  367.67
#Mann= 4 ,-1 , 0
       0      .1       0   47.67     .05       0    57.1     .06       0
   65.93     .15       0
Levee=0,,,-1,57.89,364.7152,,	2157
Bank Sta=47.67,57.1
XS Rating Curve= 0 ,0
Exp/Cntr=0.3,0.1

Type RM Length L Ch R = 1 ,18350.04,2,2,2.21
XS GIS Cut Line= 4
    -608978.2241   -1044895.2065    -609008.2817   -1044865.0536
-609022.72899999   -1044851.2234-609048.56549999   -1044818.2857
#Sta/Elev= 22
       0  373.57     9.6  371.52   13.82  370.74   28.98  366.75   29.65  366.55
    33.8  363.79   35.16  363.25   36.75   362.9   47.26  363.08    47.8  362.16
   49.92  361.34   52.39  361.21   55.19  361.41    56.2  361.99   57.62  363.12
   57.71  363.12   59.38  363.15    65.2     363    67.3  363.14   75.51  363.06
   96.41  364.13  104.44  364.33
#Mann= 4 ,-1 , 0
       0      .1       0   47.26     .05       0   57.71     .06       0
    67.3     .15       0
Levee=0,,,-1,58.38,364.6284,,	2157
Bank Sta=47.26,57.71
XS Rating Curve= 0 ,0
Exp/Cntr=0.5,0.3

Type RM Length L Ch R = 1 ,18348.04,7.11,6.87,7.11
XS GIS Cut Line= 4
    -608980.1664   -1044896.0904     -609009.671   -1044866.4922
-609024.11829999    -1044852.662-609051.48649999   -1044819.8097
#Sta/Elev= 23
       0   373.3    6.85  371.83   14.58  370.39   27.13  367.13   31.91  364.08
   32.82  363.72   33.93  363.69   37.54  362.88   47.11  363.08   47.12  362.22
    47.3  362.08   49.13  361.33   51.22  361.18   52.62  361.27   55.16  361.27
    56.9  362.79   58.56  363.11   64.54  362.98   66.68  363.12   71.95  363.09
   74.49  362.95   94.77  364.01  104.55  364.23
#Mann= 4 ,-1 , 0
       0      .1       0   47.11    .045       0   58.56     .07       0
   71.95     .15       0
Levee=0,,,-1,58.72,363.12,,
Bank Sta=47.11,58.56
XS Rating Curve= 0 ,0
Exp/Cntr=0.5,0.3

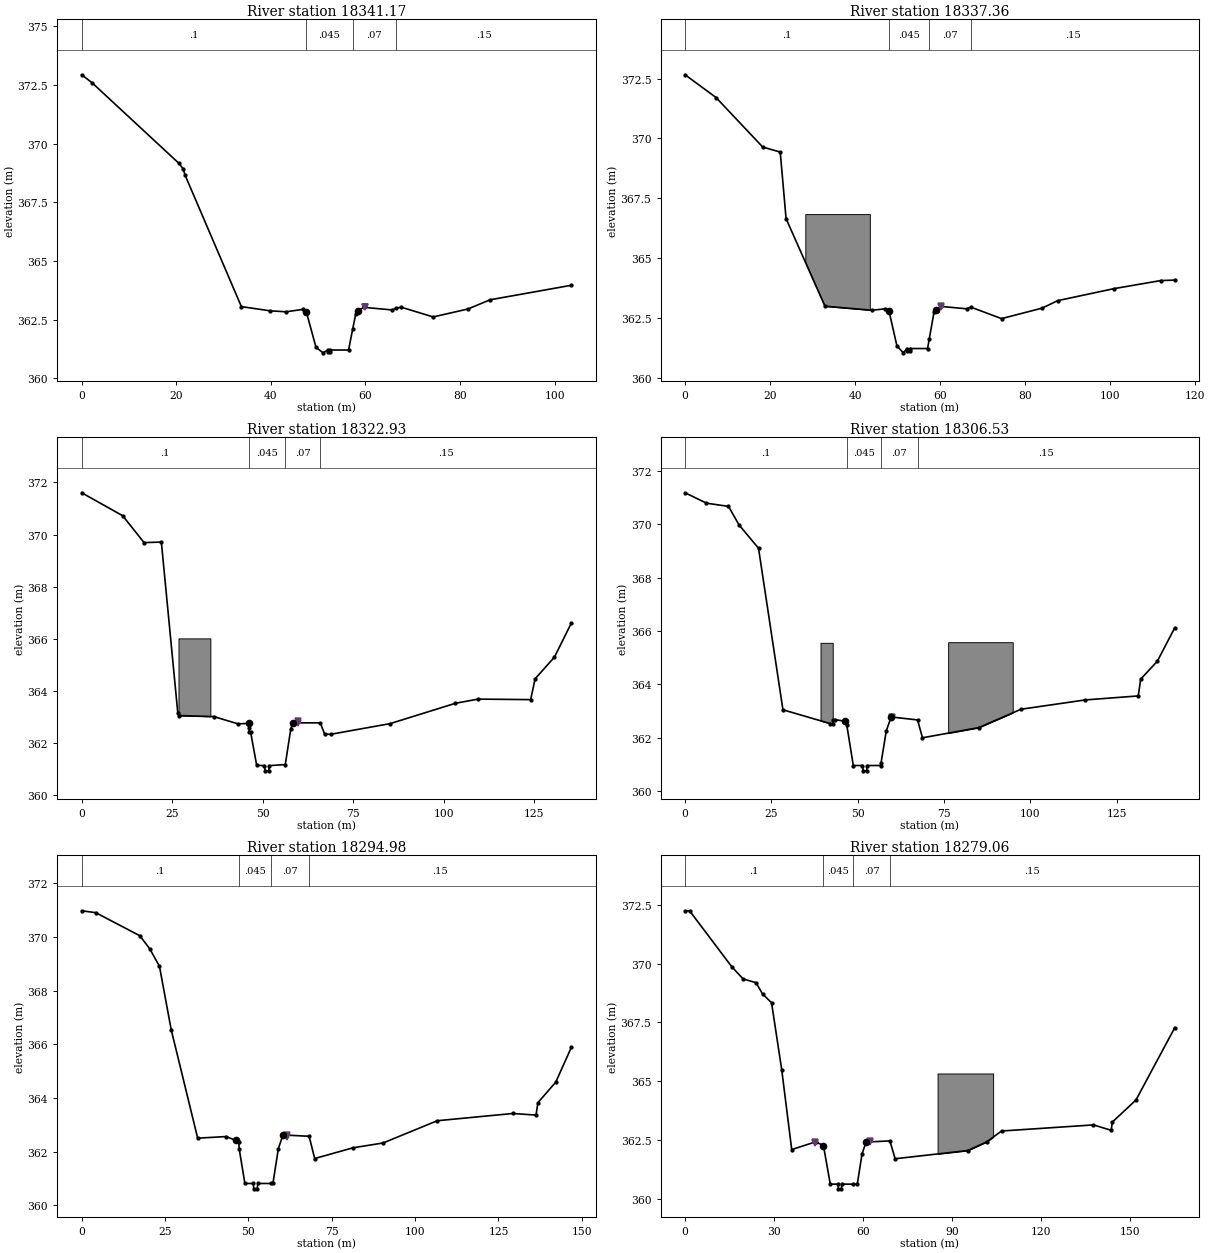
Type RM Length L Ch R = 1 ,18341.17,3.64,3.82,3.48
XS GIS Cut Line= 3
    -608984.7855   -1044901.5539    -609031.6963   -1044854.4518
    -609056.4353   -1044826.8159
#Sta/Elev= 28
       0  372.94    2.13  372.61   20.54  369.17   21.45  368.93   21.89  368.65
   33.77  363.06   39.86  362.88   43.25  362.84   46.71  362.94   47.49  362.85
   49.56  361.32   51.05  361.09   52.02  361.21   52.09  361.14   52.43  361.14
    52.5  361.21   56.44  361.21    57.3  362.09   57.94  362.73   58.53  362.88
   59.63  363.03   65.57  362.92   66.48  362.98   67.49  363.04   74.34  362.62
   81.72  362.96   86.35  363.35  103.57  363.97
#Mann= 4 ,-1 , 0
       0      .1       0   47.49    .045       0    57.3     .07       0
   66.48     .15       0
Levee=0,,,-1,59.84,363.03,,
Bank Sta=47.49,58.53
XS Rating Curve= 0 ,0
Exp/Cntr=0.3,0.1

Type RM Length L Ch R = 1 ,18337.36,14.84,14.42,14.55
XS GIS Cut Line= 4
     -608988.397   -1044905.6744    -609016.6957   -1044874.6581
-609031.05539999   -1044860.7368-609065.50409999   -1044820.1635
#Sta/Elev= 28
       0  372.66    7.27  371.71   18.26  369.64   22.38  369.43   23.75  366.65
   32.89  362.99   44.01  362.82   47.08  362.88   47.98  362.78   49.83  361.33
   51.34  361.04    52.2  361.22   52.32   361.1   52.89   361.1      53  361.22
   57.05  361.22   57.45  361.63   58.55  362.73   59.06  362.85   60.24  362.98
   66.23  362.88   67.23  362.95   74.45  362.47   84.01  362.91   87.64  363.22
  100.82  363.72  111.88  364.06  115.21  364.08
#Mann= 4 ,-1 , 0
       0      .1       0   47.98    .045       0   57.45     .07       0
   67.23     .15       0
Levee=0,,,-1,60.25,362.97,,
#Block Obstruct= 1 ,-1
   28.28   43.46366.8377
Bank Sta=47.98,59.06
XS Rating Curve= 0 ,0
Exp/Cntr=0.3,0.1

Type RM Length L Ch R = 1 ,18322.93,16.56,16.4,16.08
XS GIS Cut Line= 2
    -608999.2052   -1044914.5843-609092.44469999   -1044816.5633
#Sta/Elev= 30
       0   371.6   11.32  370.72   17.22  369.69      22  369.71   26.56  363.14
   26.79  363.06   36.52  363.02    43.2  362.74   46.09  362.76   46.17362.5667
   46.35  362.41   46.64  362.44   48.34  361.15   50.46  361.14   50.66  360.94
   51.66  360.94   51.86  361.14   56.24361.1803   57.76  362.55   58.39  362.78
   65.92  362.78   67.09  362.35   68.75  362.34    85.2  362.75  103.25  363.53
   109.5  363.69  124.02  363.67  125.26  364.47   130.6   365.3  135.28  366.61
#Mann= 4 ,-1 , 0
       0      .1       0   46.17    .045       0   56.24     .07       0
   65.92     .15       0
Levee=0,,,-1,59.87,362.84,,
#Block Obstruct= 1 ,-1
   26.73   35.54366.0181
Bank Sta=46.09,58.39
XS Rating Curve= 0 ,0
Exp/Cntr=0.3,0.1

Type RM Length L Ch R = 1 ,18306.53,11.47,11.55,11.69
XS GIS Cut Line= 3
-609011.42359999   -1044926.7722     -609089.892   -1044841.4859
-609102.89469999   -1044819.0525
#Sta/Elev= 30
       0  371.18    6.19  370.79   12.56  370.67   15.64  369.97   21.26   369.1
   28.33  363.04    42.1  362.52   42.75  362.52   42.97  362.64   43.53  362.67
   46.24  362.61   46.81  362.48   48.71  360.95   51.35  360.95   51.55  360.75
   52.55  360.75   52.75  360.95   56.63  360.95   56.76361.0543   58.26  362.25
   59.68  362.77   67.32  362.66   68.74  361.99   85.01  362.37   97.26  363.06
  115.89  363.41  131.24  363.56  131.94  364.19  136.75  364.86  141.82  366.12
#Mann= 4 ,-1 , 0
       0      .1       0   46.81    .045       0   56.76     .07       0
   67.32     .15       0
Levee=0,,,-1,59.94,362.74,,
#Block Obstruct= 2 ,-1
   39.21   42.75365.5524   76.18   94.88 365.575
Bank Sta=46.24,59.68
XS Rating Curve= 0 ,0
Exp/Cntr=0.3,0.1

Type RM Length L Ch R = 1 ,18294.98,16.32,15.92,15.19
XS GIS Cut Line= 4
    -609019.4125   -1044934.5905    -609077.4164   -1044872.4435
    -609103.2397   -1044839.8467    -609108.1081   -1044820.1617
#Sta/Elev= 30
       0  370.98    4.19  370.91   17.42  370.05   20.37  369.57   23.32  368.91
   26.83  366.55   34.78   362.5    43.3  362.56   46.18  362.42   47.13  362.35
   47.22  362.11   48.94  360.81   51.43  360.81   51.63  360.61   52.63  360.61
   52.83  360.81   56.87  360.81   57.35  360.81   58.98  362.11   60.37  362.62
   68.21  362.57   69.87  361.74   81.35  362.14   90.37  362.32  106.65  363.15
  129.28  363.42  136.27  363.36  136.81  363.82  142.18  364.59  146.87  365.89
#Mann= 4 ,-1 , 0
       0      .1       0   47.13    .045       0   56.87     .07       0
   68.21     .15       0
Levee=0,,,-1,61.52,362.56,,
Bank Sta=46.18,60.37
XS Rating Curve= 0 ,0
Exp/Cntr=0.3,0.1

Type RM Length L Ch R = 1 ,18279.06,5.31,5.32,5.33
XS GIS Cut Line= 5
-609032.27279999   -1044946.5812    -609059.4153   -1044915.6818
     -609083.818   -1044887.4375-609116.26419999   -1044848.5425
-609124.47399999   -1044813.5362
#Sta/Elev= 30
       0  372.24     1.5  372.25   15.72  369.87   19.55  369.35   23.91  369.19
   26.11  368.71   29.13  368.34   32.56  365.49   35.93  362.09   43.99  362.42
   46.63  362.26   48.93  360.62   51.46  360.62   51.66  360.42   52.66  360.42
   52.86  360.62   56.73  360.62   58.03  360.62   59.66  361.92   61.01  362.41
   69.03  362.46   70.79   361.7   95.28  362.05  101.69  362.42  106.65  362.88
  137.65  363.14  143.62  362.91     144  363.26  151.97   364.2  165.06  367.28
#Mann= 4 ,-1 , 0
       0      .1       0   46.63    .045       0   56.73     .07       0
   69.03     .15       0
Levee=-1,43.75,362.38,-1,62.46,362.46,,
#Block Obstruct= 1 ,-1
    85.1  103.82365.3277
Bank Sta=46.63,61.01
XS Rating Curve= 0 ,0
Exp/Cntr=0.3,0.1

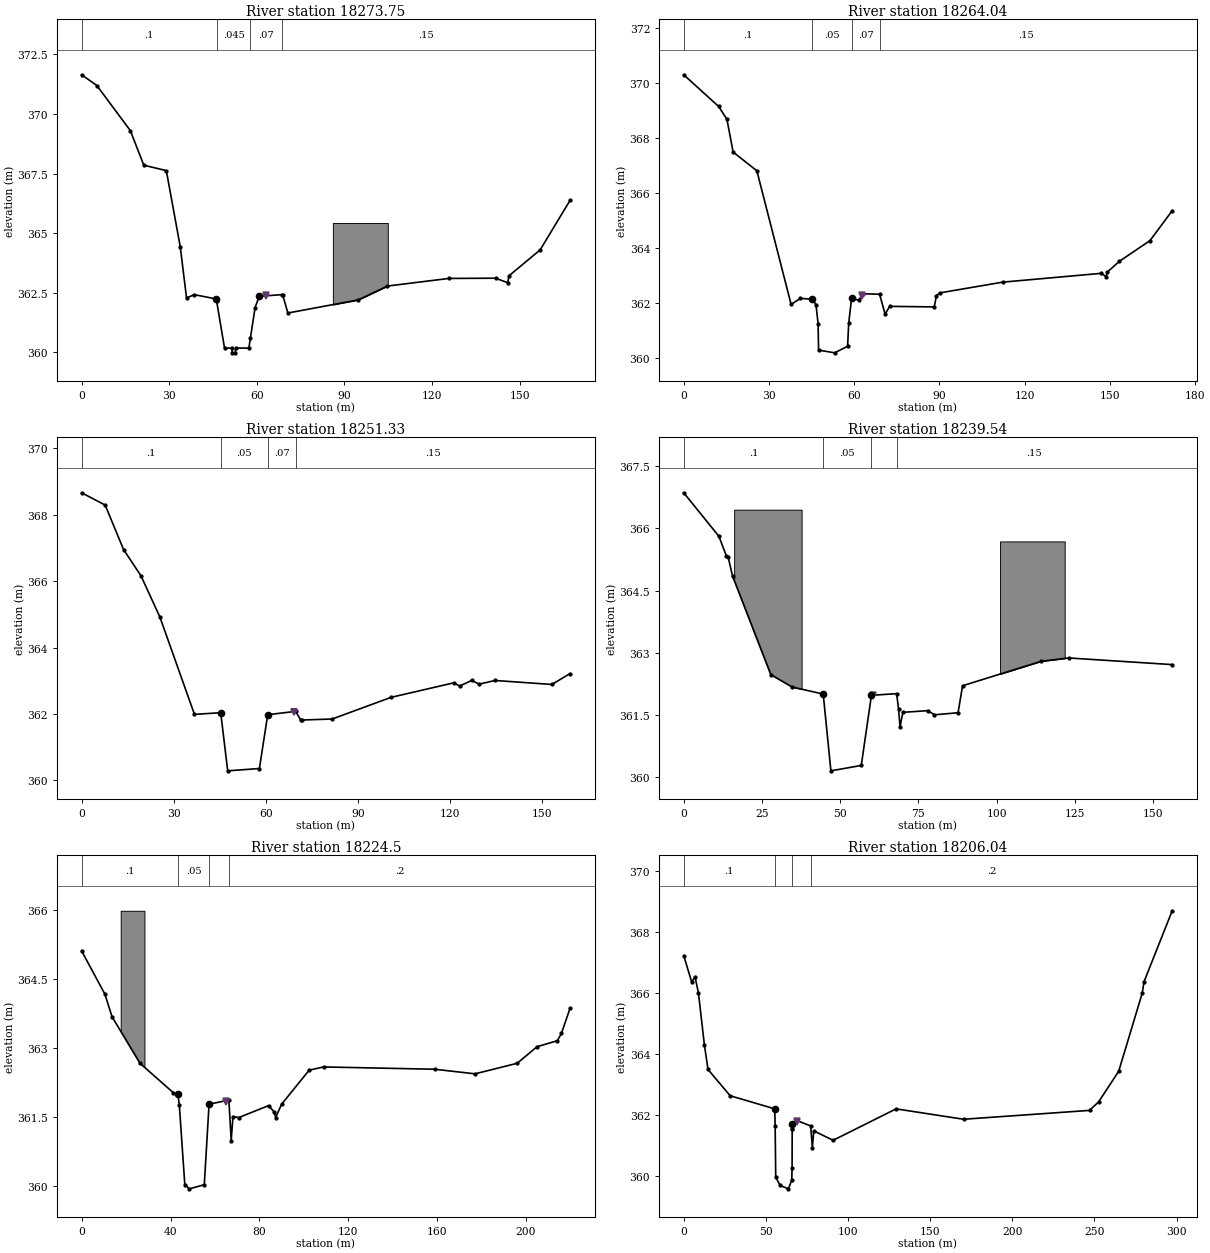
Type RM Length L Ch R = 1 ,18273.75,10.28,9.7,8.84
XS GIS Cut Line= 5
    -609036.4443   -1044949.8598-609064.65399999   -1044917.7456
-609089.05669999   -1044889.5013-609120.98169999   -1044852.9628
    -609132.1506   -1044815.9045
#Sta/Elev= 30
       0  371.64     5.2  371.19   16.67   369.3   21.28  367.85      29  367.62
   33.77  364.43   35.92  362.28   38.55  362.42   46.12  362.24   46.23  362.15
   48.93  360.18   51.39  360.18   51.59  359.98   52.59  359.98   52.79  360.18
   57.28  360.18   57.82 360.614    59.4  361.88   60.82  362.35    68.5  362.42
   68.85  362.41   70.63  361.65   94.71   362.2  104.69  362.78  125.75   363.1
  141.77  363.11  145.94  362.92  146.35  363.21  157.05   364.3   167.3  366.38
#Mann= 4 ,-1 , 0
       0      .1       0   46.23    .045       0   57.82     .07       0
    68.5     .15       0
Levee=0,,,-1,63.29,362.42,,
#Block Obstruct= 1 ,-1
   86.04  104.85365.4245
Bank Sta=46.12,60.82
XS Rating Curve= 0 ,0
Exp/Cntr=0.3,0.1

Type RM Length L Ch R = 1 ,18264.04,12.48,12.71,12.7
XS GIS Cut Line= 5
    -609043.6799   -1044956.0504    -609072.4114   -1044924.5346
-609084.51969999   -1044908.6165    -609125.8273   -1044857.4816
-609142.94559999   -1044817.4285
#Sta/Elev= 30
       0  370.31   12.28  369.16   15.21  368.69   17.39   367.5   25.74  366.82
    37.8  361.96   41.05  362.18   45.27  362.15   46.56  361.95   47.29  361.26
   47.47   360.3   53.13   360.2   57.68  360.44   58.07  361.27   59.09   362.2
   61.57  362.11   63.06  362.35   68.94  362.33   70.89  361.61    72.5  361.89
   88.18  361.87   88.96  362.28   90.18  362.38  112.24  362.77  146.92  363.09
  148.75  362.97  149.04  363.13  153.37  363.53  164.13  364.28  171.94  365.37
#Mann= 4 ,-1 , 0
       0      .1       0   45.27     .05       0   59.09     .07       0
   68.94     .15       0
Levee=0,,,-1,62.77,362.26,,
Bank Sta=45.27,59.09
XS Rating Curve= 0 ,0
Exp/Cntr=0.3,0.1

Type RM Length L Ch R = 1 ,18251.33,11.82,11.79,11.94
XS GIS Cut Line= 3
    -609055.0687   -1044965.2886    -609095.5801   -1044915.7116
    -609148.4968   -1044836.6673
#Sta/Elev= 22
       0  368.66    7.66  368.29   13.66  366.95   19.33  366.16   25.49  364.92
   36.75  361.99   45.31  362.04   47.58  360.29   57.91  360.36   60.62  361.98
   69.72  362.08   71.33  361.83   71.83  361.82   81.62  361.85  100.74   362.5
  121.28  362.94  123.12  362.84  127.06  363.01  129.52   362.9  134.68  363.01
   153.2  362.89  159.15  363.22
#Mann= 4 ,-1 , 0
       0      .1       0   45.31     .05       0   60.62     .07       0
   69.72     .15       0
Levee=0,,,-1,69.32,362.07,,
Bank Sta=45.31,60.62
XS Rating Curve= 0 ,0
Exp/Cntr=0.3,0.1

Type RM Length L Ch R = 1 ,18239.54,14.41,15.04,15.89
XS GIS Cut Line= 3
    -609064.9836   -1044971.8533    -609104.8405   -1044922.9878
-609156.10359999   -1044845.2663
#Sta/Elev= 22
       0  366.86   11.26  365.81   13.62  365.34   14.21  365.31   15.61  364.85
   27.82  362.48   34.65  362.18   44.59  362.01   47.05  360.16   56.76  360.29
   60.01  361.98   68.06  362.02   68.68  361.65   69.15  361.22   70.05  361.57
   78.08  361.61   80.15  361.51    87.7  361.56   89.14  362.21  114.25   362.8
  123.01  362.88  156.16  362.72
#Mann= 4 ,-1 , 0
       0      .1       0   44.59     .05       0   60.01     .07       0
   68.06     .15       0
Levee=0,,,-1,60.6,361.97,,
#Block Obstruct= 2 ,-1
   16.12   37.69366.4533  101.13  121.79365.6882
Bank Sta=44.59,60.01
XS Rating Curve= 0 ,0
Exp/Cntr=0.3,0.1

Type RM Length L Ch R = 1 ,18224.5 ,18.07,18.46,18.77
XS GIS Cut Line= 3
    -609075.6612   -1044979.0075    -609117.0775    -1044932.579
-609210.79199999   -1044805.8233
#Sta/Elev= 28
       0  365.11   10.49  364.17   13.68  363.68   26.24  362.67   41.24  362.03
   43.28     362   43.96  361.76   46.43  360.03   48.49  359.94    55.2  360.03
   57.34  361.78   66.26  361.87   67.31  360.99   68.09  361.51   70.76  361.49
   84.16  361.75   86.64  361.61    87.3  361.49      90  361.78   102.4  362.52
  108.88  362.59  158.83  362.54  177.06  362.44  196.05  362.67  204.95  363.03
  214.11  363.16  215.94  363.32  219.85  363.87
#Mann= 4 ,-1 , 0
       0      .1       0   43.28     .05       0   57.34     .07       0
   66.26      .2       0
Levee=0,,,-1,64.79,361.83,,
#Block Obstruct= 1 ,-1
   17.57   28.26365.9847
Bank Sta=43.28,57.34
XS Rating Curve= 0 ,0
Exp/Cntr=0.3,0.1

Type RM Length L Ch R = 1 ,18206.04,5.09,4.98,4.99
XS GIS Cut Line= 4
     -609080.951    -1044998.105    -609116.2027    -1044960.872
    -609129.9171   -1044946.3148-609272.49179999   -1044770.8857
#Sta/Elev= 30
       0  367.22    4.83  366.36    6.94  366.52    8.97  365.99   12.57   364.3
   14.78  363.49   28.27  362.63   55.41   362.2   55.65  361.65      56  359.96
    58.7  359.69   63.69  359.58   65.74  359.86   65.96  360.26   66.01  361.53
   66.11  361.55   66.12   361.7   68.84  361.82   77.27  361.64    78.3  360.92
   79.13  361.48   90.93  361.17  129.25   362.2  170.35  361.86     247  362.15
  252.55  362.43  264.74  363.43  279.08  365.99   280.2  366.37  297.33  368.69
#Mann= 4 ,-1 , 0
       0      .1       0   55.41     .05       0   66.12     .07       0
   77.27      .2       0
Levee=0,,,-1,69.11,361.76,,
Bank Sta=55.41,66.12
XS Rating Curve= 0 ,0
Exp/Cntr=0.5,0.3

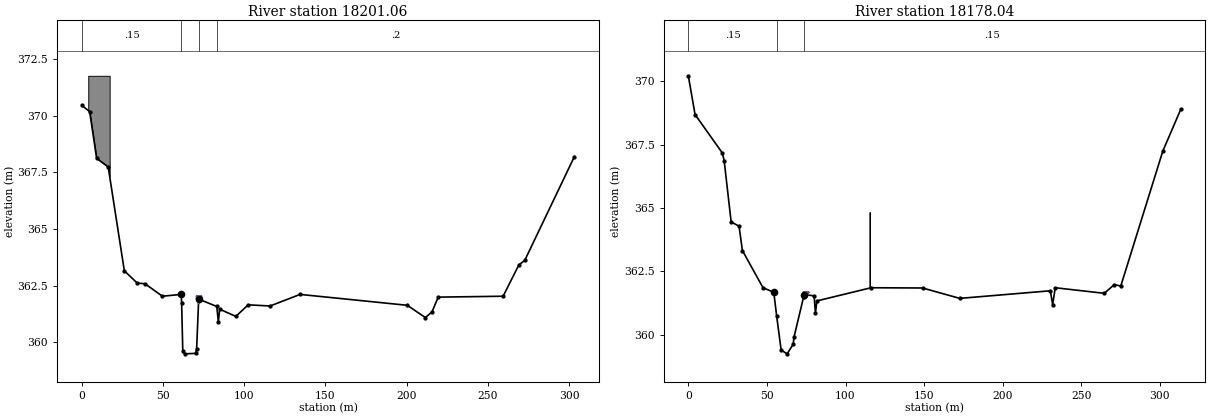
Type RM Length L Ch R = 1 ,18201.06,23.86,23.02,22.09
XS GIS Cut Line= 4
     -609081.967   -1045006.5717-609120.09479999    -1044964.001
    -609133.8092   -1044949.4436    -609276.3839   -1044774.0146
#Sta/Elev= 30
       0  370.45     4.8  370.18    9.09  368.12   16.22  367.74   26.16  363.16
    34.1  362.62   38.88  362.59   49.59  362.04   61.21  362.12   61.43  361.72
   62.15  359.61   63.21   359.5   70.02  359.52   70.68  359.73   71.92  361.91
   83.07  361.59   84.04  360.91   84.84  361.47   94.82  361.15  102.39  361.66
  115.93  361.61  134.35  362.12  200.36  361.64   211.5   361.1  215.58  361.35
  219.39     362  259.37  362.04  269.05  363.42  272.69  363.62  303.21  368.19
#Mann= 4 ,-1 , 0
       0     .15       0   61.21     .05       0   71.92     .07       0
   83.07      .2       0
Levee=0,,,-1,72.38,361.81,,
#Block Obstruct= 1 ,-1
    3.93   17.13371.7588
Bank Sta=61.21,71.92
XS Rating Curve= 0 ,0
Exp/Cntr=0.5,0.3

Type RM Length L Ch R = 1 ,18178.04,32.9,33.23,33.2
XS GIS Cut Line= 4
    -609103.6508   -1045021.0811-609138.55079999   -1044978.8772
    -609151.1605   -1044963.3531    -609291.7859   -1044770.6855
#Sta/Elev= 30
       0  370.22    4.28  368.69   21.67  367.17   22.82  366.86   27.24  364.45
   32.28  364.28    34.4  363.32   47.53  361.85   54.36  361.67   56.22360.7247
   59.04  359.39   62.85  359.24   66.74  359.62   67.19  359.89   73.29 361.474
   73.82  361.58   80.03  361.53   80.86  360.85   81.81  361.33  116.27  361.85
  148.98  361.84   172.7  361.43   230.3  361.73  231.77  361.18  233.41  361.85
   264.6  361.63  270.94  361.97  275.13  361.92  301.82  367.24  313.29   368.9
#Mann= 3 ,-1 , 0
       0     .15       0   56.22     .05       0   73.29     .15       0
Levee=0,,,-1,74.58,361.57,,
#Block Obstruct= 1 ,-1
  115.17  115.55 364.834
Bank Sta=54.36,73.82
XS Rating Curve= 0 ,0
Exp/Cntr=0.3,0.1

--- PPO_Kvasiny_efektiv.g12 (geometry) ---

Geom Title=N-Q50
Program Version=5.03

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
River Reach=Bela            ,Bela_reach