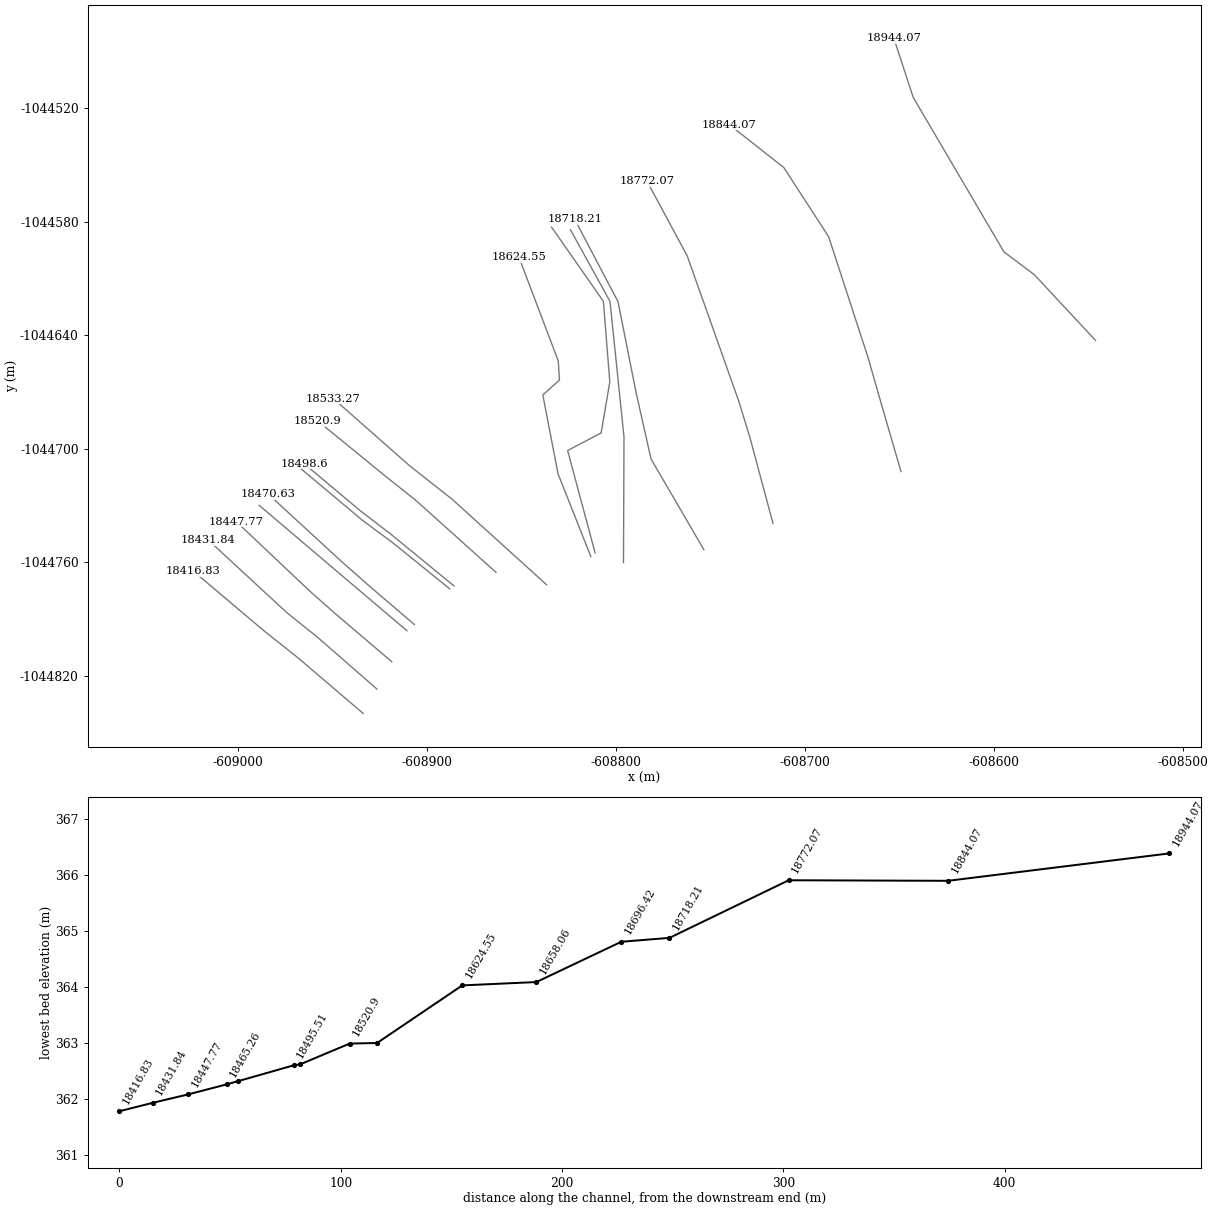
HEC-RAS study PPO_Kvasiny_efektiv.prj: PPO_Kvasiny_efektivita

--- PPO_Kvasiny_efektiv.g12 (geometry) --- (continued)

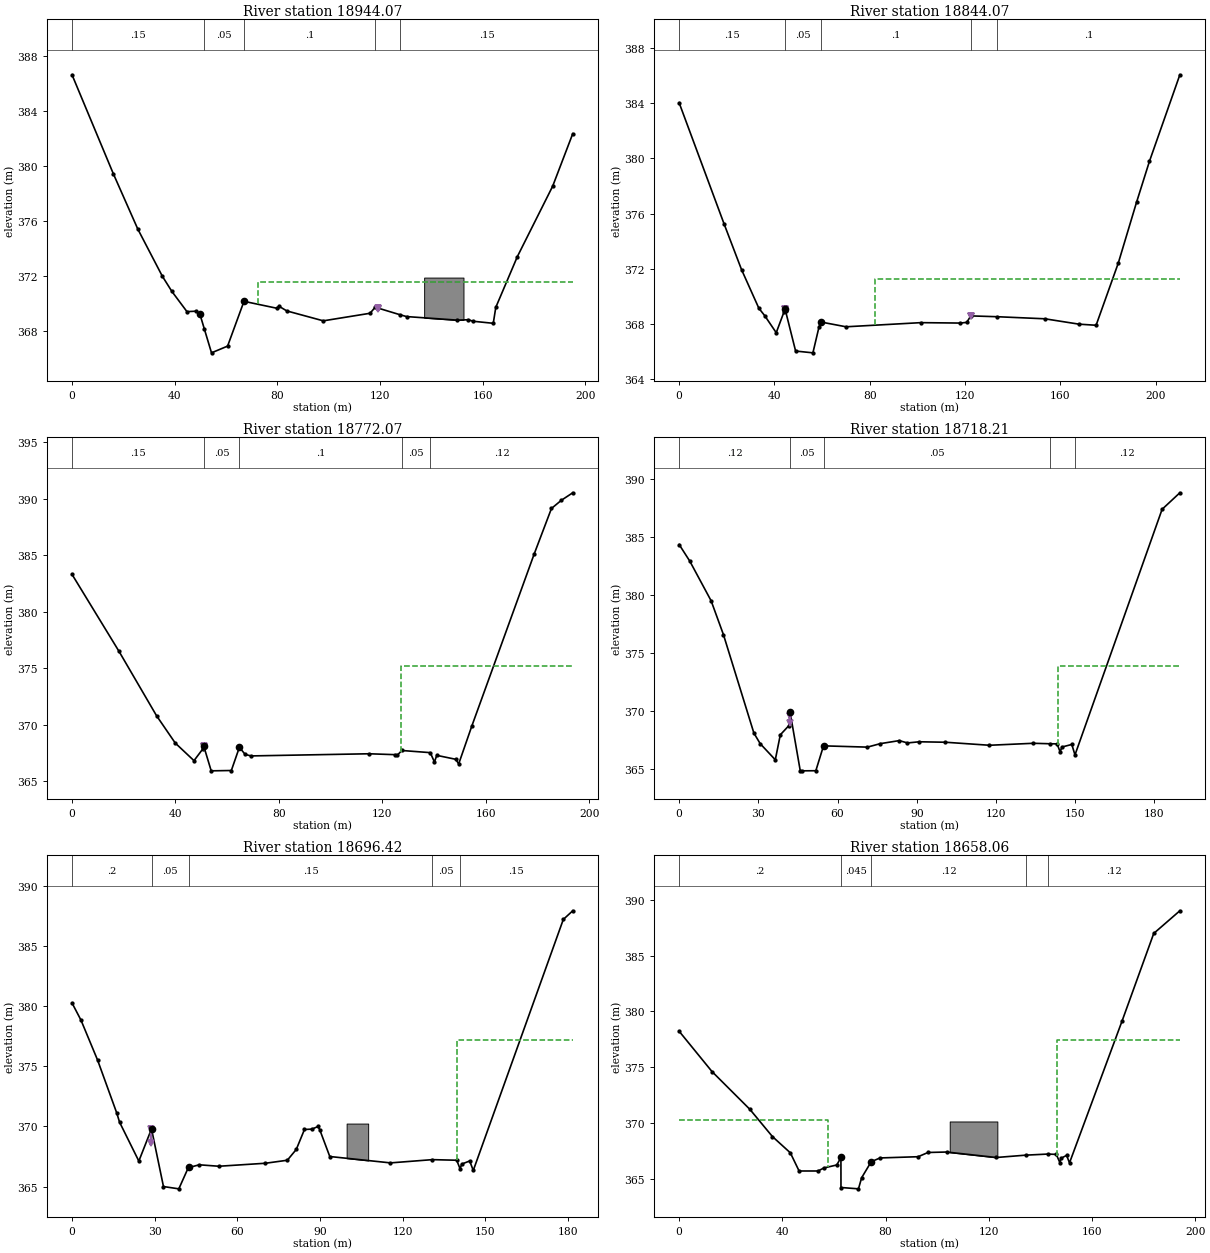
Type RM Length L Ch R = 1 ,18944.07,107.06,100,81.52
XS GIS Cut Line= 5
    -608546.4782   -1044642.7763-608578.86259999   -1044608.0005
     -608594.864   -1044596.0024    -608642.9144   -1044514.1948
    -608653.0656   -1044483.0645
#Sta/Elev= 29
       0  386.63   16.09  379.43   25.66  375.39   35.22  371.96   38.92  370.86
   44.79  369.39   48.23  369.42    49.8  369.23   51.56368.1339   54.36  366.39
   60.63  366.88   67.02  370.14   67.03370.1393   79.71  369.64   80.76  369.77
   83.72  369.44   97.93  368.72  116.15  369.27  118.16  369.71   127.9369.1595
  130.38  369.03  150.14  368.77  154.47   368.8  156.24  368.69  164.17  368.54
  165.15   369.7  173.57   373.4  187.32  378.52  195.14  382.34
#Mann= 5 ,-1 , 0
       0     .15       0   51.56     .05       0   67.03      .1       0
  118.16     .05       0   127.9     .15       0
Levee=0,,,-1,119.11,369.55,,
#XS Ineff= 2 , 0
                           72.51          371.52
Permanent Ineff=
       F       F
#Block Obstruct= 1 ,-1
  137.23  152.56371.8682
Bank Sta=49.8,67.02
XS Rating Curve= 0 ,0
Exp/Cntr=0.3,0.1

Type RM Length L Ch R = 1 ,18844.07,72.16,72,73.34
XS GIS Cut Line= 6
-608649.34349999   -1044712.1427    -608661.1943   -1044671.2681
    -608666.6842   -1044652.0363-608687.57959999     -1044587.96
    -608711.2657   -1044551.4157    -608740.0273   -1044528.7448
#Sta/Elev= 28
       0  384.04   18.89  375.24   26.18  371.94   33.47  369.13    35.9   368.6
   40.75  367.36   44.03  368.88   44.31  369.11   44.35  369.09   44.67  368.93
   48.88  366.03   56.14   365.9   58.65  367.74   59.34  368.14   59.46368.1367
   70.03  367.79  101.43  368.09     118  368.06  120.69  368.11  122.41  368.58
  133.48  368.52  153.46  368.37  167.81  367.98  174.98   367.9  184.29  372.41
  191.95  376.82  197.36  379.79  210.13  386.07
#Mann= 5 ,-1 , 0
       0     .15       0   44.35     .05       0   59.46      .1       0
  122.41     .05       0  133.48      .1       0
Levee=-1,44.3,369.1,-1,122.55,368.54,,
#XS Ineff= 2 , 0
                           82.13          371.22
Permanent Ineff=
       F       F
Bank Sta=44.31,59.34
XS Rating Curve= 0 ,0
Exp/Cntr=0.3,0.1

Type RM Length L Ch R = 1 ,18772.07,49.5,53.87,46.34
XS GIS Cut Line= 5
-608717.01799999   -1044739.5508    -608729.3973    -1044693.413
    -608735.3242   -1044674.3114    -608762.3599   -1044598.1112
    -608783.6774   -1044558.5216
#Sta/Elev= 28
       0  383.29   18.17  376.48   32.67  370.79   39.91  368.37   47.16  366.81
   50.67  367.88   50.91  368.11   50.99368.0506   53.81  365.91    61.6  365.94
    64.7367.9844   64.71  367.99   66.95  367.36   69.23  367.23  114.85  367.42
     125  367.34  125.72  367.28   127.5  367.71  138.51  367.52  140.12  366.69
  141.02  367.28  148.38  366.93  149.49  366.52  154.63  369.91  178.71  385.11
  185.36  389.12  189.15  389.84  193.59  390.51
#Mann= 5 ,-1 , 0
       0     .15       0   50.99     .05       0    64.7      .1       0
   127.5     .05       0  138.51     .12       0
Levee=-1,50.88,368,0,,,,
#XS Ineff= 2 , 0
                          127.02          375.15
Permanent Ineff=
       F       F
Bank Sta=50.91,64.71
XS Rating Curve= 0 ,0
Exp/Cntr=0.3,0.1

Type RM Length L Ch R = 1 ,18718.21,29.06,21.79,6.52
XS GIS Cut Line= 5
-608753.54699999   -1044753.4637     -608781.487   -1044705.5211
    -608789.4245   -1044670.2786    -608798.9496    -1044622.336
-608821.80959999   -1044578.8384
#Sta/Elev= 30
       0  384.35    4.01  382.93   12.11  379.51   16.79  376.59   28.31  368.13
   30.69  367.22   36.42  365.83   38.32  367.98   41.56  368.77   42.02  369.93
   45.86   364.9   46.37  364.88   51.77  364.89   54.68  367.03   71.29  366.92
    76.2  367.22   83.37  367.48   86.48  367.28   90.94  367.38  100.86  367.34
  117.53  367.08  134.11  367.25  140.49  367.21  143.13   367.2  144.27  366.52
  144.99  366.93  148.71  367.15  149.91  366.25  182.91  387.38  189.63   388.8
#Mann= 5 ,-1 , 0
       0     .12       0   42.02     .05       0   54.68     .05       0
  140.49     .05       0  149.91     .12       0
Levee=-1,41.88,369,0,,,,
#XS Ineff= 2 , 0
                           143.3          373.87
Permanent Ineff=
       F       F
Bank Sta=42.02,54.68
XS Rating Curve= 0 ,0
Exp/Cntr=0.3,0.1

Type RM Length L Ch R = 1 ,18696.42,50.22,38.35,4.09
XS GIS Cut Line= 4
-608796.05849999    -1044760.252    -608795.7939   -1044693.8414
    -608803.2023   -1044622.1392    -608824.1044   -1044584.3037
#Sta/Elev= 30
       0  380.28    3.25  378.85    9.27  375.53   16.25  371.11   17.25  370.36
   24.25  367.12   28.85   369.8   33.19     365   38.76  364.81   42.24  366.59
    42.5  366.59   46.19  366.81   53.31  366.69   70.21  366.94   78.14  367.19
   81.39  368.09   84.36  369.75   87.08  369.78   89.29     370   89.92  369.72
   93.55   367.5  115.58  366.97  130.78  367.24  139.61  367.19  140.83  366.48
  141.43  366.87  144.32  367.13  145.62  366.34   178.3  387.23  181.72  387.95
#Mann= 5 ,-1 , 0
       0      .2       0   28.85     .05       0    42.5     .15       0
  130.78     .05       0  140.83     .15       0
Levee=-1,28.8,368.61,0,,,,
#XS Ineff= 2 , 0
                          139.61          377.16
Permanent Ineff=
       F       F
#Block Obstruct= 1 ,-1
   99.66  107.48370.2419
Bank Sta=28.85,42.5
XS Rating Curve= 0 ,0
Exp/Cntr=0.3,0.1

Type RM Length L Ch R = 1 ,18658.06,22,33.51,26.87
XS GIS Cut Line= 6
-608811.08549999    -1044755.116     -608825.589   -1044701.0257
    -608807.8792   -1044691.7325-608803.30299999   -1044664.7705
    -608806.6867   -1044622.1356-608834.09479999   -1044582.8844
#Sta/Elev= 30
       0  378.22   12.72  374.61   27.41  371.22   36.15  368.78    43.1  367.32
    46.5  365.69   53.84  365.69   56.09  365.96   61.11  366.23   62.71   366.9
   62.73  364.21   69.51  364.09   70.75  365.09   74.45  366.52   74.46366.5206
   77.86  366.86   92.64  366.97   96.45  367.35  103.66  367.39  122.92   366.9
  134.34  367.11   142.8367.2064  146.19  367.18  147.55  366.45  148.03  366.83
  150.17  367.09  151.31  366.42  171.67  379.13  183.96  386.99  194.08  389.02
#Mann= 5 ,-1 , 0
       0      .2       0   62.71    .045       0   74.46     .12       0
  134.34     .05       0   142.8     .12       0
#XS Ineff= 2 , 0
           57.59  370.29  146.42          377.41
Permanent Ineff=
       F       F
#Block Obstruct= 1 ,-1
  104.88  123.34370.1295
Bank Sta=62.71,74.45
XS Rating Curve= 0 ,0
Exp/Cntr=0.3,0.1

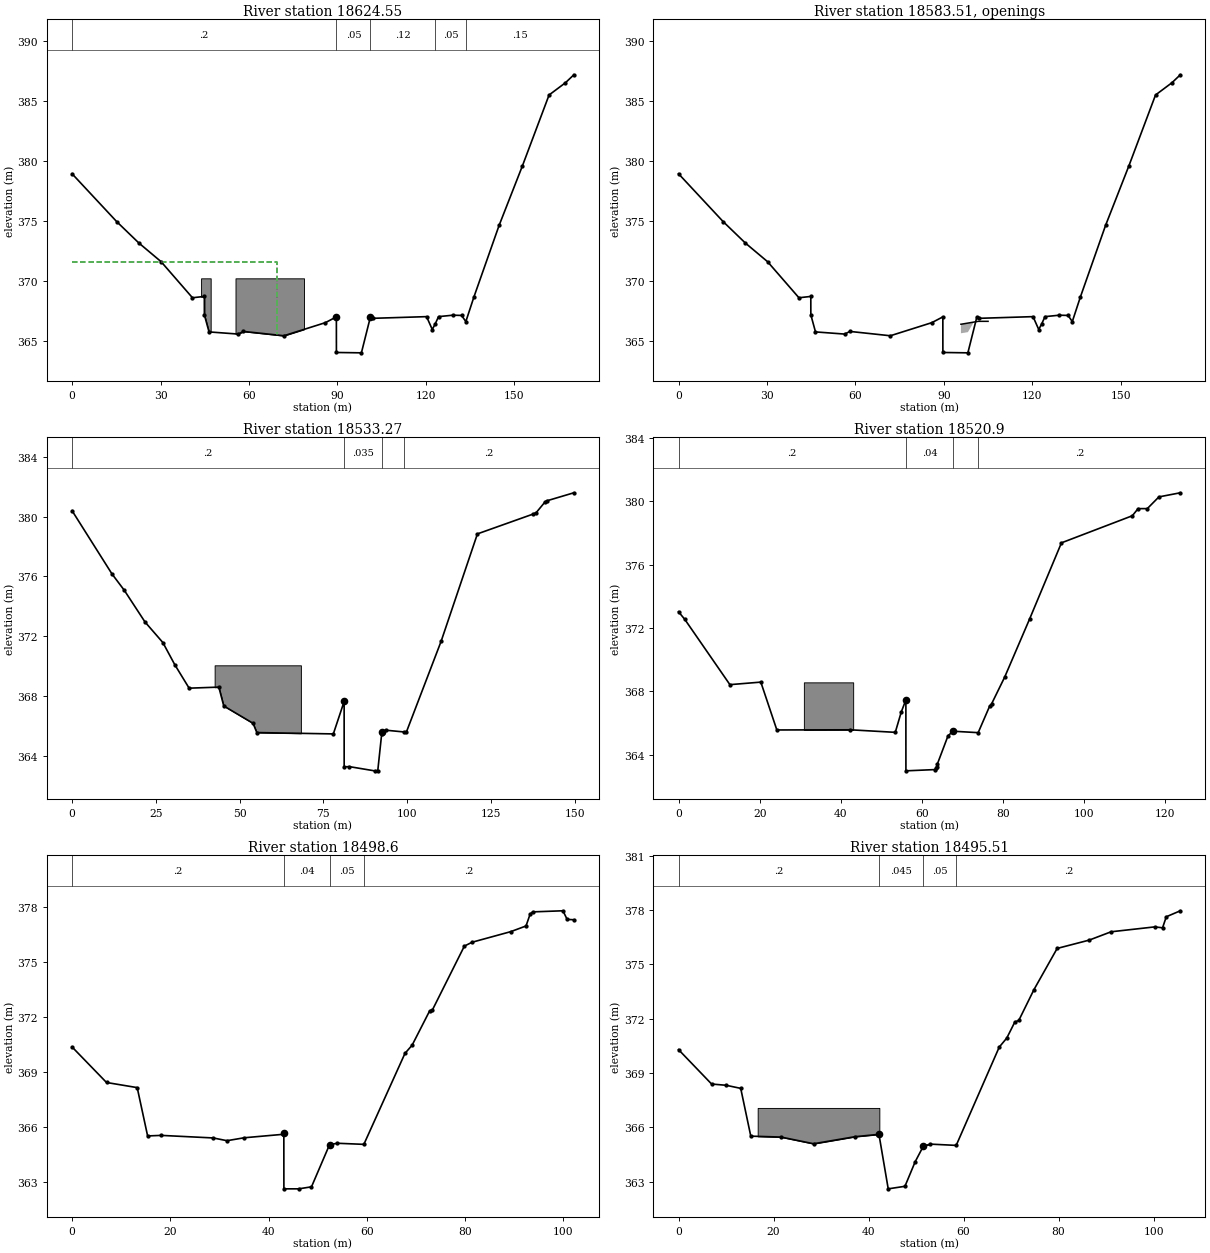
Type RM Length L Ch R = 1 ,18624.55,27.54,38.49,47.2
XS GIS Cut Line= 6
    -608813.3292   -1044757.0751-608830.65819999   -1044713.3605
     -608838.708   -1044671.6675    -608829.9133   -1044663.7088
    -608830.5483   -1044653.6758    -608851.3869   -1044598.6741
#Sta/Elev= 30
       0  378.92   15.14  374.94   22.67  373.16    30.2  371.61   40.84  368.61
   44.87  368.72   44.88  367.19   46.46  365.77   56.35  365.59   58.15  365.81
   71.85  365.45   85.93  366.54   89.66  367.02   89.67  364.06   98.15  364.03
   101.2  367.01  101.96   366.9  120.26  367.04  122.19  365.97  123.18  366.43
  124.31  367.04  129.18  367.16  132.12  367.14  133.58  366.63  136.31  368.67
  144.85  374.62  152.76  379.57  161.81  385.47  167.38  386.49  170.22  387.15
#Mann= 5 ,-1 , 0
       0      .2       0   89.66     .05       0   101.2     .12       0
  123.18     .05       0  133.58     .15       0
#XS Ineff= 2 , 0
           69.42   371.6
Permanent Ineff=
       F       F
#Block Obstruct= 2 ,-1
   43.76   47.02 370.226   55.44   78.67 370.226
Bank Sta=89.66,101.2
XS Rating Curve= 0 ,0
Exp/Cntr=0.3,0.1

Type RM Length L Ch R = 4 ,18583.51,,,
BEGIN DESCRIPTION:
18779.9  PF 244 SILNIÈNÍ ŽLB MOSTEK F.PORKET
END DESCRIPTION:
Bridge Culvert--1,0,-1,-1, 0
Deck Dist Width WeirC Skew NumUp NumDn MinLoCord MaxHiCord MaxSubmerge Is_Ogee
0.2,6.6,1.4,0, 4, 4, , , 0.98, 0, 0,0,,
    95.8   95.89  101.67     105
  366.41  366.41  366.65  366.65
  365.66  365.66  365.89  365.89
      95   95.89  101.67     105
  366.41  366.41  366.65  366.65
  365.66  365.66  365.89  365.89
BR Coef=-1 , 0 , 0 ,, 0 ,,,0.8,-1,,0,
WSPro=,,,, 1 ,,,, 0 ,,,, 0 ,,,,-1 ,-1 ,-1 , 0 , 0 , 0 , 0 , 0
BC Mult= 1 ,0,95.31,0,94.9
BC Mult= 3 ,95.31,101.21,94.9,102.36
BC Mult= 1 ,101.21,160.29,102.36,160.29
BC Design=,, 0 ,, 0 ,,,,,,
BC Use User HTab Curves=0
BC User HTab FreeFlow(D)= 0

Type RM Length L Ch R = 1 ,18533.27,12.87,12.37,12.43
XS GIS Cut Line= 4
    -608836.7278   -1044771.9928-608886.99879999   -1044726.4844
    -608909.2238   -1044709.0218    -608949.4406   -1044673.5676
#Sta/Elev= 29
       0   380.4   11.91  376.17   15.57  375.08   21.75  372.96   27.09  371.58
   30.64   370.1   34.92  368.53   43.78   368.6   45.25  367.34   53.98  366.18
   55.12  365.56   77.94  365.47   81.16  367.64   81.17  363.27   82.75  363.28
   90.22     363    91.2  363.02   92.37  365.49   92.53   365.6   93.52  365.72
   99.07   365.6   99.74   365.6   110.1  371.67  120.92  378.85  137.46  380.17
  138.48  380.28  141.03  380.97  141.59  381.06  149.69   381.6
#Mann= 4 ,-1 , 0
       0      .2       0   81.16    .035       0   92.53     .05       0
   99.07      .2       0
#Block Obstruct= 1 ,-1
   42.53   68.26370.0591
Bank Sta=81.16,92.53
XS Rating Curve= 0 ,0
Exp/Cntr=0.3,0.1

Type RM Length L Ch R = 1 ,18520.9 ,21.89,22.29,22.52
XS GIS Cut Line= 4
    -608863.4842   -1044765.4406-608906.08109999   -1044727.1808
-608921.42689999     -1044715.01    -608957.6926   -1044685.3842
#Sta/Elev= 27
       0  373.03    1.54  372.55   12.66  368.43   20.28  368.59   24.23  365.57
   42.35  365.58   53.42  365.42   54.89   366.7   56.03  367.47   56.04  362.99
   63.28  363.07   63.48   363.2   63.73  363.25   63.82  363.44   66.43  365.21
   67.69  365.49   73.85   365.4   76.67  367.07   77.16  367.22   80.37   368.9
    86.5  372.56   94.37  377.38  111.84  379.09  113.26  379.54  115.53  379.54
  118.39  380.28  123.67  380.54
#Mann= 4 ,-1 , 0
       0      .2       0   56.03     .04       0   67.69     .05       0
   73.85      .2       0
#Block Obstruct= 1 ,-1
   30.89   43.04368.5746
Bank Sta=56.03,67.69
XS Rating Curve= 0 ,0
Exp/Cntr=0.3,0.1

Type RM Length L Ch R = 1 ,18498.6 ,2.83,3.09,3.31
XS GIS Cut Line= 4
    -608885.6669   -1044772.6373    -608919.2351   -1044745.1325
    -608935.1101   -1044732.9616    -608964.8046   -1044708.0749
#Sta/Elev= 29
       0  370.37    7.01  368.43   13.26  368.15   15.38  365.51   18.15  365.54
   28.73   365.4   31.54  365.25   35.05  365.41   43.04   365.6   43.11  365.66
   43.12  362.62   46.14  362.62   48.74  362.73   52.41  365.03   53.99  365.11
    59.4  365.05   67.77  370.02   69.23  370.47   72.79  372.34   73.35  372.39
   79.86  375.88   81.41  376.09    89.3  376.67   92.41  376.98   93.25  377.63
   93.77  377.75   99.93  377.81  100.78  377.34  102.15  377.32
#Mann= 4 ,-1 , 0
       0      .2       0   43.11     .04       0   52.41     .05       0
    59.4      .2       0
#XS Ineff= 2 , 0
Permanent Ineff=
       F       F
Bank Sta=43.11,52.41
XS Rating Curve= 0 ,0
Exp/Cntr=0.3,0.1

Type RM Length L Ch R = 1 ,18495.51,25.6,24.88,23.57
XS GIS Cut Line= 4
    -608887.9529   -1044774.1613    -608917.6792   -1044750.0879
    -608934.0835    -1044737.917    -608970.0669   -1044707.7544
#Sta/Elev= 27
       0  370.29    6.96  368.39   10.03  368.32   13.09  368.15   15.21  365.51
   21.57  365.46   28.43  365.09   37.14  365.48   42.19  365.61   44.14   362.6
   47.66  362.74   49.82   364.1   51.54  364.96   53.01  365.07   58.45     365
   67.51  370.43    69.1  370.93    70.8  371.82   71.62   371.9   74.81   373.6
    79.7  375.88   86.45  376.34   91.06   376.8  100.25  377.07  101.89  377.02
  102.68  377.63  105.63  377.96
#Mann= 4 ,-1 , 0
       0      .2       0   42.19    .045       0   51.54     .05       0
   58.45      .2       0
#Block Obstruct= 2 ,-1
   16.66   42.27367.0693   52.01    52.5 365.041
Bank Sta=42.19,51.54
XS Rating Curve= 0 ,0
Exp/Cntr=0.3,0.1

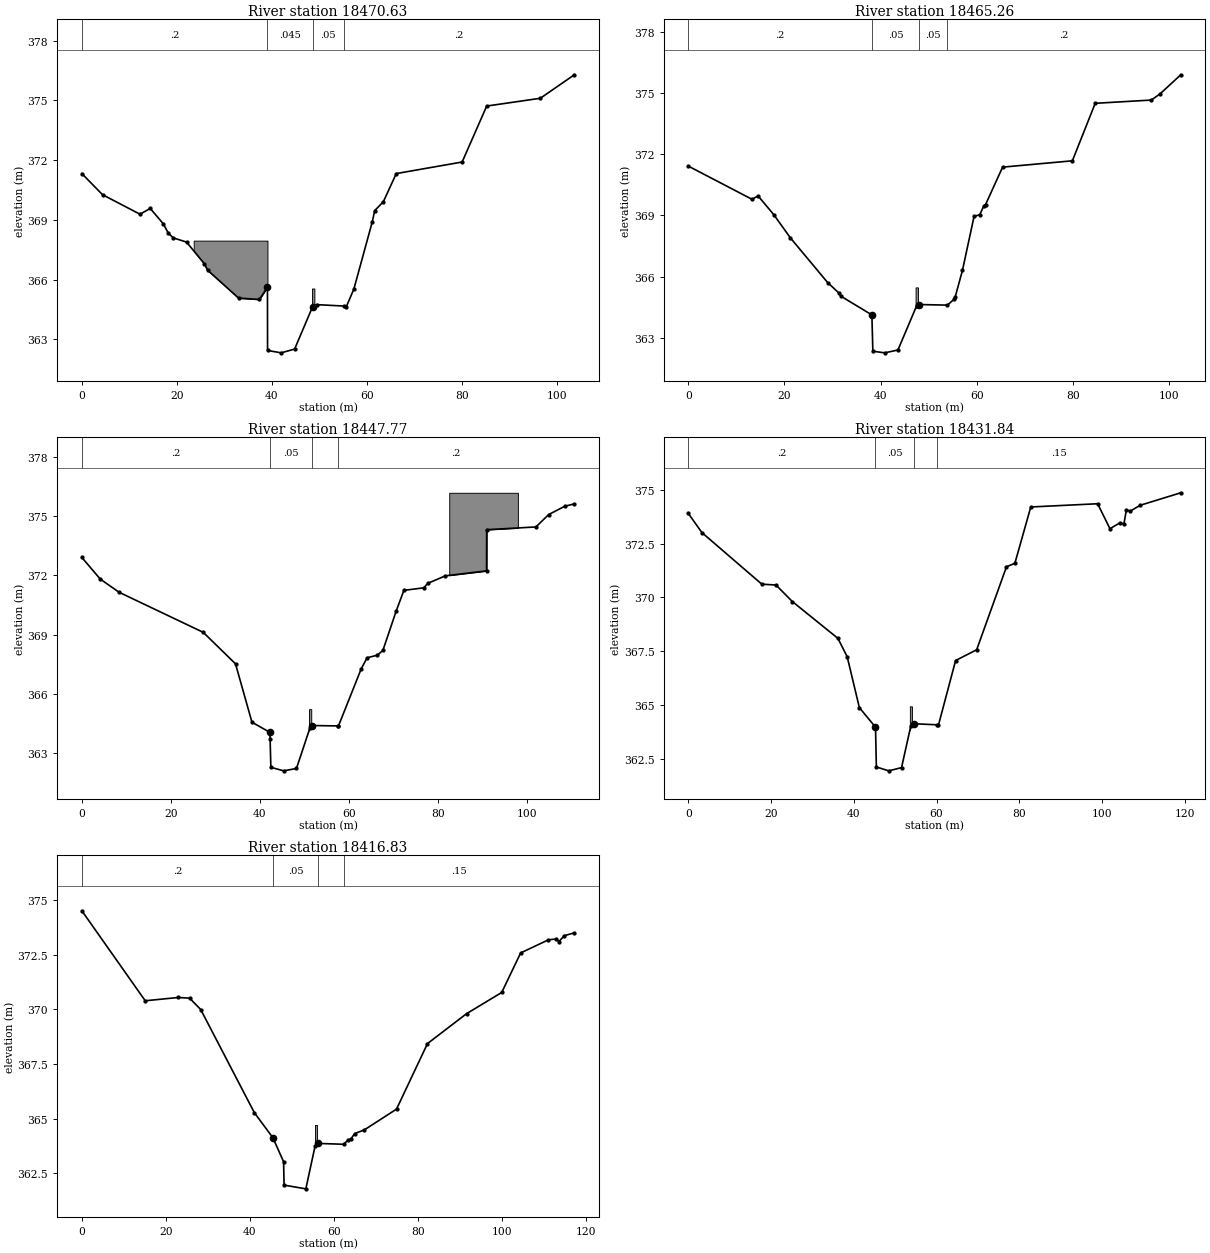
Type RM Length L Ch R = 1 ,18470.63,5.16,5.37,5.75
XS GIS Cut Line= 4
-608906.65179999   -1044793.0242    -608930.3372   -1044772.7807
-608945.32779999   -1044759.5411    -608983.9917   -1044723.9844
#Sta/Elev= 30
       0  371.32    4.35  370.26   12.24  369.28    14.4  369.57   17.14   368.8
   18.23  368.32   19.27  368.09   22.05  367.88   25.79  366.79   26.47  366.47
   32.99  365.07   37.38     365      39365.5917   39.08  365.61    39.1  362.44
   41.97  362.32    44.8  362.51   48.59  364.64   49.46  364.74   55.09  364.67
   55.62   364.6   57.27  365.52   61.13  368.88   61.66  369.46   63.49  369.91
    66.2  371.32   80.07   371.9   85.24  374.71   96.53   375.1  103.69  376.28
#Mann= 4 ,-1 , 0
       0      .2       0      39    .045       0   48.59     .05       0
   55.09      .2       0
#XS Ineff= 2 , 0
Permanent Ineff=
       F       F
#Block Obstruct= 2 ,-1
   23.55   39.08 367.954   48.46   48.96  365.55
Bank Sta=39.08,48.59
XS Rating Curve= 0 ,0
Exp/Cntr=0.3,0.1

Type RM Length L Ch R = 1 ,18465.26,17.65,17.49,17.14
XS GIS Cut Line= 2
    -608910.5632   -1044796.3117    -608988.7089   -1044730.0063
#Sta/Elev= 28
       0  371.42   13.27  369.79   14.51  369.96   17.78  369.04   21.24   367.9
   29.02   365.7   31.41  365.18   31.74  365.04    38.2  364.12    38.4  362.34
   40.87  362.26   43.62   362.4    47.5  364.56   48.04  364.63   53.93   364.6
    55.3  364.89   55.55  365.01   57.04   366.3   59.46  368.95   60.65  369.04
   61.48  369.46   61.85  369.53    65.4  371.37   79.92  371.68   84.67   374.5
   96.34  374.66   98.15  374.96  102.48   375.9
#Mann= 4 ,-1 , 0
       0      .2       0    38.2     .05       0   48.04     .05       0
   53.93      .2       0
#Block Obstruct= 1 ,-1
   47.29   47.79  365.47
Bank Sta=38.2,48.04
XS Rating Curve= 0 ,0
Exp/Cntr=0.3,0.1

Type RM Length L Ch R = 1 ,18447.77,15.66,15.93,16.64
XS GIS Cut Line= 4
-608918.60229999   -1044812.6923-608948.38219999   -1044787.3387
    -608962.1406   -1044775.1678    -609000.7698   -1044738.6552
#Sta/Elev= 30
       0  372.91    4.15  371.81     8.4  371.14   27.27  369.11   34.52  367.51
   38.21  364.55   42.26  364.03   42.29  363.69   42.46  362.26   45.32  362.08
   48.21   362.2   51.24  364.26   51.65  364.38   57.48  364.36   57.63  364.35
   62.76  367.26   64.08  367.82   66.39  367.95   67.64   368.2   70.61  370.19
   72.34  371.24   76.82  371.37   77.73   371.6   81.68  371.98   90.92  372.23
   90.94  374.32     102  374.46  104.88  375.09  108.48  375.51  110.63  375.63
#Mann= 4 ,-1 , 0
       0      .2       0   42.26     .05       0   51.65     .05       0
   57.48      .2       0
#XS Ineff= 2 , 0
Permanent Ineff=
       F       F
#Block Obstruct= 2 ,-1
   82.53   97.95 376.194   51.03   51.53  365.21
Bank Sta=42.26,51.65
XS Rating Curve= 0 ,0
Exp/Cntr=0.3,0.1

Type RM Length L Ch R = 1 ,18431.84,14.94,15.01,15.06
XS GIS Cut Line= 4
-608926.42619999   -1044827.1558    -608957.9395   -1044799.6768
-608973.81459999   -1044786.9768    -609015.6187   -1044748.3474
#Sta/Elev= 30
       0   373.9    3.28  373.01   17.77  370.61    21.2  370.57   25.16   369.8
   36.17  368.09   38.42  367.23   41.35  364.87   45.17  363.98   45.26  363.94
   45.46  362.11   48.45  361.93   51.55  362.08   53.78  364.01   54.56  364.12
   60.23  364.07   60.48  364.06   64.62  367.06   69.71  367.56   76.92  371.42
   78.95  371.58   82.79   374.2   98.96  374.35  101.93  373.19  104.34  373.46
  105.32  373.41  105.89  374.06  106.87  374.01  109.27  374.28  119.06  374.86
#Mann= 4 ,-1 , 0
       0      .2       0   45.17     .05       0   54.56     .05       0
   60.23     .15       0
#XS Ineff= 2 , 0
Permanent Ineff=
       F       F
#Block Obstruct= 1 ,-1
   53.56   54.06  364.93
Bank Sta=45.17,54.56
XS Rating Curve= 0 ,0
Exp/Cntr=0.3,0.1

Type RM Length L Ch R = 1 ,18416.83,19.51,19.31,18.8
XS GIS Cut Line= 4
    -608933.7448   -1044840.0106    -608967.9937   -1044810.7893
-608985.98539999   -1044796.5017    -609023.5562   -1044764.7517
#Sta/Elev= 27
       0  374.51   15.08  370.39   22.91  370.54   25.64  370.51   28.28  369.99
   41.04  365.27   45.46  364.12   48.01  363.02   48.12  361.95    53.3  361.78
   55.49  363.73   56.19  363.86   62.29  363.82   63.37  364.02   64.02  364.06
   64.91  364.31   67.23  364.48   74.88  365.43   82.25  368.43   91.55   369.8
   99.91  370.77  104.42  372.58  111.02  373.18  112.87  373.22  113.53   373.1
   114.8  373.37  117.19   373.5
#Mann= 4 ,-1 , 0
       0      .2       0   45.46     .05       0   56.19     .05       0
   62.29     .15       0
#XS Ineff= 2 , 0
Permanent Ineff=
       F       F
#Block Obstruct= 1 ,-1
   55.47   55.97   364.7
Bank Sta=45.46,56.19
XS Rating Curve= 0 ,0
Exp/Cntr=0.3,0.1