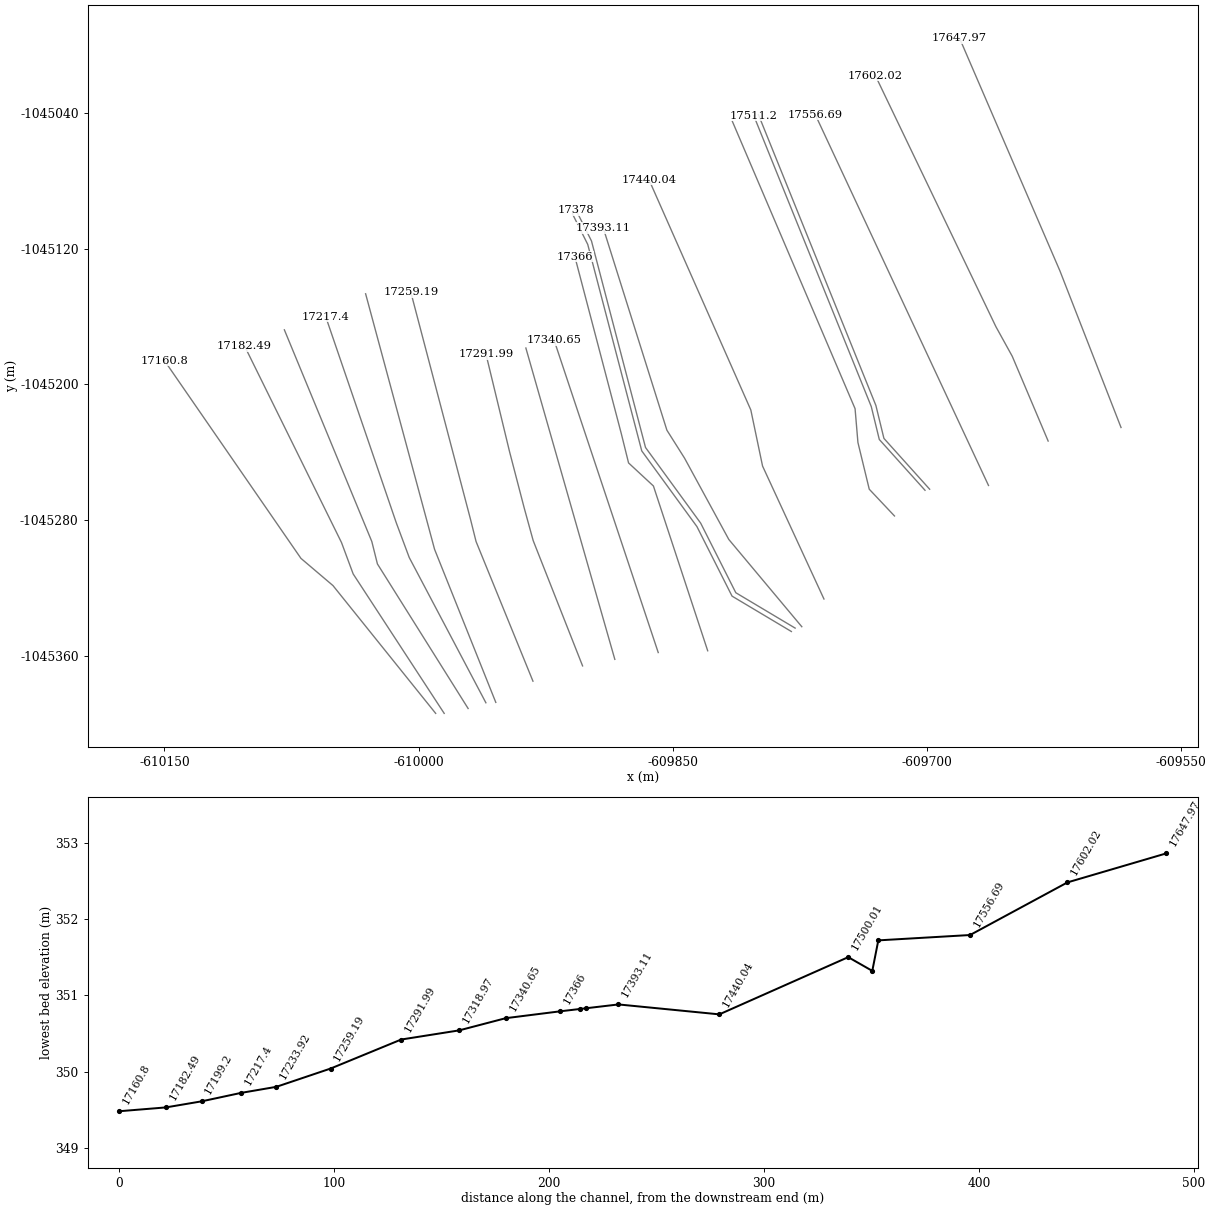
HEC-RAS study PPO_Kvasiny_efektiv.prj: PPO_Kvasiny_efektivita

--- PPO_Kvasiny_efektiv.g12 (geometry) --- (continued)

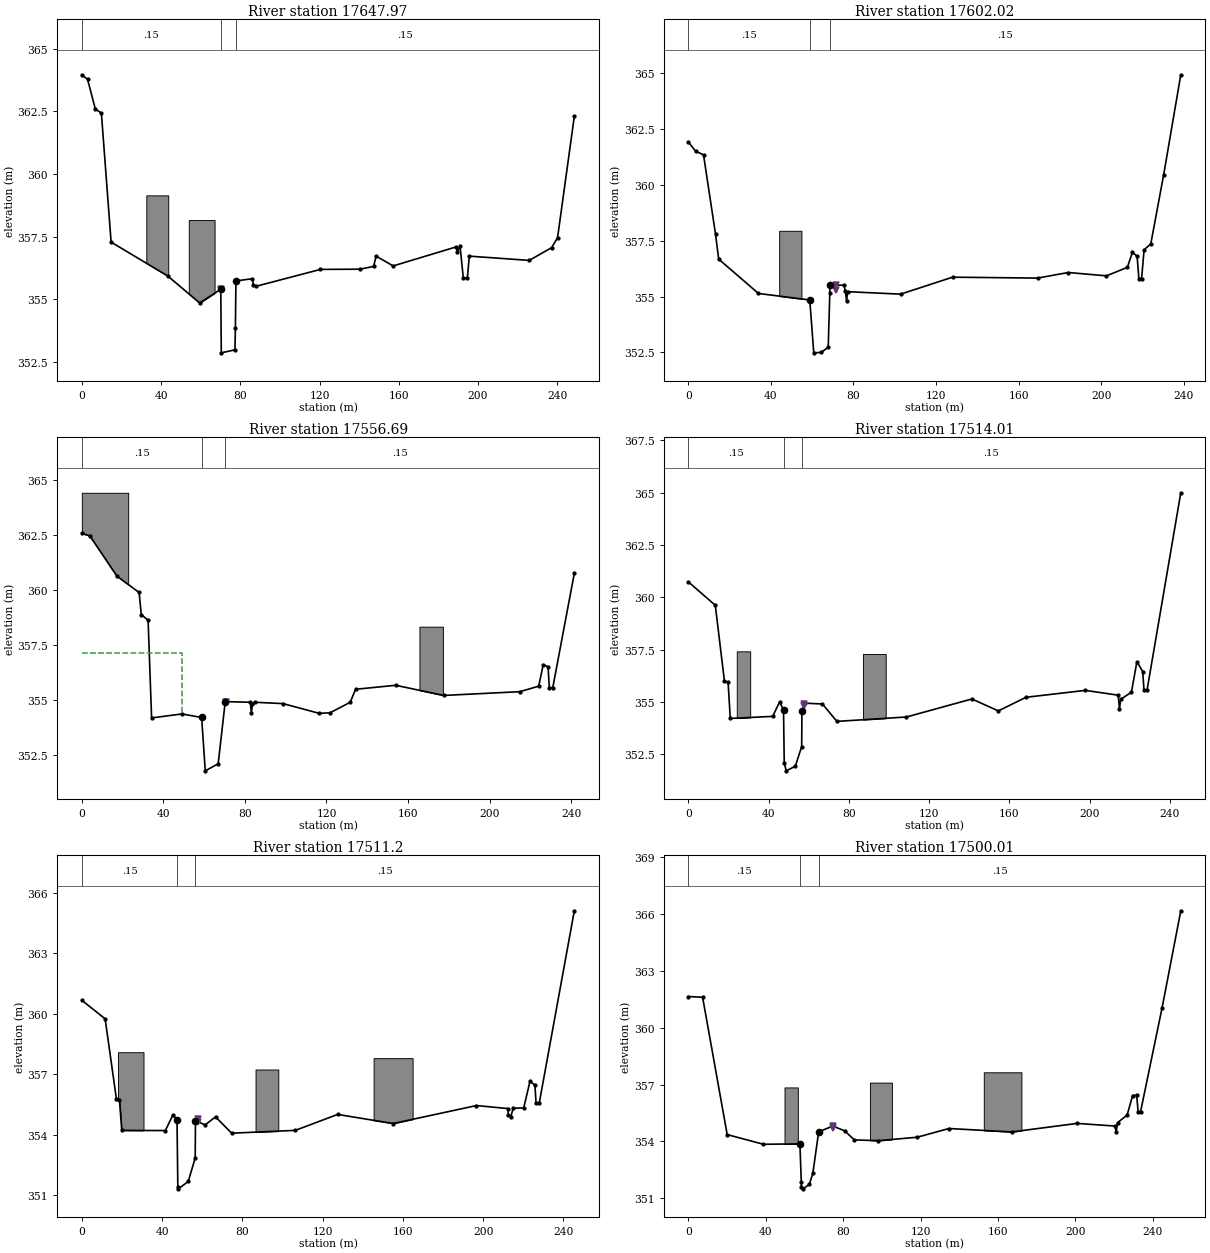
Type RM Length L Ch R = 1 ,17647.97,44.69,45.95,47.64
XS GIS Cut Line= 4
-609585.52739999   -1045225.4584-609605.14359999   -1045175.1529
-609621.57099999    -1045133.065    -609680.7776   -1044995.7996
#Sta/Elev= 30
       0  363.96    2.87  363.78    6.78   362.6    9.86  362.43   14.77  357.28
   43.32  355.93   59.51  354.85   70.15   355.4    70.4  352.86   77.31  352.98
   77.53  353.86    77.8  355.73   86.09  355.82   86.61  355.58   88.12  355.52
  120.47  356.19  140.44   356.2  147.34  356.31  148.56  356.72   157.2  356.33
  189.04  357.09  189.57  356.89  190.98  357.11   192.6  355.85  194.66  355.85
  195.62  356.72  225.89  356.55  237.22  357.06   240.2  357.46  248.66   362.3
#Mann= 3 , 0 , 0
       0     .15       0   70.15    .043       0    77.8     .15       0
Levee=-1,70.09,355.37,0,,,,
#Block Obstruct= 2 ,-1
   32.55   43.62359.1464   53.99   67.02358.1605
Bank Sta=70.15,77.8
XS Rating Curve= 0 ,0
Exp/Cntr=0.3,0.1

Type RM Length L Ch R = 1 ,17602.02,44.99,45.33,43.77
XS GIS Cut Line= 4
    -609628.5299    -1045233.445-609649.70439999   -1045183.4506
    -609659.3708   -1045165.9417    -609730.4928    -1045017.789
#Sta/Elev= 30
       0  361.93     3.5  361.52    7.37  361.35   13.18   357.8   14.71  356.68
   33.99  355.14   58.85  354.85   60.79  352.48    64.4   352.5   67.79  352.73
   68.56  355.16   68.63  355.51   75.39  355.51   76.07  355.26   76.69   354.8
   77.19  355.22  102.87  355.11  128.03  355.87  169.26  355.83  184.11  356.08
   202.6  355.93  212.73  356.31   215.2  356.99  217.47   356.8  218.32  355.81
  219.64  355.81  220.85   357.1  224.09  357.36  230.35  360.47  238.63  364.94
#Mann= 3 ,-1 , 0
       0     .15       0   58.85     .04       0   68.66     .15       0
Levee=0,,,-1,71.59,355.3,,
#Block Obstruct= 1 ,-1
   44.03   54.82357.9499
Bank Sta=58.85,68.63
XS Rating Curve= 0 ,0
Exp/Cntr=0.3,0.1

Type RM Length L Ch R = 1 ,17556.69,44.71,42.68,40.34
XS GIS Cut Line= 2
    -609663.7304   -1045259.6598    -609765.9736   -1045040.7789
#Sta/Elev= 30
       0  362.56    3.89  362.45    17.2  360.62    28.1  359.88   29.15  358.88
    32.5  358.62   34.21  354.19    49.1  354.37   58.77  354.21   60.53  351.79
   66.87  352.11   70.34  354.93   82.63   354.9   83.15  354.41   83.69  354.83
   84.78   354.9   98.66  354.84  116.35   354.4  121.72  354.42  131.64   354.9
  134.28  355.49  153.96  355.67  177.53  355.21  214.78  355.38  224.11  355.63
  226.33  356.61   228.7  356.51  229.31  355.56     231  355.56  241.58  360.75
#Mann= 3 , 0 , 0
       0     .15       0   58.77     .04       0   70.34     .15       0
Levee=0,,,-1,70.54,354.92,,
#XS Ineff= 2 , 0
           49.36  357.13
Permanent Ineff=
       F       F
#Block Obstruct= 2 ,-1
   165.6  177.11358.3292       0   22.74 364.402
Bank Sta=58.77,70.34
XS Rating Curve= 0 ,0
Exp/Cntr=0.3,0.1

Type RM Length L Ch R = 1 ,17514.01,2.8,2.8,2.82
BEGIN DESCRIPTION:
17708  PF 227 ŽELEZNÝ MOSTEK V KVASINÁCH (F39)
END DESCRIPTION:
XS GIS Cut Line= 4
    -609698.4602   -1045261.8683     -609725.443   -1045231.8903
-609730.18059999   -1045212.4594-609799.52079999   -1045040.7983
#Sta/Elev= 30
       0  360.74   13.45  359.62   17.99  356.01   19.82  355.95   20.92  354.22
   42.05  354.32   45.47     355   47.45354.6392   47.81  352.09   48.83  351.72
   53.33  351.94   56.51  352.88   56.63  354.56   57.99  354.95   66.87  354.91
   74.05  354.08  108.73  354.29  141.34  355.15  154.53  354.58  168.29  355.23
  197.86  355.56  214.27  355.33  214.89  354.69  215.58  355.14  220.87  355.47
  223.59  356.93  226.48  356.46  227.14  355.57  228.65  355.57  245.47  364.99
#Mann= 3 ,-1 , 0
       0     .15       0   47.45     .04       0   56.63     .15       0
Levee=0,,,-1,57.59,354.91,,
#Block Obstruct= 2 ,-1
   87.04   98.39357.2969   24.15   30.84357.4231
Bank Sta=47.45,56.63
XS Rating Curve= 0 ,0
Exp/Cntr=0.5,0.3

Type RM Length L Ch R = 1 ,17511.2 ,12.67,11.2,9.7
XS GIS Cut Line= 4
    -609701.1935   -1045262.4972-609728.17619999   -1045232.5193
-609732.91389999   -1045213.0884-609802.25409999   -1045041.4272
#Sta/Elev= 30
       0  360.67   11.61  359.75   17.21  355.79   18.74  355.74   19.88  354.22
   41.62  354.21   45.47     355   47.44  354.71   47.83  351.43   48.13  351.32
   53.04  351.69    56.5  352.85   56.64   354.7   61.45  354.49   66.63  354.89
   74.68  354.08  106.42  354.22  127.47  355.01  155.19  354.56  196.68  355.45
  212.48   355.3  212.49  354.98  213.78  354.89  215.01  355.32  220.24  355.33
  223.38  356.66  225.83  356.46   226.4  355.57  227.98  355.57  245.47  365.11
#Mann= 3 , 0 , 0
       0     .15       0   47.44     .04       0   56.64     .15       0
Levee=0,,,-1,58.03,354.79,,
#Block Obstruct= 3 ,-1
   86.57   97.92357.2387  145.42  164.87357.8016   18.01   30.73358.0956
Bank Sta=47.44,56.64
XS Rating Curve= 0 ,0
Exp/Cntr=0.5,0.3

Type RM Length L Ch R = 1 ,17500.01,58,59.97,58.41
XS GIS Cut Line= 5
-609719.21379999    -1045277.659    -609734.1021   -1045261.8683
     -609740.789   -1045234.2777    -609742.4705   -1045214.3485
-609814.86039999   -1045044.8588
#Sta/Elev= 30
       0  361.64    7.38   361.6   20.08  354.36   38.77  353.85   57.64  353.87
   58.36  351.86   58.37  351.62   59.47   351.5   62.53  351.75   64.32  352.32
   67.25  354.44   67.66  354.52   74.65  354.81   80.73  354.56   85.77  354.08
   98.15  354.04  118.21  354.22   134.6  354.68  167.05   354.5  200.88  354.95
  220.42  354.81  220.99   354.5  221.74  354.99  226.68  355.39   229.5  356.42
  231.61  356.43  232.34  355.57  233.62  355.57  244.74  361.05  254.39  366.16
#Mann= 3 , 0 , 0
       0     .15       0   57.64     .04       0   67.66     .15       0
Levee=0,,,-1,74.48,354.73,,
#XS Ineff= 2 , 0
Permanent Ineff=
       F       F
#Block Obstruct= 3 ,-1
   49.69   56.55356.8469   93.82  105.17357.1008  152.62  172.07357.6448
Bank Sta=57.64,67.66
XS Rating Curve= 0 ,0
Exp/Cntr=0.3,0.1

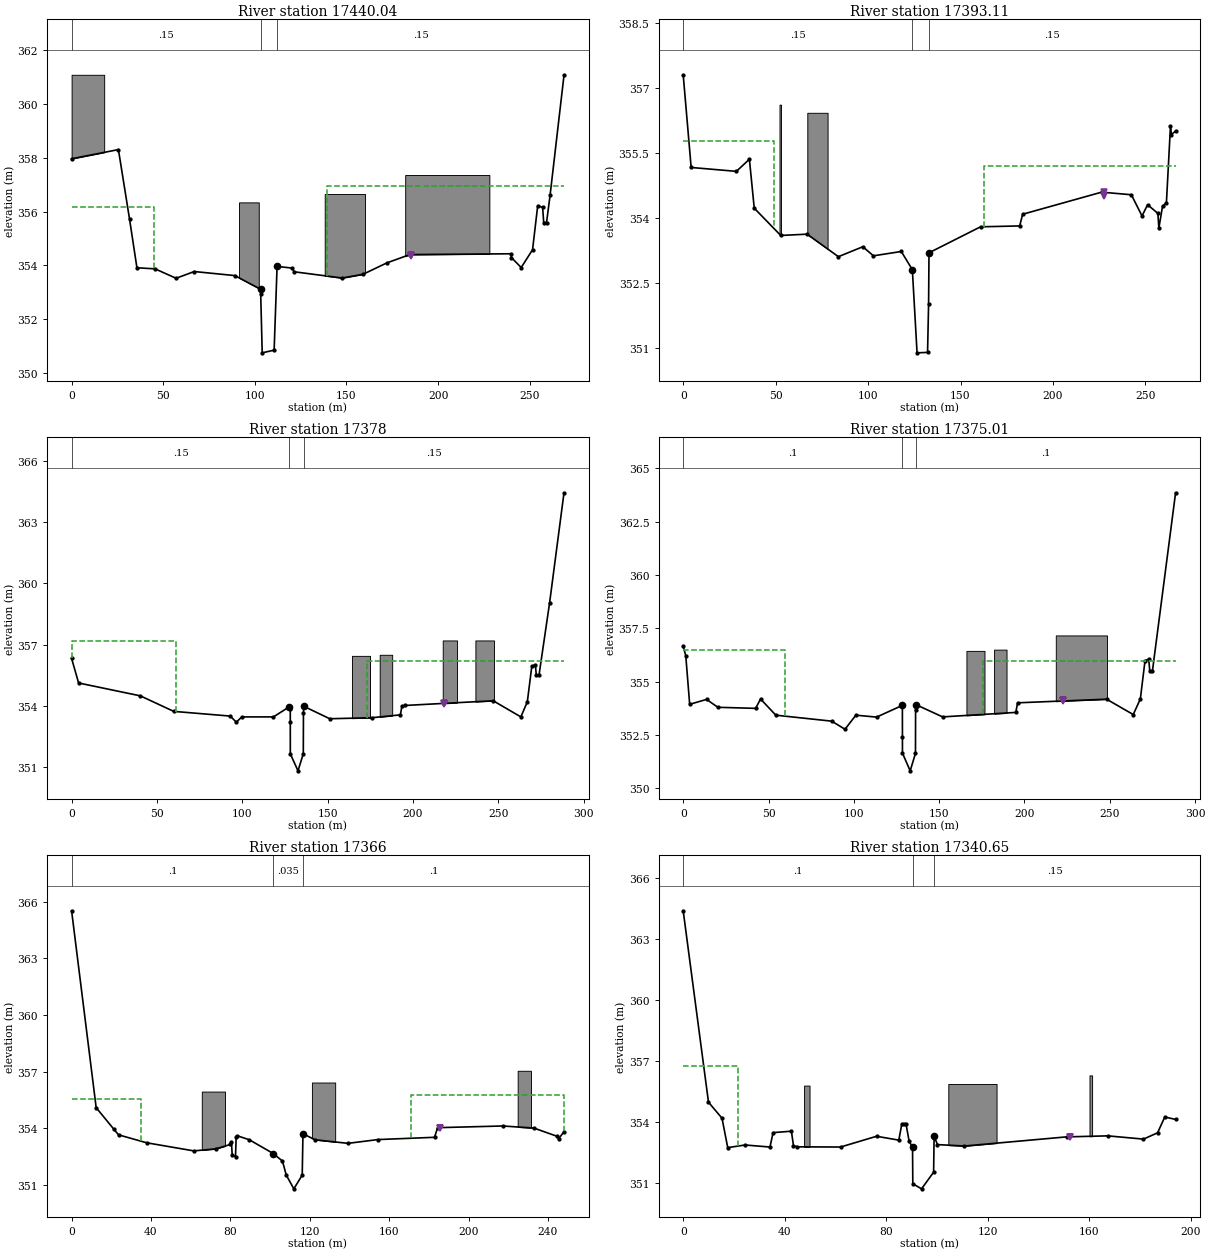
Type RM Length L Ch R = 1 ,17440.04,41.3,46.93,51.33
XS GIS Cut Line= 4
-609760.83949999    -1045326.651-609797.06219999   -1045248.2126
    -609803.9891   -1045215.1089    -609864.0548   -1045079.3023
#Sta/Elev= 29
       0  357.96   25.55   358.3   31.64  355.71   35.65  353.91   45.53  353.87
   57.03  353.52   66.93  353.77   89.06  353.62  103.17  353.11   103.2  352.94
  104.02  350.75  110.53  350.85  112.14  353.96  120.22   353.9  121.54  353.76
  147.61  353.53  159.11  353.67     172  354.09  184.58   354.4  239.73  354.43
  240.01  354.29  245.36  353.92  251.56  354.58  254.38  356.22  257.06  356.15
  257.65  355.59   259.2  355.59  261.12   356.6  268.72  361.06
#Mann= 3 , 0 , 0
       0     .15       0  103.17     .04       0  112.14     .15       0
Levee=0,,,-1,185.16,354.36,,
#XS Ineff= 2 , 0
           44.86  356.16  139.26          356.96
Permanent Ineff=
       F       F
#Block Obstruct= 4 ,-1
       0   17.78361.0793  182.05  227.99357.3547  138.13  160.15356.6496
   91.36  102.14356.3394
Bank Sta=103.17,112.14
XS Rating Curve= 0 ,0
Exp/Cntr=0.3,0.1

Type RM Length L Ch R = 1 ,17393.11,13.26,15.1,14.97
XS GIS Cut Line= 5
    -609773.9127   -1045343.0054    -609816.9842   -1045291.5139
-609843.09259999   -1045243.5518-609853.51619999   -1045227.0443
    -609891.0705   -1045107.7374
#Sta/Elev= 30
       0   357.3    4.31  355.16   28.77  355.07   35.81  355.35   38.43  354.22
   52.76  353.59   67.02  353.62   83.96   353.1   97.17  353.33  102.89  353.12
  117.97  353.22  123.95   352.8   126.5  350.88  132.18  350.89  132.74  352.01
  132.96  353.19  160.85  353.79  182.01  353.81  183.61  354.08  226.35  354.59
  242.41  354.53  248.19  354.04   251.2   354.3  256.76   354.1  257.29  353.76
   259.3  354.27  261.37  354.34  263.58  356.12  264.05  355.92  266.34     356
#Mann= 3 , 0 , 0
       0     .15       0  123.95     .04       0  132.96     .15       0
Levee=0,,,-1,227.77,354.5,,
#XS Ineff= 2 , 0
           48.85  355.76  162.82           355.2
Permanent Ineff=
       F       F
#Block Obstruct= 2 ,-1
   52.09    52.9356.6096   67.13    78.1356.4224
Bank Sta=123.95,132.96
XS Rating Curve= 0 ,0
Exp/Cntr=0.3,0.1

Type RM Length L Ch R = 1 ,17378   ,2.96,2.99,2.78
XS GIS Cut Line= 6
     -609777.842   -1045343.8274-609812.85159999     -1045322.95
    -609833.5683   -1045281.9181    -609866.1356    -1045237.247
    -609898.0165   -1045115.3894    -609907.0396   -1045097.3429
#Sta/Elev= 30
       0  356.33    4.12  355.13   40.29   354.5   59.87  353.74   93.02  353.51
   96.51  353.21   99.77  353.47  118.31  353.47  127.69  353.97  128.16  353.84
  128.17  353.23  128.18  351.66  132.69  350.83  135.79  351.67  135.87  353.64
  136.03  353.99   151.3  353.38  175.95  353.43  192.67  353.57  193.59  353.99
  195.42  354.03  247.07  354.26  263.29  353.47  267.08  354.21  269.69  355.94
  271.77  356.02  272.35  355.51  273.92  355.51  280.14  359.06  288.57  364.44
#Mann= 3 , 0 , 0
       0     .15       0  127.69     .04       0  136.03     .15       0
Levee=0,,,-1,218.24,354.09,,
#XS Ineff= 2 , 0
           61.14  357.17  173.38          356.23
Permanent Ineff=
       F       F
#Block Obstruct= 4 ,-1
   164.3  174.89356.4578  180.57  187.88356.5107   217.5   225.9357.2125
  236.65  247.52357.2125
Bank Sta=127.69,136.03
XS Rating Curve= 0 ,0
Exp/Cntr=0.5,0.3

Type RM Length L Ch R = 1 ,17375.01,8.74,9.01,9.67
XS GIS Cut Line= 6
    -609780.0582   -1045345.8438    -609815.0678   -1045324.9665
-609835.78449999   -1045283.9345-609868.35179999   -1045239.2635
    -609900.2327   -1045117.4058     -609909.256   -1045099.3593
#Sta/Elev= 30
       0  356.66    1.51  356.22     3.8  353.94   13.71  354.17   20.31   353.8
   42.47  353.75   45.33  354.19   54.28  353.43   87.05  353.15   94.83  352.77
   101.2  353.43  113.33  353.34  128.45  353.89  128.49  352.43   128.5  351.65
  133.03  350.82  136.13  351.64   136.2  353.67  136.26  353.93  152.01  353.35
  194.94  353.56  195.97  354.01  248.13  354.18  263.75  353.46  267.91  354.19
  270.65  355.98  272.83  356.06  273.43  355.51  275.01  355.51  288.57  363.86
#Mann= 3 , 0 , 0
       0      .1       0  128.45     .04       0  136.26      .1       0
Levee=0,,,-1,222.58,354.16,,
#XS Ineff= 2 , 0
           59.76  356.49  175.81          355.98
Permanent Ineff=
       F       F
#Block Obstruct= 3 ,-1
  165.99  176.58 356.446  182.19   189.5356.5049  218.36  248.38357.1706
Bank Sta=128.45,136.26
XS Rating Curve= 0 ,0
Exp/Cntr=0.5,0.3

Type RM Length L Ch R = 1 ,17366   ,28.61,25.35,19.86
XS GIS Cut Line= 5
    -609829.4397   -1045357.2129    -609861.4726   -1045259.9622
    -609876.1358   -1045246.3611    -609880.4211   -1045229.0826
    -609907.8099   -1045124.7443
#Sta/Elev= 30
       0  365.52   12.38  355.09   21.35  353.94   23.66  353.65    37.8  353.23
    61.6   352.8    72.7  352.91   79.98  353.14   80.52  353.26   80.93  352.56
   82.58   352.5    82.9  353.53    83.5   353.6   89.54  353.39   101.6  352.66
  106.24  352.26  108.13  351.52  111.97  350.79  116.19  351.52  116.56  353.71
   122.6  353.39  139.25   353.2  154.31   353.4  182.83  353.52  184.41  354.03
  217.23  354.12  232.88  354.01  244.41  353.58   245.3  353.44  248.07  353.81
#Mann= 3 , 0 , 0
       0      .1       0   101.6    .035       0  116.56      .1       0
Levee=0,,,-1,185.62,354.02,,
#XS Ineff= 2 , 0
           34.79  355.55  171.05          355.75
Permanent Ineff=
       F       F
#Block Obstruct= 3 ,-1
   65.59   77.29355.9429  224.73  231.42357.0443  121.07  132.79 356.422
Bank Sta=101.6,116.56
XS Rating Curve= 0 ,0
Exp/Cntr=0.3,0.1

Type RM Length L Ch R = 1 ,17340.65,22.16,21.68,21.33
XS GIS Cut Line= 2
    -609858.6317   -1045358.2556    -609920.0152   -1045174.1052
#Sta/Elev= 30
       0   364.4    9.97  354.97    15.3  354.18   17.56  352.73   24.41  352.86
   34.21  352.76   35.44  353.47   42.65  353.54   43.48  352.83   44.98  352.77
   62.04  352.76   76.22  353.29      85   353.1   86.18  353.89   87.07   353.9
   87.83   353.9   89.06  353.05   90.41  352.74   90.52  350.95   93.96   350.7
   98.72  351.52   98.92  353.29  100.25  352.88  110.89  352.81  151.11  353.26
  167.41  353.31  181.44  353.15  187.01  353.46  189.85  354.24  194.11  354.12
#Mann= 3 , 0 , 0
       0      .1       0   90.41    .037       0   98.92     .15       0
Levee=0,,,-1,152.66,353.25,,
#XS Ineff= 2 , 0
           21.48  356.74
Permanent Ineff=
       F       F
#Block Obstruct= 3 ,-1
  104.51  123.54355.8673   47.65   49.81355.7874  160.17   161.2356.2895
Bank Sta=90.41,98.92
XS Rating Curve= 0 ,0
Exp/Cntr=0.3,0.1

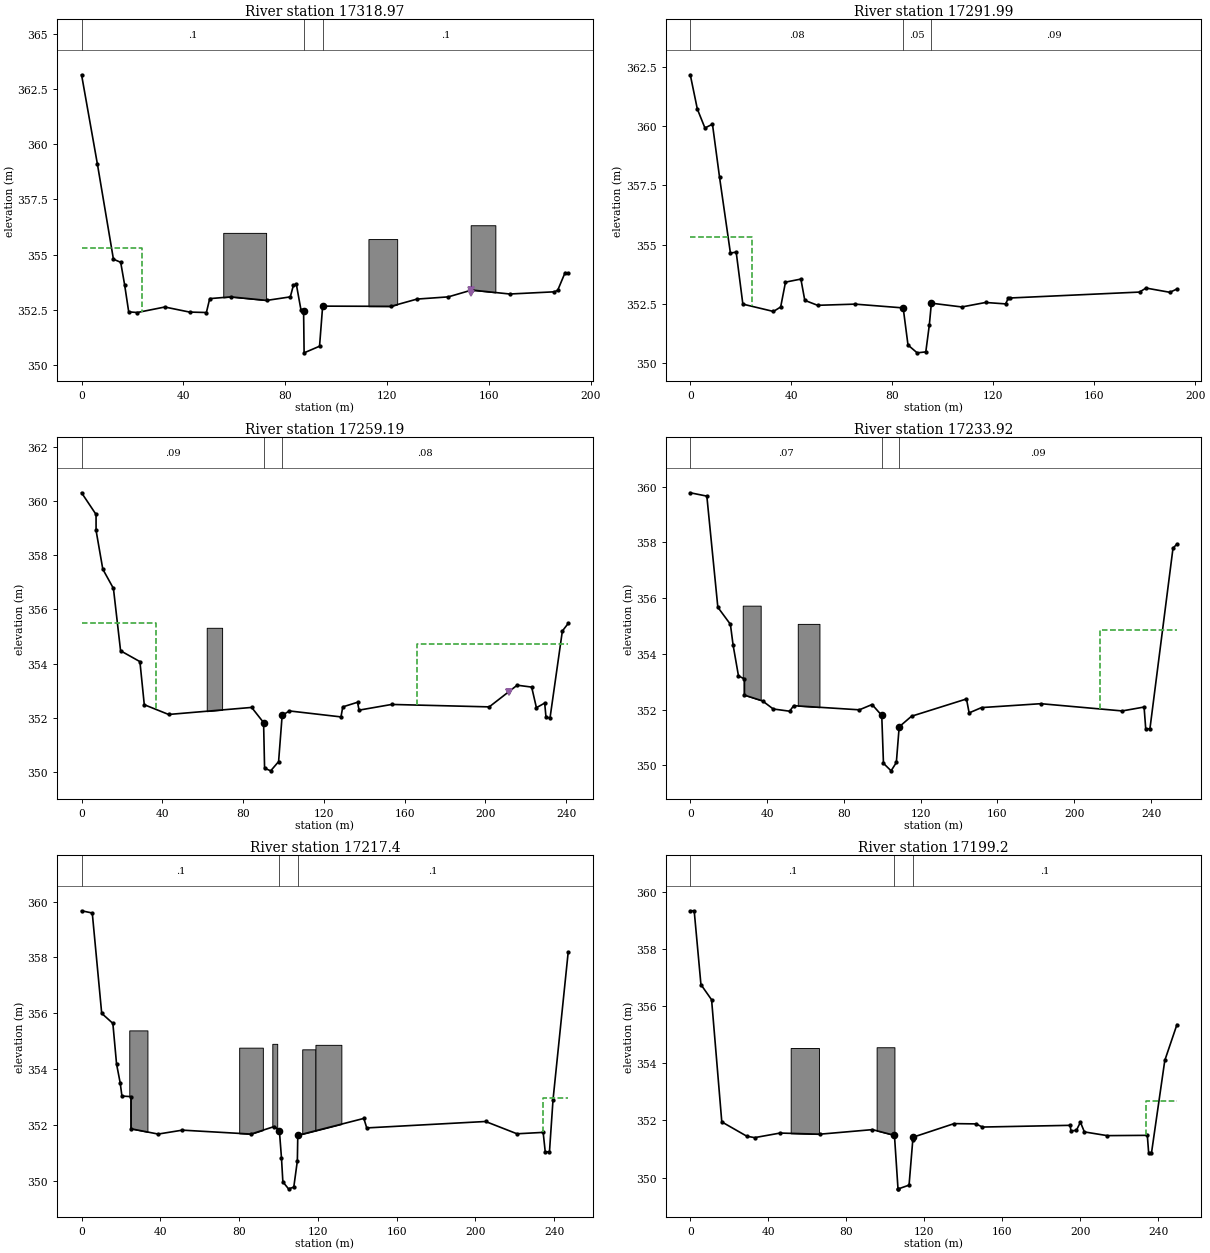
Type RM Length L Ch R = 1 ,17318.97,27.08,26.98,26.72
XS GIS Cut Line= 2
    -609884.2434   -1045362.2772    -609936.7369   -1045178.5502
#Sta/Elev= 30
       0  363.16    6.23   359.1   12.51  354.79   15.36  354.65   16.89  353.64
   18.51   352.4   21.88  352.37   32.69  352.62    42.4  352.39   49.01  352.37
   50.32     353   58.54  353.08   72.71  352.92   81.96  353.08   83.21  353.62
   84.33  353.65   86.16  352.48   87.18  352.44   87.38  350.54   93.44  350.84
   94.66  352.66  121.45  352.65  131.72  352.98  143.99  353.08  153.18  353.39
  168.15  353.21  185.65  353.31  186.95  353.38  189.85  354.18  191.08  354.15
#Mann= 3 , 0 , 0
       0      .1       0   87.18    .045       0   94.66      .1       0
Levee=0,,,-1,152.77,353.27,,
#XS Ineff= 2 , 0
           23.67  355.28
Permanent Ineff=
       F       F
#Block Obstruct= 3 ,-1
   55.63   72.46355.9849  152.78  162.47356.3312  112.64  123.92355.7037
Bank Sta=87.18,94.66
XS Rating Curve= 0 ,0
Exp/Cntr=0.3,0.1

Type RM Length L Ch R = 1 ,17291.99,31.82,32.8,32.37
XS GIS Cut Line= 5
    -609903.2769   -1045366.1317    -609932.4292   -1045292.1715
    -609937.7335   -1045272.8878    -609946.3473   -1045239.7977
-609960.23189999   -1045182.3602
#Sta/Elev= 30
       0  362.18     2.8  360.73    5.81  359.93    8.79  360.09   11.59  357.85
    15.9  354.64   18.19  354.68   20.83  352.48   32.95  352.17   35.81  352.36
   37.72  353.41   43.82  353.54   45.36  352.64   50.44  352.43    65.3  352.48
   84.34  352.32   86.25  350.75   89.88  350.42    93.3  350.46   94.69  351.59
   95.51  352.52  107.58  352.36  116.98  352.55  124.91  352.49  125.98  352.73
  126.71  352.74  177.97  352.99  180.53  353.16  189.99  352.98  192.78  353.12
#Mann= 3 , 0 , 0
       0     .08       0   84.34     .05       0   95.51     .09       0
#XS Ineff= 2 , 0
           24.36  355.33
Permanent Ineff=
       F       F
Bank Sta=84.34,95.51
XS Rating Curve= 0 ,0
Exp/Cntr=0.3,0.1

Type RM Length L Ch R = 1 ,17259.19,24.97,25.27,25.19
XS GIS Cut Line= 4
-609932.55249999   -1045375.1618    -609966.1363   -1045292.7288
-609969.44359999   -1045279.4995-610004.63879999   -1045145.5948
#Sta/Elev= 30
       0   360.3    7.18   359.5    7.19  358.91   10.53  357.48   15.79  356.77
   19.33  354.47   28.91  354.07   31.07  352.48   43.13  352.12   84.27  352.38
   90.18  351.82   90.67  350.14   93.69  350.04   97.61  350.38   99.38  352.09
     103  352.25  128.52  352.03  129.41   352.4  136.72  352.57  137.49  352.28
  153.66  352.49  201.97   352.4  215.81   353.2  222.99  353.13  225.34  352.37
  229.44  352.54  230.09  352.02  232.08  351.99   238.2   355.2   241.1  355.48
#Mann= 3 , 0 , 0
       0     .09       0   90.18     .05       0   99.38     .08       0
Levee=0,,,-1,211.75,352.96,,
#XS Ineff= 2 , 0
           36.81  355.48  166.23          354.73
Permanent Ineff=
       F       F
#Block Obstruct= 1 ,-1
   62.01   69.63355.3181
Bank Sta=90.18,99.38
XS Rating Curve= 0 ,0
Exp/Cntr=0.3,0.1

Type RM Length L Ch R = 1 ,17233.92,15.49,16.52,17.84
XS GIS Cut Line= 4
    -609954.4877   -1045387.6656    -609990.6103    -1045297.359
-609995.24049999    -1045280.161-610031.30889999   -1045146.5473
#Sta/Elev= 30
       0  359.78    8.63  359.66   14.36  355.67    20.9  355.06   22.29  354.32
    25.1  353.21   28.11   353.1   28.12  352.52   37.62  352.31   43.21  352.02
   51.78  351.94   53.85  352.14   88.06  351.99   94.68  352.18   99.73  351.79
  100.62  350.07   104.6   349.8  107.33   350.1  108.81  351.38  115.24  351.76
  143.86  352.38  145.24  351.88  151.69  352.07  182.57  352.21  224.98  351.95
  236.36  352.09  237.22  351.31  239.41  351.31  251.42  357.79  253.47  357.94
#Mann= 3 , 0 , 0
       0     .07       0   99.73     .05       0  108.81     .09       0
#XS Ineff= 2 , 0
                          213.22          354.86
Permanent Ineff=
       F       F
#Block Obstruct= 2 ,-1
   27.33   36.67 355.729   55.99   67.28355.0744
Bank Sta=99.73,108.81
XS Rating Curve= 0 ,0
Exp/Cntr=0.3,0.1

Type RM Length L Ch R = 1 ,17217.4 ,18.02,18.21,18.04
XS GIS Cut Line= 4
-609960.33769999   -1045387.8889    -610005.5549   -1045302.1949
-610013.21709999   -1045281.6724    -610054.8039   -1045160.1999
#Sta/Elev= 30
       0  359.67    5.44  359.59   10.23     356    15.9  355.64   17.77  354.19
   19.65   353.5    20.5  353.04   25.06  353.02   25.07  351.87   38.89  351.68
   51.19  351.82   86.09  351.68   97.87  351.95  100.48   351.8  101.54  350.83
  102.25  349.97  105.12  349.72  107.79  349.78  109.61  350.72  109.82   351.6
  110.08  351.64  143.38  352.24  144.85   351.9  205.21  352.13  221.17  351.69
  234.46  351.74  235.52  351.04  237.67  351.05  239.46   352.9  247.19   358.2
#Mann= 3 , 0 , 0
       0      .1       0  100.48     .05       0  110.08      .1       0
#XS Ineff= 2 , 0
                          234.27          352.97
Permanent Ineff=
       F       F
#Block Obstruct= 5 ,-1
   80.06   92.08354.7722   96.89   99.38354.9088  112.08   118.8 354.712
   118.8  131.96354.8729   24.23   33.46355.3898
Bank Sta=100.48,110.08
XS Rating Curve= 0 ,0
Exp/Cntr=0.3,0.1

Type RM Length L Ch R = 1 ,17199.2 ,15.17,16.71,17.13
XS GIS Cut Line= 4
-609970.81529999   -1045391.2756-610024.34479999    -1045305.958
    -610027.6521   -1045292.7288-610079.25149999   -1045167.8199
#Sta/Elev= 30
       0  359.33    2.01  359.33    5.47  356.75   10.93  356.22   16.16  351.95
   28.98  351.45   32.98   351.4   46.06  351.56   66.39  351.52    93.4  351.68
  104.68  351.48  106.49  349.62  106.73  349.61  112.17  349.74  114.08  351.32
  114.43  351.42  135.27  351.89  146.56  351.88  149.72  351.77  194.77  351.83
  195.14  351.64  197.92  351.65  200.02  351.94  202.05   351.6  213.74  351.47
  234.32  351.48  235.01  350.86  236.43  350.85  243.28   354.1   249.5  355.35
#Mann= 3 , 0 , 0
       0      .1       0  104.68     .05       0  114.43      .1       0
#XS Ineff= 2 , 0
                          233.83          352.68
Permanent Ineff=
       F       F
#Block Obstruct= 2 ,-1
   51.48   65.97354.5328   95.54  104.67354.5594
Bank Sta=104.68,114.43
XS Rating Curve= 0 ,0
Exp/Cntr=0.3,0.1

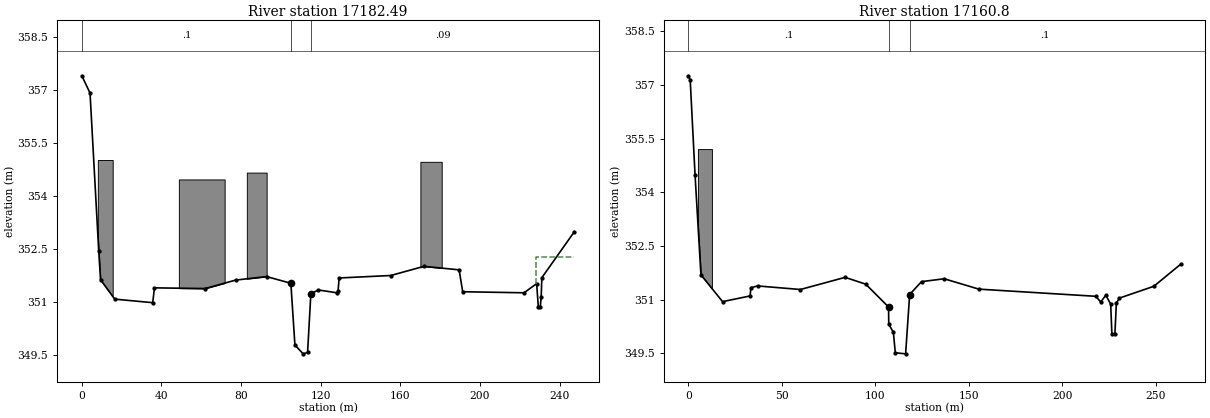
Type RM Length L Ch R = 1 ,17182.49,12.56,21.69,26.56
XS GIS Cut Line= 4
-609984.94399999   -1045394.1508-610038.65459999   -1045311.8652
    -610045.5337   -1045293.3443    -610102.7465   -1045177.3449
#Sta/Elev= 30
       0  357.41    4.11  356.92    8.48  352.44    9.38  351.63   16.51  351.08
    35.6  350.98   36.46   351.4   61.86  351.38   77.25  351.62   92.75  351.72
  104.98  351.53  107.02  349.78  111.16  349.53  113.38  349.57  115.02  351.23
  118.76  351.34  128.15  351.26   128.7  351.32  129.24  351.68  155.18  351.75
  171.85  352.01  189.49  351.91   191.3  351.29  222.11  351.26  228.44  351.52
  229.27  350.86  230.26  350.86   230.7  351.14  231.06  351.69  247.36  352.99
#Mann= 3 , 0 , 0
       0      .1       0  104.98     .05       0  115.02     .09       0
#XS Ineff= 2 , 0
                          228.35          352.28
Permanent Ineff=
       F       F
#Block Obstruct= 4 ,-1
   82.86   92.82354.6667    8.03   15.49355.0234   48.72   71.72354.4726
  170.04  180.75354.9718
Bank Sta=104.98,115.02
XS Rating Curve= 0 ,0
Exp/Cntr=0.3,0.1

Type RM Length L Ch R = 1 ,17160.8 ,13.11,14.81,16.5
XS GIS Cut Line= 4
-609989.97109999   -1045394.1508    -610050.5608   -1045318.7444
-610069.46269999   -1045302.6894-610150.05409999   -1045185.9174
#Sta/Elev= 30
       0  357.26       1  357.15    3.62  354.47    6.75  351.69   18.33  350.94
   33.03   351.1    33.5  351.33   37.06  351.38   59.95  351.28   83.86  351.62
   94.89  351.43  107.11  350.79  107.21  350.31  109.69  350.08  110.71  349.51
  116.23  349.48  118.39  351.14  124.73   351.5  136.87  351.58  155.45  351.29
  217.95  351.09   220.6  350.93  223.32  351.12  225.93  350.87  226.57  350.03
  228.16  350.03  228.97   350.9  230.61  351.04  249.01  351.37  263.42  351.99
#Mann= 3 , 0 , 0
       0      .1       0  107.11     .05       0  118.39      .1       0
#Block Obstruct= 1 ,-1
    5.14   12.62355.2086
Bank Sta=107.11,118.39
XS Rating Curve= 0 ,0
Exp/Cntr=0.3,0.1