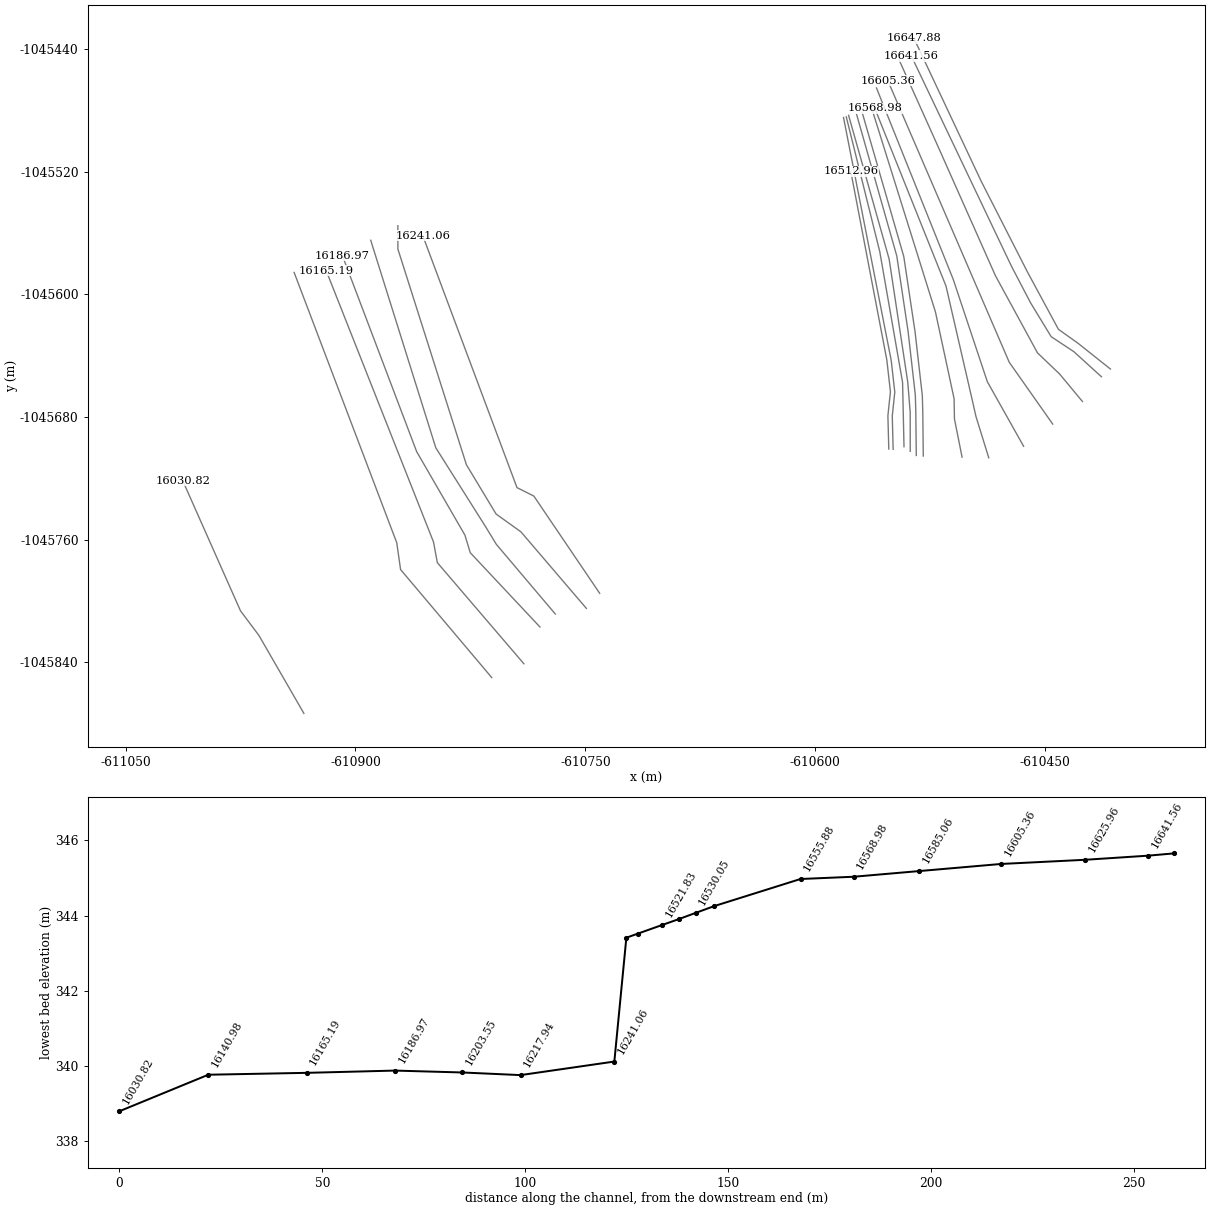
HEC-RAS study PPO_Kvasiny_efektiv.prj: PPO_Kvasiny_efektivita

--- PPO_Kvasiny_efektiv.g12 (geometry) --- (continued)

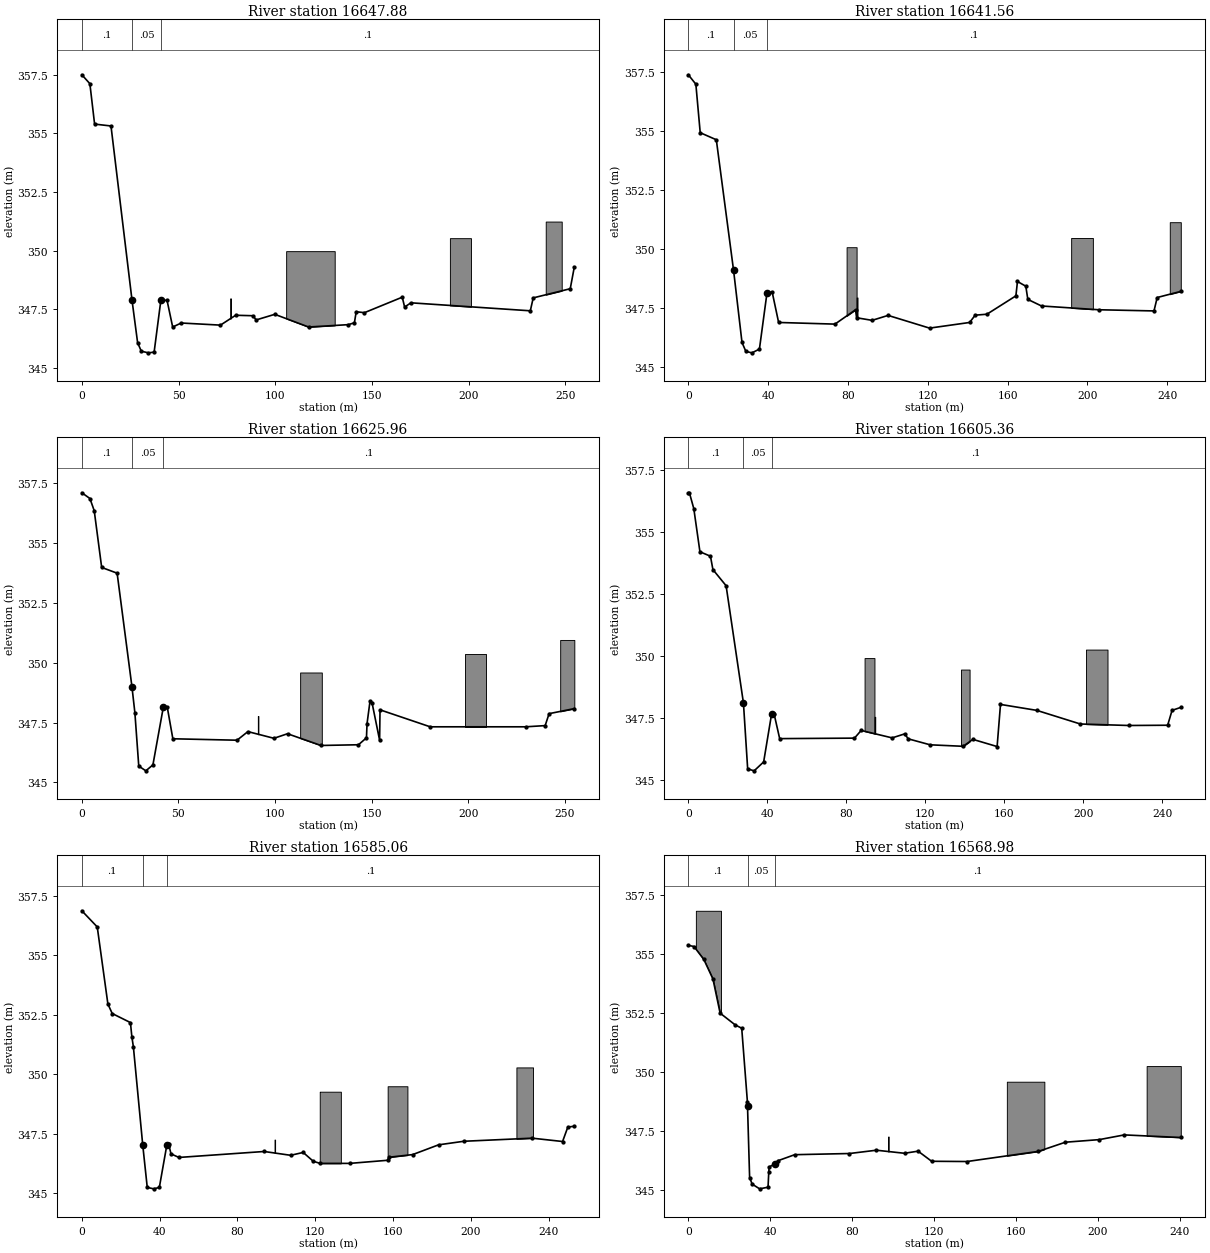
Type RM Length L Ch R = 1 ,16647.88,5.99,6.32,7.53
XS GIS Cut Line= 6
-610407.45239999   -1045648.6625    -610428.5344   -1045631.8985
-610441.36149999   -1045622.7545-610461.68149999   -1045585.1624
    -610491.7806   -1045526.1073-610535.63219999   -1045432.9065
#Sta/Elev= 30
       0  357.49    4.15  357.11    6.59  355.39   15.07  355.31   25.93   347.9
   28.84  346.08   30.75  345.72   34.39  345.65   37.38  345.68   40.85  347.88
   44.05  347.89   46.97  346.75   51.41  346.92   71.69  346.83   79.54  347.25
   88.55  347.23   90.11  347.05   99.78  347.29  117.27  346.75  137.81  346.85
  140.96  346.93  141.89   347.4  146.14  347.36  165.71  348.02  166.93   347.6
  170.19  347.78  231.94  347.44  233.44  347.99  252.59  348.38   254.7  349.31
#Mann= 3 , 0 , 0
       0      .1       0   25.93     .05       0   40.85      .1       0
#XS Ineff= 2 , 0
Permanent Ineff=
       F       F
#Block Obstruct= 4 ,-1
  239.91  248.18  351.24  190.35  201.24 350.533  105.66  130.77  349.98
   76.74   77.05  347.97
Bank Sta=25.93,40.85
XS Rating Curve= 0 ,0
Exp/Cntr=0.3,0.1

Type RM Length L Ch R = 1 ,16641.56,17.07,15.6,12.26
XS GIS Cut Line= 6
-610413.30689999   -1045653.7066-610431.29479999   -1045637.3368
-610446.09189999    -1045627.568    -610459.5562   -1045605.4465
    -610472.0445   -1045581.5282    -610537.3255   -1045444.4423
#Sta/Elev= 30
       0   357.4    3.78     357    5.96  354.94   14.03  354.64   22.68  349.09
    26.9  346.03   28.84  345.65   31.89  345.59   35.63  345.75   39.44  348.15
   42.05  348.16   45.25  346.88   73.49  346.81   83.79  347.42   84.32  347.08
   92.09  346.97   100.1  347.18  120.88  346.64  140.97  346.88  143.73  347.19
  149.61  347.23  164.14  348.01  164.93  348.62  169.11  348.42  170.12  347.86
  176.98  347.58  205.67  347.42  233.34  347.37  234.95  347.94  246.77   348.2
#Mann= 3 , 0 , 0
       0      .1       0   22.68     .05       0   39.44      .1       0
#XS Ineff= 2 , 0
Permanent Ineff=
       F       F
#Block Obstruct= 4 ,-1
  241.25  246.77 351.139   79.31   84.32 350.077  191.83  202.72 350.469
   84.32   84.79  347.94
Bank Sta=22.68,39.44
XS Rating Curve= 0 ,0
Exp/Cntr=0.3,0.1

Type RM Length L Ch R = 1 ,16625.96,21.61,20.6,17.48
XS GIS Cut Line= 6
-610425.68789999   -1045669.8678     -610440.574   -1045651.9392
-610455.03269999   -1045638.1208     -610482.421   -1045587.8698
    -610520.3187      -1045502.6-610545.36879999   -1045446.8765
#Sta/Elev= 30
       0   357.1    4.18  356.86    6.41  356.35   10.26  353.98   18.26  353.74
   25.94  348.99   27.45  347.91   29.46  345.68   33.12  345.48   36.79  345.73
   42.22  348.16   44.24  348.13   47.11  346.82   80.33  346.76   85.96  347.12
   99.43  346.84  106.46  347.03   123.8  346.54   143.2  346.57  147.34  346.86
  147.63  347.45  149.17  348.39  150.21  348.33  154.14  346.76  154.35  348.03
  180.32  347.32  229.76  347.32  239.84  347.37  241.88  347.87  254.94  348.08
#Mann= 3 , 0 , 0
       0      .1       0   25.94     .05       0   42.22      .1       0
#XS Ineff= 2 , 0
Permanent Ineff=
       F       F
#Block Obstruct= 4 ,-1
  247.62  254.94  350.95  198.32  209.22  350.38     113  124.22  349.59
    91.1    91.4  347.77
Bank Sta=25.94,42.22
XS Rating Curve= 0 ,0
Exp/Cntr=0.3,0.1

Type RM Length L Ch R = 1 ,16605.36,21.02,20.3,16.27
XS GIS Cut Line= 3
-610445.09629999   -1045684.5852-610473.44709999   -1045644.2738
-610552.67139999    -1045460.529
#Sta/Elev= 30
       0  356.58     .55  356.59    2.78  355.95    5.88  354.21   11.21  354.03
   12.46  353.49   19.13  352.84   27.91  348.11   30.05  345.45   33.32  345.37
   38.15  345.73   42.18  347.67   43.48  347.65   46.26  346.67   84.14  346.69
   87.53     347  103.21   346.7  109.51  346.86  111.41  346.66  122.47  346.42
  139.16  346.36   144.1  346.64  156.37  346.35  158.08  348.05  176.45  347.81
  198.52  347.26  222.94   347.2  242.73  347.21  244.96  347.81  249.38  347.93
#Mann= 3 , 0 , 0
       0      .1       0   27.91     .05       0   42.18      .1       0
#XS Ineff= 2 , 0
Permanent Ineff=
       F       F
#Block Obstruct= 4 ,-1
  138.07  142.43 349.457   89.25   94.26  349.92  201.36  212.27 350.263
   94.26   94.66  347.55
Bank Sta=27.91,42.18
XS Rating Curve= 0 ,0
Exp/Cntr=0.3,0.1

Type RM Length L Ch R = 1 ,16585.06,17.86,16.08,10.48
XS GIS Cut Line= 4
    -610464.0819   -1045699.0756    -610487.7346   -1045656.9739
    -610509.9596   -1045590.2987    -610560.0797   -1045465.2915
#Sta/Elev= 30
       0  356.87    7.92  356.19   13.39  352.95   15.62  352.55   24.98  352.17
   25.73  351.56   26.49  351.16    31.3  347.03   33.63  345.24   36.97  345.18
   39.85  345.24   43.72  347.03   44.65  347.06   45.84  346.65   49.93   346.5
   93.75  346.75  107.37  346.59  113.82  346.71  118.99  346.34  122.48  346.25
  137.76  346.25  157.18  346.38  158.11  346.51  170.11  346.62  183.44  347.03
  196.43  347.18  231.58  347.31  247.21  347.17  249.92  347.78  253.25  347.81
#Mann= 3 , 0 , 0
       0      .1       0    31.3     .05       0   43.72      .1       0
#XS Ineff= 2 , 0
Permanent Ineff=
       F       F
#Block Obstruct= 4 ,-1
  122.33  133.19 349.264  157.26  167.42 349.493  223.47  232.02 350.285
   99.07   99.38  347.25
Bank Sta=31.3,43.72
XS Rating Curve= 0 ,0
Exp/Cntr=0.3,0.1

Type RM Length L Ch R = 1 ,16568.98,14.3,13.1,11.02
XS GIS Cut Line= 5
    -610486.8255   -1045706.5634-610495.14299999   -1045679.7281
    -610497.7888   -1045668.0863    -610514.7221    -1045594.532
    -610561.2439   -1045478.4149
#Sta/Elev= 29
       0  355.37    2.76  355.32    7.58  354.77   12.03  353.94   15.54  352.49
   22.92  351.99   26.09  351.85   28.89   348.7   28.92  348.54   29.95  345.51
   31.19  345.23   34.85  345.03   38.95   345.1   39.31  345.75   39.49  345.96
   42.33  346.09   43.66  346.22   51.97  346.48   78.74  346.53   91.89  346.67
  105.62  346.54  112.26  346.63  118.88   346.2  136.17  346.19     171  346.62
  184.22  347.01  200.78  347.12  212.99  347.32   240.6  347.21
#Mann= 3 , 0 , 0
       0      .1       0   28.92     .05       0   42.33      .1       0
#XS Ineff= 2 , 0
Permanent Ineff=
       F       F
#Block Obstruct= 4 ,-1
    3.69   15.95 356.837  155.62  173.94 349.579  223.92   240.6 350.243
   97.59    97.9  347.25
Bank Sta=28.92,42.33
XS Rating Curve= 0 ,0
Exp/Cntr=0.3,0.1

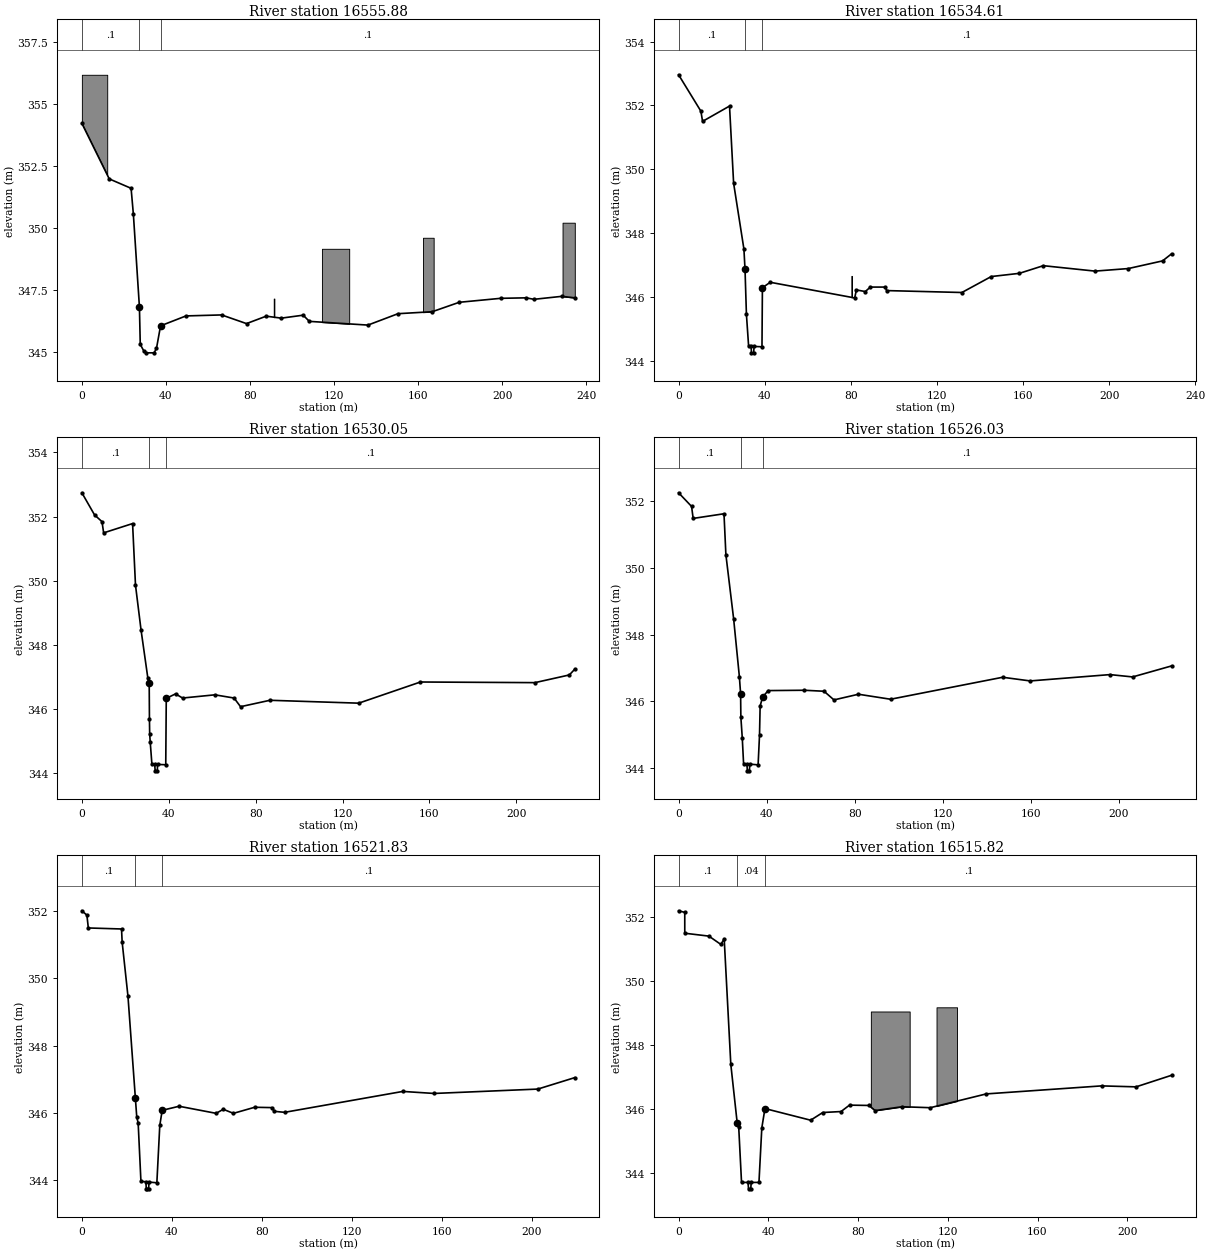
Type RM Length L Ch R = 1 ,16555.88,20.77,21.27,17.9
XS GIS Cut Line= 5
    -610504.2404   -1045706.1507    -610509.2146    -1045681.174
    -610509.4305   -1045668.0863-610521.60139999   -1045611.4654
    -610562.8314   -1045479.6849
#Sta/Elev= 27
       0  354.23   13.02  351.99   23.42  351.61   24.51  350.56   27.39  346.81
   27.78  345.31   29.57  345.03   30.58  344.97   34.36  344.97    35.5  345.15
   37.44  346.06   49.54  346.46    66.5   346.5   78.34  346.15   87.71  346.45
    94.9  346.37   105.3  346.49  108.23  346.24  136.11  346.09  150.44  346.55
  166.72  346.63  179.56  347.01  199.26  347.17  211.42  347.19  215.11  347.13
  228.36  347.25  234.55  347.19
#Mann= 3 , 0 , 0
       0      .1       0   27.39     .05       0   37.44      .1       0
#XS Ineff= 2 , 0
Permanent Ineff=
       F       F
#Block Obstruct= 5 ,-1
       0   12.06 356.192  114.23   127.2 349.169  162.31  167.39 349.614
  228.72  234.55 350.222   91.29    91.6  347.16
Bank Sta=27.39,37.44
XS Rating Curve= 0 ,0
Exp/Cntr=0.3,0.1

Type RM Length L Ch R = 1 ,16534.61,4.61,4.56,4.51
XS GIS Cut Line= 6
-610529.54529999   -1045705.4184    -610529.8783    -1045676.323
-610530.17399999   -1045665.9981-610534.91189999   -1045624.3717
-610542.27789999   -1045575.2226-610569.46539999   -1045481.1129
#Sta/Elev= 30
       0  352.96   10.36  351.82   11.14   351.5   23.66  351.98   25.57  349.56
   30.35   347.5   30.86  346.87   31.51  345.46   32.53  344.46   33.67  344.45
   33.87  344.25   34.87  344.25   35.07  344.45   38.74  344.44   38.94  346.29
   42.57  346.46   81.81  345.97    82.6  346.22   86.73  346.17   89.08  346.31
    96.1  346.31   96.62   346.2  131.61  346.14  145.25  346.64  158.29  346.74
  169.44  346.98  193.45  346.81   208.9  346.89  224.82  347.13  228.98  347.35
#Mann= 3 , 0 , 0
       0      .1       0   30.86     .04       0   38.94      .1       0
#XS Ineff= 2 , 0
Permanent Ineff=
       F       F
#Block Obstruct= 1 ,-1
   80.25   80.56  346.66
Bank Sta=30.86,38.94
XS Rating Curve= 0 ,0
Exp/Cntr=0.5,0.3

Type RM Length L Ch R = 1 ,16530.05,3.73,4.02,4.32
XS GIS Cut Line= 6
    -610534.1055   -1045705.0639-610534.43849999   -1045675.9685
    -610534.7342   -1045665.6436    -610539.4721   -1045624.0172
    -610546.8381   -1045574.8681    -610573.0214   -1045482.6369
#Sta/Elev= 30
       0  352.74    5.83  352.05    9.26  351.84   10.02  351.49   23.34  351.78
   24.68  349.86   27.24  348.46   30.35  346.97   30.99  346.81    31.1   345.7
   31.21  345.22   31.46  344.97   32.23  344.28   33.48  344.28   33.76  344.07
   34.69  344.07   34.89  344.27   38.61  344.26   38.85  346.33   43.12  346.47
   46.35  346.34   61.25  346.44   70.06  346.34   73.04  346.07   86.57  346.27
  127.43  346.18  155.85  346.84  208.55  346.82  224.39  347.06   226.9  347.24
#Mann= 3 , 0 , 0
       0      .1       0   30.99     .04       0   38.85      .1       0
#XS Ineff= 2 , 0
Permanent Ineff=
       F       F
Bank Sta=30.99,38.85
XS Rating Curve= 0 ,0
Exp/Cntr=0.5,0.3

Type RM Length L Ch R = 1 ,16526.03,4.58,4.2,3.62
XS GIS Cut Line= 5
    -610538.0693   -1045702.3362-610538.07229999    -1045677.112
    -610539.6568   -1045657.3569-610551.82759999   -1045576.9234
    -610578.2707   -1045483.1449
#Sta/Elev= 30
       0  352.26     5.9  351.85    6.62  351.49   20.62  351.63   21.48   350.4
   24.99  348.48    27.6  346.74   28.16  346.23   28.28  345.52   28.91  344.91
   29.51  344.13   31.02  344.12   31.22  343.92   32.08  343.91   32.44  344.11
   36.11  344.09   36.75  344.98   37.03  345.86    38.2  346.13   40.68  346.32
   57.07  346.33   66.05   346.3   70.55  346.04   81.67  346.21   96.26  346.06
  147.15  346.72  159.66  346.61   195.9   346.8  206.17  346.73  223.83  347.06
#Mann= 3 , 0 , 0
       0      .1       0   28.16     .04       0    38.2      .1       0
#XS Ineff= 2 , 0
Permanent Ineff=
       F       F
Bank Sta=28.16,38.2
XS Rating Curve= 0 ,0
Exp/Cntr=0.3,0.1

Type RM Length L Ch R = 1 ,16521.83,6.74,6.01,5.22
XS GIS Cut Line= 4
    -610542.1235   -1045699.3356    -610543.0548   -1045657.4255
    -610557.9562   -1045571.9967    -610579.7877   -1045484.1398
#Sta/Elev= 30
       0     352    2.23  351.87    2.87  351.49   17.63  351.46   17.91  351.07
    20.5  349.46   23.79  346.44    24.4  345.88   25.03   345.7   26.26  343.97
   28.45  343.96   28.64  343.76   28.85  343.75   29.66  343.75   29.86  343.95
   33.34  343.93   34.64  345.63   35.71  346.08   43.23   346.2    59.7  345.99
   62.86  346.11   67.39  345.99   76.82  346.17   84.53  346.16   85.58  346.05
   90.13  346.02   142.7  346.64  156.61  346.58  202.73  346.71  219.17  347.05
#Mann= 3 , 0 , 0
       0      .1       0   23.79     .04       0   35.71      .1       0
#XS Ineff= 2 , 0
Permanent Ineff=
       F       F
Bank Sta=23.79,35.71
XS Rating Curve= 0 ,0
Exp/Cntr=0.3,0.1

Type RM Length L Ch R = 1 ,16515.82,2.86,2.86,2.83
XS GIS Cut Line= 5
    -610549.2021   -1045701.0436    -610549.7798   -1045679.3474
    -610548.1328   -1045663.7179    -610550.4721   -1045643.0045
    -610581.5868   -1045484.5631
#Sta/Elev= 30
       0  352.19    2.75  352.14    2.76  351.49   13.52   351.4   18.86  351.14
   20.33  351.32   23.28   347.4   26.15  345.56   26.81  345.44   28.06  343.72
   30.97  343.72   31.17  343.52   32.17  343.52   32.37  343.72   35.83  343.72
    37.1  345.42   38.47  346.01   38.68  346.02   58.86  345.66   64.28   345.9
   72.41  345.93   76.19  346.13   84.83  346.12   87.61  345.96   99.59  346.08
  112.21  346.05  137.16  346.48  188.56  346.73  203.93   346.7  219.73  347.06
#Mann= 3 , 0 , 0
       0      .1       0   26.15     .04       0   38.68      .1       0
#XS Ineff= 2 , 0
Permanent Ineff=
       F       F
#Block Obstruct= 2 ,-1
  114.98  124.12349.1804   85.71  103.01  349.05
Bank Sta=26.15,38.68
XS Rating Curve= 0 ,0
Exp/Cntr=0.3,0.1

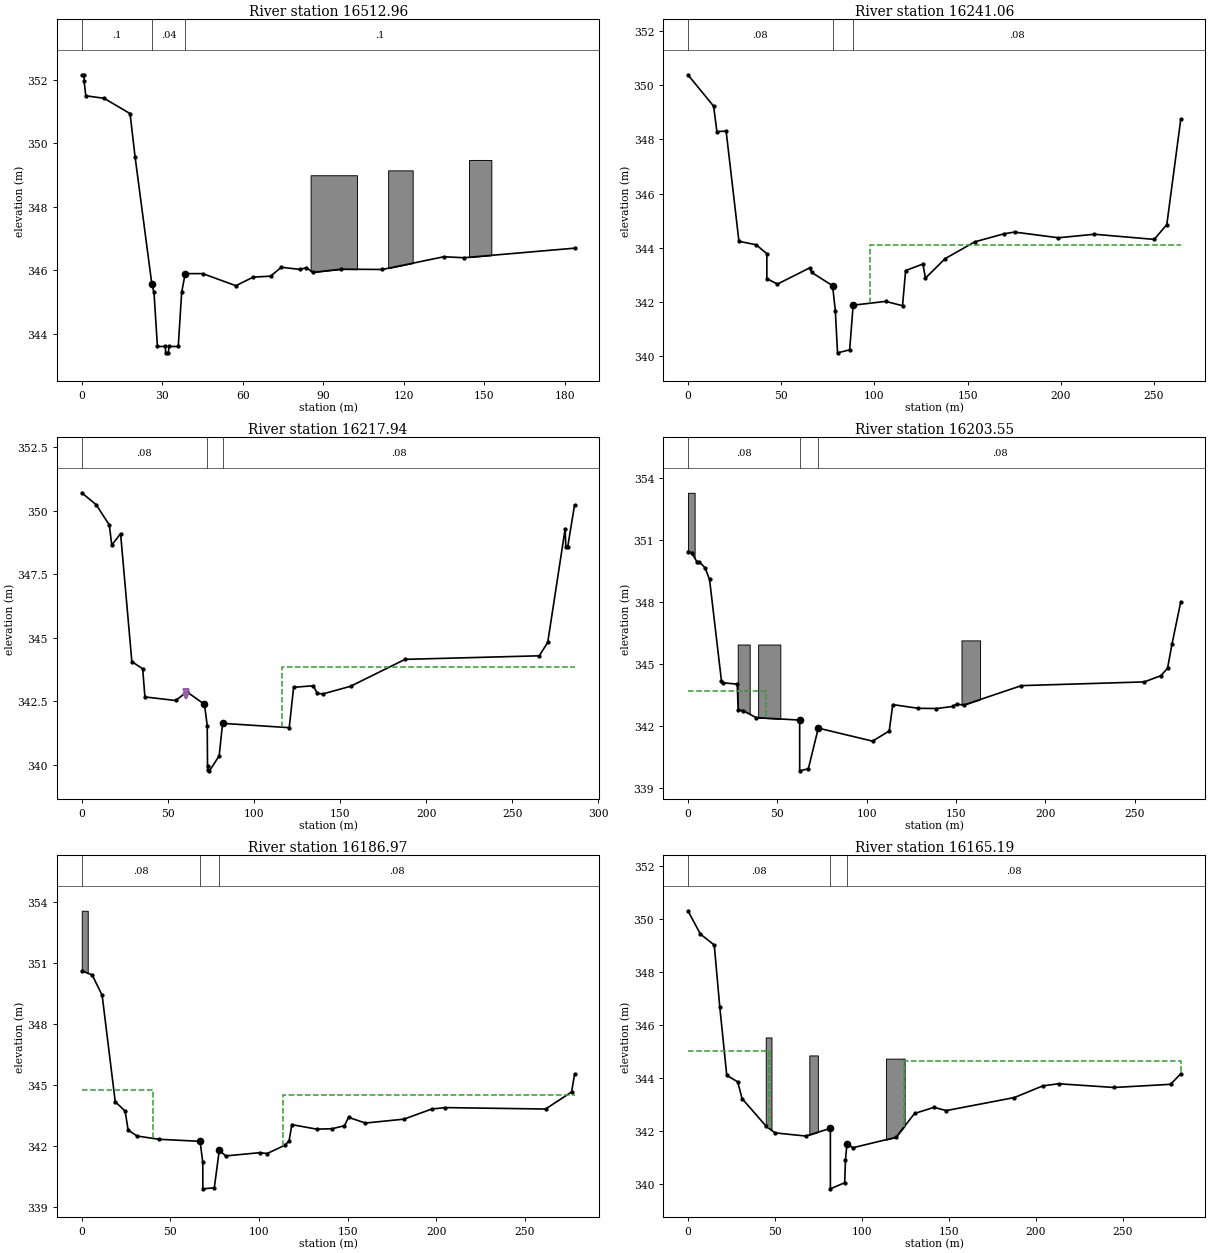
Type RM Length L Ch R = 1 ,16512.96,2.96,2.96,2.85
XS GIS Cut Line= 5
    -610552.0539   -1045700.8215    -610552.6316   -1045679.1253
    -610550.9846   -1045663.4958-610553.32389999   -1045642.7824
    -610576.8487   -1045519.6843
#Sta/Elev= 30
       0  352.15     .88  352.14     .89  351.94    1.51  351.49    8.34  351.41
      18  350.93   19.85  349.58   26.13  345.56   26.91  345.31   28.19  343.61
   31.08  343.61   31.28  343.41   32.28  343.41   32.48  343.61   35.95  343.61
   37.22  345.31   38.53   345.9   45.06   345.9   57.42  345.52   63.88  345.79
   70.34  345.82   74.35   346.1   81.44  346.03    83.7  346.09   85.98  345.94
   96.73  346.04  111.96  346.03  134.86  346.43   142.3   346.4  183.59   346.7
#Mann= 3 , 0 , 0
       0      .1       0   26.13     .04       0   38.53      .1       0
#Block Obstruct= 3 ,-1
  114.14  123.28349.1454   85.25  102.53348.9921  144.27  152.58349.4734
Bank Sta=26.13,38.53
XS Rating Curve= 0 ,0
Exp/Cntr=0.3,0.1

Type RM Length L Ch R = 1 ,16241.06,21.08,23.12,26.17
XS GIS Cut Line= 4
-610740.67799999   -1045794.9927    -610783.6451   -1045731.5412
-610794.63679999   -1045726.0454-610856.08969999   -1045561.6711
#Sta/Elev= 30
       0  350.39   13.77  349.23   15.54  348.29   20.49  348.31   27.36  344.24
   36.66  344.11   42.33  343.78   42.34  342.86   48.03  342.66   65.38  343.26
   66.37  343.09   77.59   342.6   79.07  341.68   80.26  340.12   86.76  340.23
   88.63  341.88  106.11  342.02  115.13  341.86  116.79  343.16  126.05   343.4
  127.44  342.88  138.01   343.6   153.9  344.22  169.78  344.52  175.28  344.58
  198.75  344.37  218.04   344.5  250.18  344.31  256.93  344.86  264.41  348.75
#Mann= 3 , 0 , 0
       0     .08       0   77.59     .04       0   88.63     .08       0
#XS Ineff= 2 , 0
                           97.69          344.12
Permanent Ineff=
       F       F
Bank Sta=77.59,88.63
XS Rating Curve= 0 ,0
Exp/Cntr=0.3,0.1

Type RM Length L Ch R = 1 ,16217.94,17.82,14.38,10.85
XS GIS Cut Line= 6
    -610749.3409   -1045804.8633    -610792.0326   -1045754.9198
    -610808.2784   -1045743.2547    -610827.6222   -1045711.1307
    -610872.3427   -1045570.3783    -610872.3427   -1045555.1515
#Sta/Elev= 30
       0  350.71    8.39  350.24   16.02  349.44   17.41  348.65   22.55   349.1
   29.09  344.06   35.38  343.78   36.67  342.67   54.49  342.53   61.05  342.87
   71.24  342.38   72.85  341.54   73.02  339.95    73.1  339.81   74.14  339.76
   79.78  340.35   81.77  341.63  120.46  341.46     123  343.05  134.37  343.11
  136.79  342.81  140.02  342.79  156.08  343.09  187.68  344.15  265.62  344.29
  270.54  344.82  280.67   349.3  281.02  348.59  282.12  348.58  286.12  350.23
#Mann= 3 ,-1 , 0
       0     .08       0   72.44     .04       0   81.72     .08       0
Levee=-1,60.62,342.72,0,,,,
#XS Ineff= 2 , 0
                           116.4          343.83
Permanent Ineff=
       F       F
Bank Sta=71.24,81.77
XS Rating Curve= 0 ,0
Exp/Cntr=0.3,0.1

Type RM Length L Ch R = 1 ,16203.55,16.98,16.59,13.12
XS GIS Cut Line= 5
    -610769.6559   -1045808.4823    -610808.1264   -1045763.0171
    -610815.1211   -1045751.5259    -610847.5962   -1045700.0653
    -610890.0638   -1045564.6689
#Sta/Elev= 30
       0  350.46    2.07   350.4    4.97  349.97    6.36  349.96    9.56  349.67
   12.09  349.11   18.75  344.19   19.58   344.1   27.59  344.03    28.1  342.77
   30.81  342.75   38.12  342.41   62.52  342.29   62.53  339.83   67.37  339.93
   72.94   341.9  103.27  341.27  112.63  341.76  114.61  343.04  128.88  342.86
  139.06  342.85  148.15  342.95  150.27  343.06  154.36  343.02  186.61  343.96
  255.33  344.14  264.57  344.44  268.36   344.8  270.82  345.96  275.76  348.03
#Mann= 3 , 0 , 0
       0     .08       0   62.52     .04       0   72.94     .08       0
#XS Ineff= 2 , 0
           43.65   343.7
Permanent Ineff=
       F       F
#Block Obstruct= 4 ,-1
  153.07  163.46346.1526       0    3.74353.3066   27.86   34.56 345.952
   39.28   51.69 345.952
Bank Sta=62.52,72.94
XS Rating Curve= 0 ,0
Exp/Cntr=0.3,0.1

Type RM Length L Ch R = 1 ,16186.97,23.06,21.77,16.29
XS GIS Cut Line= 5
    -610779.6482   -1045816.9759    -610825.1134   -1045768.5129
    -610828.6108   -1045757.0217-610860.08659999   -1045702.5634
    -610908.5496   -1045574.6612
#Sta/Elev= 30
       0  350.62    5.89  350.41   11.51  349.41    18.9  344.17   24.48  343.71
   26.19  342.77   31.27  342.48   43.49  342.32   66.78  342.22   68.32  341.18
   68.33  339.88   74.81  339.93   77.62  341.78   81.26   341.5  100.37  341.66
  104.66  341.62   114.7  342.03     117  342.24  118.59  343.04   132.6  342.82
  141.36  342.84  148.28  342.99  150.56   343.4  160.08  343.12  181.77  343.31
  197.52  343.81  205.12  343.88  261.78  343.81  276.45  344.65  278.14  345.52
#Mann= 3 , 0 , 0
       0     .08       0   66.78     .04       0   77.62     .08       0
#XS Ineff= 2 , 0
           40.01  344.75  113.45          344.49
Permanent Ineff=
       F       F
#Block Obstruct= 1 ,-1
       0    3.38 353.571
Bank Sta=66.78,77.62
XS Rating Curve= 0 ,0
Exp/Cntr=0.3,0.1

Type RM Length L Ch R = 1 ,16165.19,23.88,24.21,22.28
XS GIS Cut Line= 4
    -610790.1402   -1045840.9575-610846.59699999    -1045775.008
    -610849.0951   -1045761.5183-610919.04149999   -1045584.6535
#Sta/Elev= 27
       0   350.3    7.18  349.42   15.14  349.01   18.29  346.69   22.32   344.1
   28.64  343.85   31.14  343.22   44.85  342.19   50.01  341.93   67.73  341.81
   81.92   342.1   81.93  339.82   90.15  340.05   90.61  340.92   91.47  341.52
   91.57  341.52   94.87  341.37  119.58  341.76  130.35  342.66  141.45  342.89
  148.64  342.77  187.72  343.26  204.08   343.7  213.17  343.78  245.14  343.64
  277.62  343.76  283.46  344.16
#Mann= 3 , 0 , 0
       0     .08       0   81.92     .04       0   91.57     .08       0
#XS Ineff= 2 , 0
           46.42  345.02  124.19          344.62
Permanent Ineff=
       F       F
#Block Obstruct= 3 ,-1
   44.75   48.05345.5259   69.81   74.72344.8481  113.88  124.65344.7277
Bank Sta=81.92,91.57
XS Rating Curve= 0 ,0
Exp/Cntr=0.3,0.1

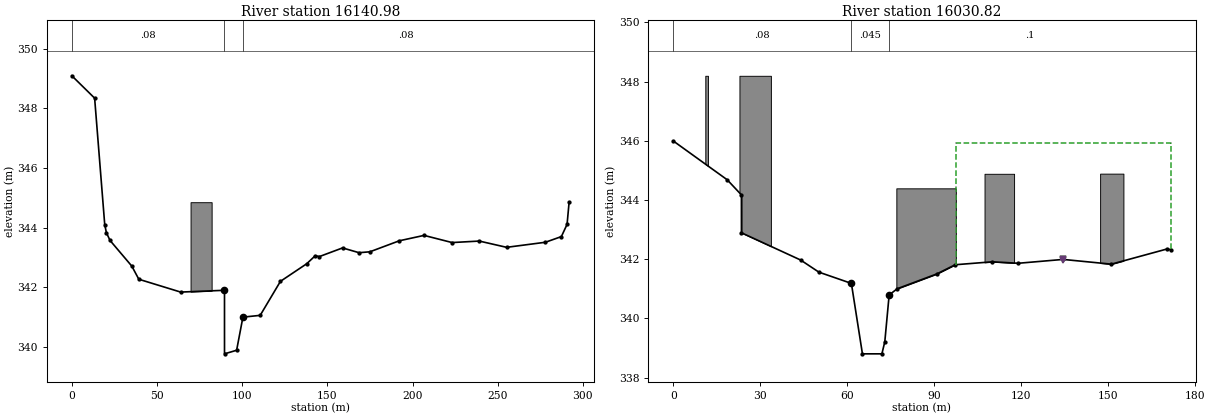
Type RM Length L Ch R = 1 ,16140.98,20.09,21.91,20.25
XS GIS Cut Line= 4
    -610811.1241   -1045849.9506    -610870.5786   -1045779.5045
-610873.07669999   -1045762.0179    -610940.0255   -1045585.6527
#Sta/Elev= 29
       0  349.09   13.38  348.34   19.31   344.1   20.29  343.83   22.43  343.57
   35.21  342.71   39.32  342.27   63.88  341.84   89.62   341.9   89.63  339.77
   96.74  339.89  100.43     341  110.58  341.06  122.46   342.2   137.9  342.79
  142.93  343.06  145.31  343.03  158.93  343.32  168.61  343.16  174.96  343.19
  192.29  343.56  206.78  343.74  223.24   343.5   239.2  343.55  255.24  343.34
  278.02  343.51   287.4   343.7  290.74  344.11  291.95  344.86
#Mann= 3 , 0 , 0
       0     .08       0   89.62     .04       0  100.43     .08       0
#XS Ineff= 2 , 0
Permanent Ineff=
       F       F
#Block Obstruct= 1 ,-1
   69.69   82.07344.8526
Bank Sta=89.62,100.43
XS Rating Curve= 0 ,0
Exp/Cntr=0.3,0.1

Type RM Length L Ch R = 1 ,16030.82,23.32,23.08,22.14
XS GIS Cut Line= 4
-610933.67859999    -1045873.336    -610963.0078   -1045822.4717
-610974.99879999   -1045806.4839-611012.67509999   -1045721.6095
#Sta/Elev= 20
       0  345.99   18.59  344.68   23.48  344.17   23.49  342.89    43.9  341.97
   50.21  341.56   61.42  341.18   65.23   338.8   71.95   338.8   72.95  339.21
   74.45  340.79   77.25     341    90.9   341.5   97.22  341.81  110.09  341.91
  118.98  341.86  134.47  341.99  151.11  341.83  170.21  342.34  171.56  342.32
#Mann= 3 , 0 , 0
       0     .08       0   61.42    .045       0   74.45      .1       0
Levee=0,,,-1,134.53,341.98,,
#XS Ineff= 2 , 0
                           97.48          345.91
Permanent Ineff=
       F       F
#Block Obstruct= 5 ,-1
   11.02   11.93348.1946    22.8   33.65348.1946   76.93   97.46 344.392
  107.35  117.55344.8834  147.23  155.27344.8887
Bank Sta=61.42,74.45
XS Rating Curve= 0 ,0
Exp/Cntr=0.3,0.1