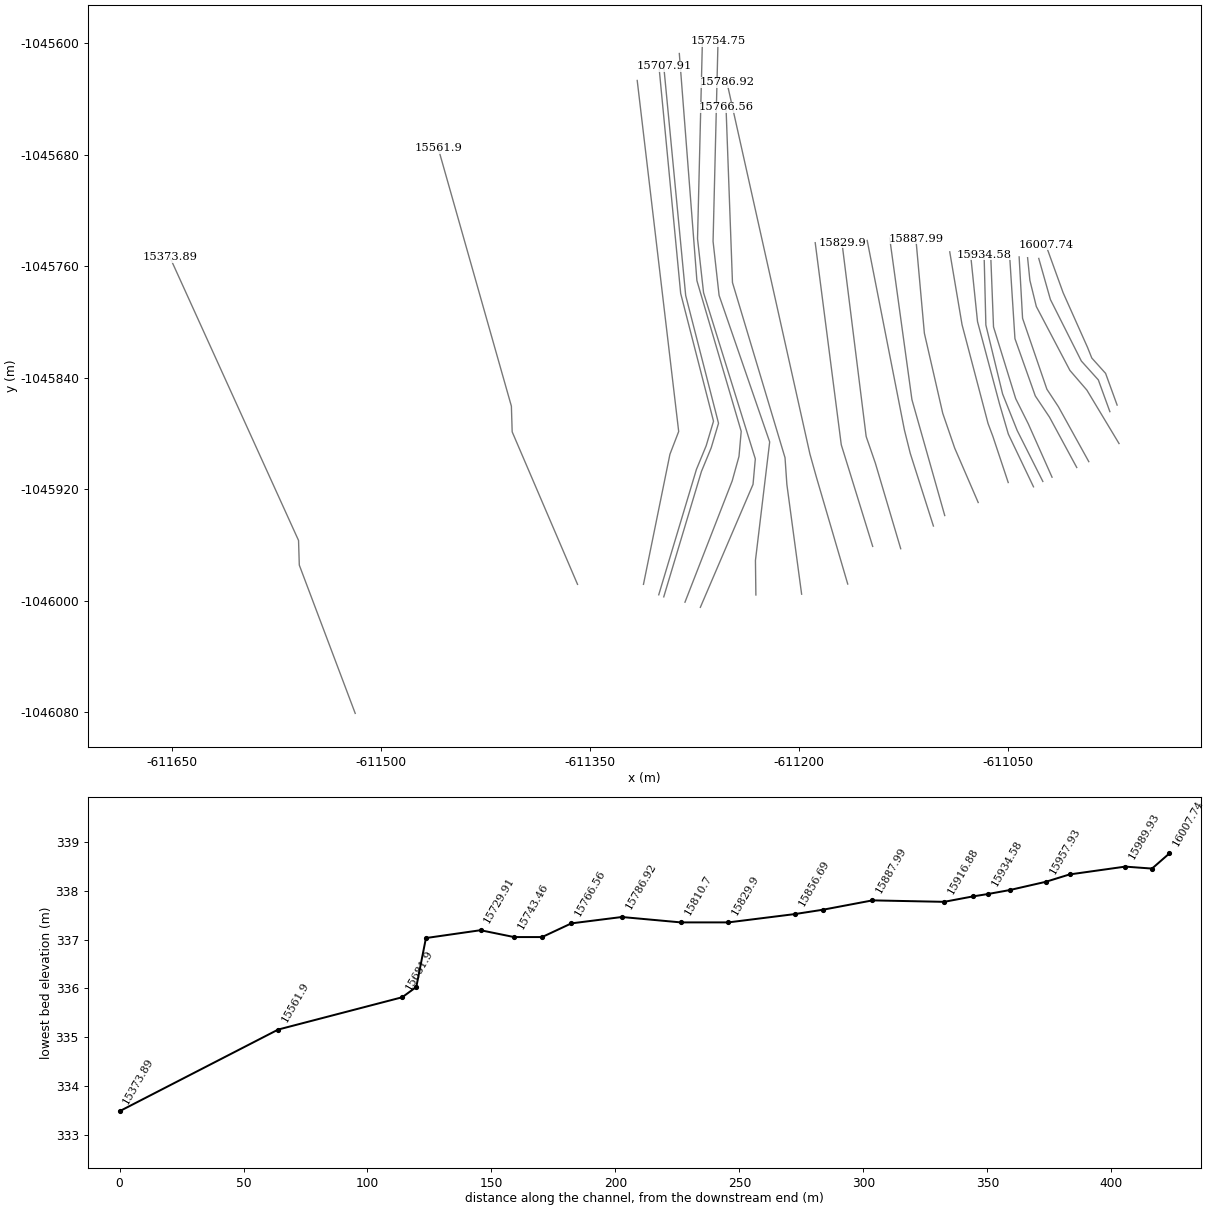
HEC-RAS study PPO_Kvasiny_efektiv.prj: PPO_Kvasiny_efektivita

--- PPO_Kvasiny_efektiv.g12 (geometry) --- (continued)

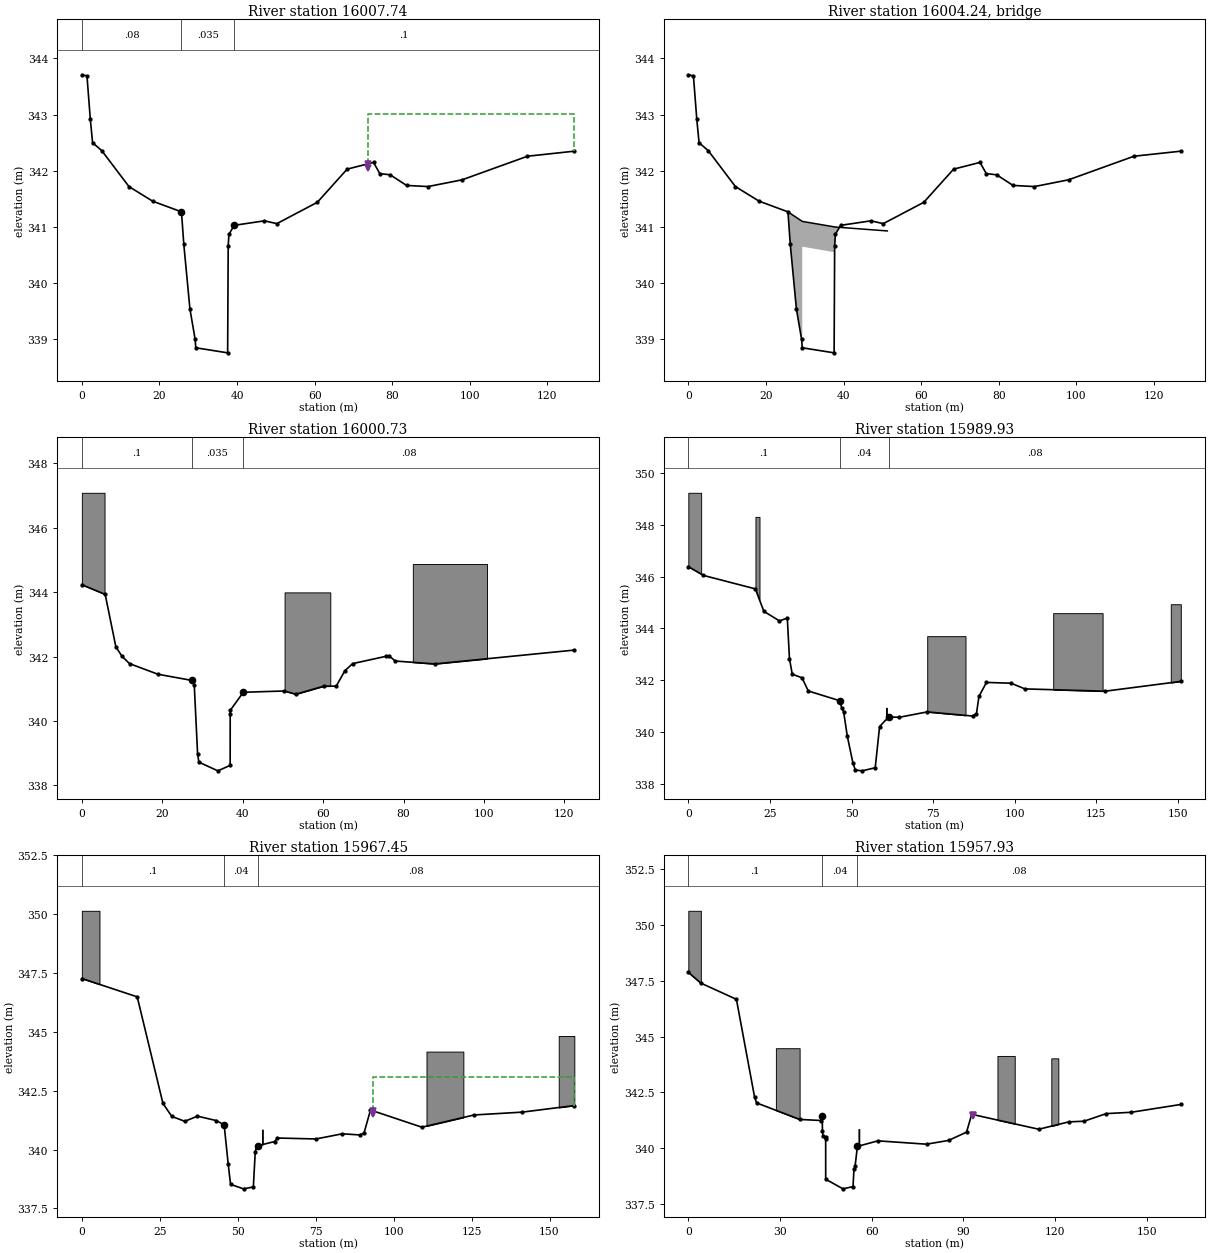
Type RM Length L Ch R = 1 ,16007.74,6.71,7.01,8.54
XS GIS Cut Line= 6
-610971.77129999   -1045859.4797    -610980.0408   -1045836.7296
    -610989.9356   -1045825.7279    -610992.9954   -1045818.0942
-611010.51089999   -1045778.8608    -611023.0044   -1045744.3002
#Sta/Elev= 28
       0  343.71    1.32  343.69    2.18  342.92    2.77   342.5    5.13  342.36
   12.14  341.72   18.24  341.46   25.68  341.27   26.28  340.69   27.86  339.54
    29.2     339   29.37  338.85   37.58  338.76   37.72  340.66   37.91  340.87
   39.28  341.03   47.07  341.11   50.26  341.06    60.7  341.44   68.38  342.03
   75.18  342.15   76.81  341.95   79.46  341.93   83.71  341.74   89.23  341.72
   98.01  341.84  114.86  342.26  126.94  342.35
#Mann= 3 , 0 , 0
       0     .08       0   25.68    .035       0   39.28      .1       0
Levee=0,,,-1,73.72,342.05,,
#XS Ineff= 2 , 0
                            73.8          343.01
Permanent Ineff=
       F       F
Bank Sta=25.68,39.28
XS Rating Curve= 0 ,0
Exp/Cntr=0.5,0.3

Type RM Length L Ch R = 3 ,16004.24,,,
BEGIN DESCRIPTION:
16199.9  PF 206 SILNIÈNÍ ŽLB MOSTEK V
END DESCRIPTION:
Bridge Culvert--1,0,-1,-1, 0
Deck Dist Width WeirC Skew NumUp NumDn MinLoCord MaxHiCord MaxSubmerge Is_Ogee
0.5,6,1.4,0, 5, 5, , , 0.98, 0, 0,0,,
   25.68   29.37   37.83   37.83    51.3
  341.27   341.1     341     341  340.93
          340.65  340.55
   24.73   28.42   36.88   36.88   50.35
  341.27   341.1     341     341  340.93
          340.65  340.55
BR Coef=-1 , 0 , 0 ,, 0 ,,,0.8,0,,0,
WSPro=,,,, 1 ,,,, 0 ,,,, 0 ,,,,-1 ,-1 ,-1 , 0 , 0 , 0 , 0 , 0
BC Design=,, 0 ,, 0 ,,,,,,
BC Use User HTab Curves=0
BC User HTab FreeFlow(D)= 0

Type RM Length L Ch R = 1 ,16000.73,9.83,10.81,10.61
XS GIS Cut Line= 5
     -610976.975   -1045864.1751    -610985.2445    -1045841.425
    -610997.4496   -1045827.8546-611019.62709999   -1045783.7506
    -611027.9807   -1045754.2729
#Sta/Elev= 26
       0  344.23     5.8  343.93    8.46   342.3    9.96  342.01   11.85  341.78
   18.91  341.45   27.28  341.26   27.95  341.12   28.78  338.98    29.1  338.72
   33.82  338.45   36.88  338.62   36.89   340.2   36.91  340.33   40.15  340.89
   50.35  340.93   53.21  340.83   60.15  341.08   63.25  341.08   65.41  341.56
   67.34  341.78   75.75  342.01   76.44  342.02   77.92  341.86   87.77  341.77
  122.46   342.2
#Mann= 3 , 0 , 0
       0      .1       0   27.28    .035       0   40.15     .08       0
#Block Obstruct= 4 ,-1
       0    5.64 347.085    82.3  100.74 344.872   50.41   61.78 343.992
   40.08   40.38  340.95
Bank Sta=27.28,40.15
XS Rating Curve= 0 ,0
Exp/Cntr=0.5,0.3

Type RM Length L Ch R = 1 ,15989.93,23.84,22.47,19.81
XS GIS Cut Line= 6
    -610970.3973   -1045887.0677    -610993.4662   -1045848.7396
    -611005.6395   -1045834.6026    -611029.7291    -1045788.774
    -611034.3488   -1045770.0031    -611035.9998    -1045753.747
#Sta/Elev= 30
       0  346.39    4.63  346.05   20.52  345.53   23.14  344.66   27.92  344.29
   30.32   344.4   30.98  342.83   31.83  342.23   34.82  342.09   36.74  341.58
   46.45   341.2   46.96  340.92   47.56  340.78   48.68  339.84   50.39  338.81
   51.14  338.52   53.27  338.49   57.25  338.61   58.58   340.2   61.37  340.58
   64.54  340.56   73.16  340.77   87.05  340.61   88.25   340.7   89.02  341.37
   91.32  341.91   98.87  341.88  103.09  341.66   127.6  341.57  150.84  341.95
#Mann= 3 , 0 , 0
       0      .1       0   46.45     .04       0   61.37     .08       0
#XS Ineff= 2 , 0
Permanent Ineff=
       F       F
#Block Obstruct= 6 ,-1
   20.56    21.8 348.315  111.76  126.89  344.59   73.17    84.9   343.7
       0    3.93 349.247  147.77  150.84 344.935   60.53   60.83  340.93
Bank Sta=46.45,61.37
XS Rating Curve= 0 ,0
Exp/Cntr=0.3,0.1

Type RM Length L Ch R = 1 ,15967.45,9.35,9.53,9.59
XS GIS Cut Line= 5
-610992.09319999   -1045900.0587    -611013.8884   -1045860.6581
-611022.15659999   -1045848.0903-611039.60269999   -1045797.2262
-611042.06069999   -1045753.1775
#Sta/Elev= 26
       0  347.27   17.76  346.49   26.01  341.96   28.84  341.41   33.02   341.2
   37.08  341.42   43.15  341.23   45.64  341.05   46.95  339.37    47.7  338.52
   51.85  338.33   55.01  338.41   55.61  339.89   56.02  340.12   56.35  340.16
   61.82  340.34   62.73  340.49    75.1  340.45   83.56  340.67   89.14  340.62
    90.5   340.7   92.58  341.68  109.06  340.95   125.8  341.47  141.22  341.59
  157.96  341.87
#Mann= 3 , 0 , 0
       0      .1       0   45.64     .04       0   56.35     .08       0
Levee=0,,,-1,93.3,341.5,,
#XS Ineff= 2 , 0
                           93.39          343.08
Permanent Ineff=
       F       F
#Block Obstruct= 4 ,-1
  110.54  122.37 344.164       0    5.65 350.149  152.96  157.96 344.828
   57.76   58.06  340.85
Bank Sta=45.64,56.35
XS Rating Curve= 0 ,0
Exp/Cntr=0.3,0.1

Type RM Length L Ch R = 1 ,15957.93,15.71,14.65,13.63
XS GIS Cut Line= 5
     -611000.734   -1045904.2531    -611020.2591   -1045868.1678
-611030.47859999   -1045852.8987-611045.06769999   -1045811.8192
-611048.78449999   -1045753.7894
#Sta/Elev= 30
       0  347.88    4.05   347.4   15.74  346.67   21.67   342.3   22.34  342.03
   36.42  341.29    43.5  341.24   43.53  341.44   43.83  341.45   43.88  340.76
   44.08  340.53   44.92  340.42   44.94  340.49   44.95  338.61   50.61  338.18
   53.89  338.28    54.2  339.05   54.58   339.2   55.32  340.08   62.03  340.33
   77.96  340.18   85.16  340.35   91.04  340.72   92.73  341.52  114.67  340.85
  124.49  341.18  129.49  341.21  136.74  341.55   144.9  341.61  161.14  341.96
#Mann= 3 , 0 , 0
       0      .1       0   43.83     .04       0   55.32     .08       0
Levee=0,,,-1,93.22,341.45,,
#XS Ineff= 2 , 0
Permanent Ineff=
       F       F
#Block Obstruct= 5 ,-1
  118.77  121.07 344.026  101.15   106.8 344.134       0    4.09 350.637
   28.65   36.42  344.48   55.65   55.95  340.86
Bank Sta=43.83,55.32
XS Rating Curve= 0 ,0
Exp/Cntr=0.3,0.1

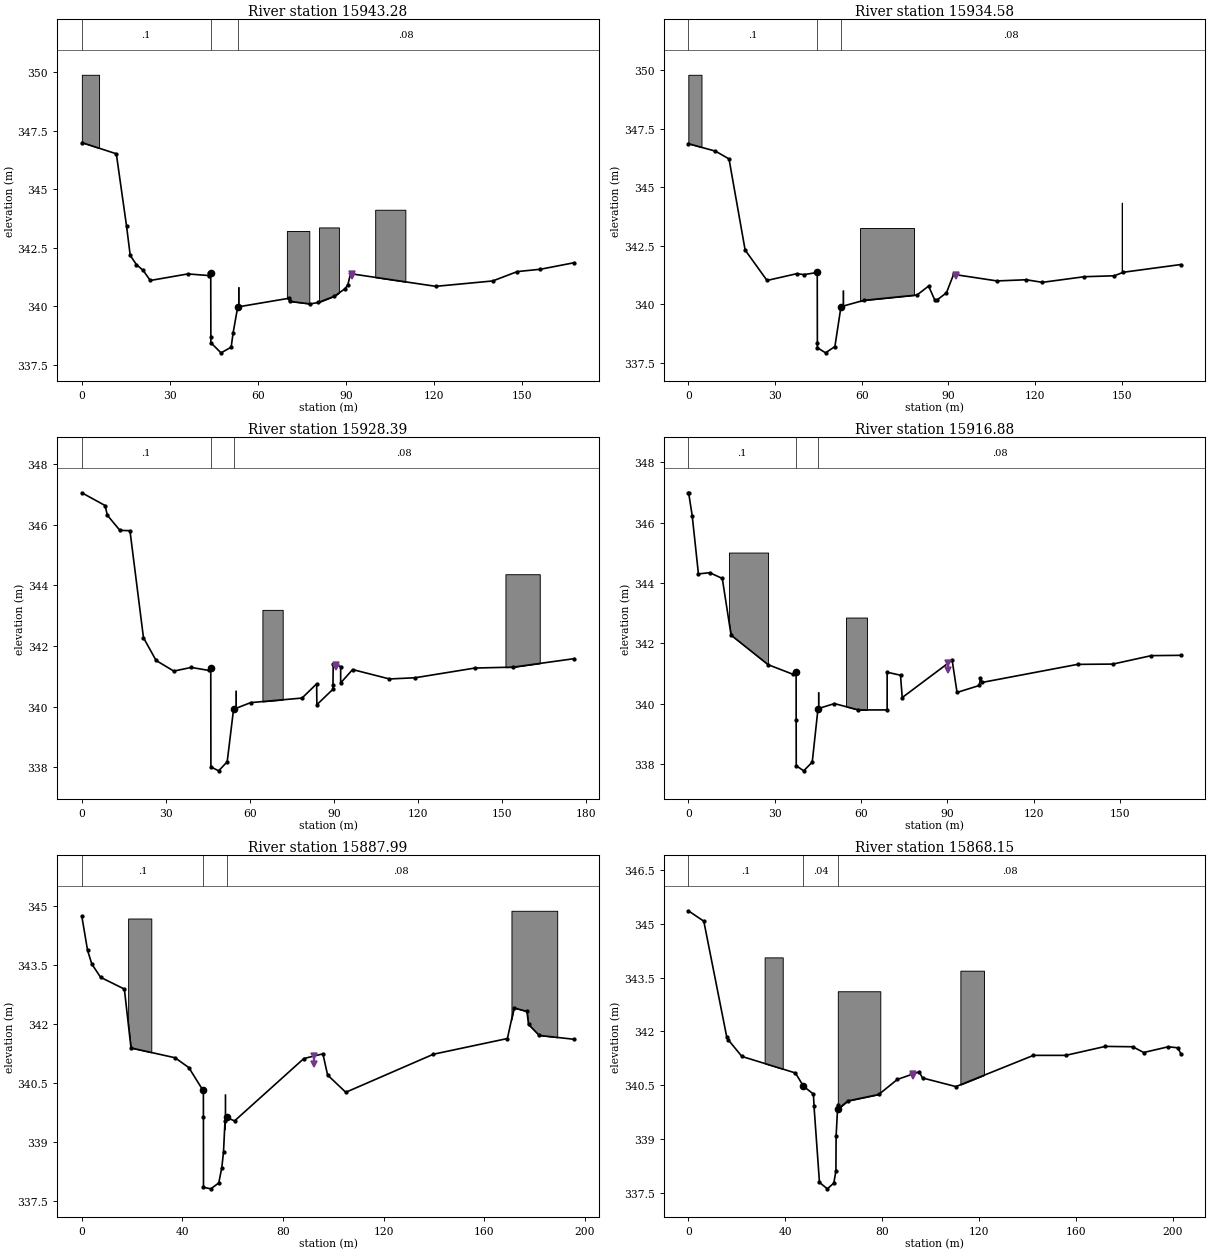
Type RM Length L Ch R = 1 ,15943.28,9.23,8.7,8.01
XS GIS Cut Line= 5
-611018.45259999   -1045911.2168    -611035.5181   -1045872.8951
-611044.51399999   -1045854.9034-611060.44139999   -1045803.4049
-611062.47329999   -1045751.5215
#Sta/Elev= 30
       0  346.99   11.75  346.51   15.23  343.43   16.49  342.17    18.6  341.78
   20.91  341.53   23.32   341.1   36.13  341.38   43.42  341.31   43.45  341.42
   43.94  341.41   43.98  338.67   43.99  338.44   47.44  338.01    50.9  338.25
   51.56  338.86   53.14  339.97    70.6  340.34   70.79  340.21   77.82   340.1
   80.64  340.16   86.13  340.43   89.75  340.75   90.69  340.92   91.59  341.39
  120.67  340.85  140.07  341.08  148.45  341.48  156.33  341.58  167.89  341.86
#Mann= 3 , 0 , 0
       0      .1       0   43.94     .04       0   53.14     .08       0
Levee=0,,,-1,92.18,341.28,,
#XS Ineff= 2 , 0
Permanent Ineff=
       F       F
#Block Obstruct= 5 ,-1
   80.86   87.63 343.366     100  110.29 344.121    69.9   77.54 343.214
       0    5.87 349.885   53.22   53.52  340.82
Bank Sta=43.94,53.14
XS Rating Curve= 0 ,0
Exp/Cntr=0.3,0.1

Type RM Length L Ch R = 1 ,15934.58,6.66,6.18,4
XS GIS Cut Line= 5
    -611025.0566   -1045914.2648    -611043.4717   -1045877.6887
-611053.92689999   -1045851.5159    -611065.9296   -1045802.0495
    -611067.1996   -1045751.6727
#Sta/Elev= 27
       0  346.86    9.39  346.54   14.08  346.21   19.66  342.32   27.23  341.02
   37.57  341.31   39.99  341.27   44.62  341.36   44.66  338.33   44.67  338.15
   47.49  337.93   50.73   338.2   52.83   339.9   60.69  340.17   79.16   340.4
   83.15  340.78   85.27  340.19   85.89  340.17   89.32  340.49    91.8  341.28
  106.84     341  116.94  341.05  122.53  340.94  137.05  341.18  147.45  341.22
  150.52  341.37  170.43   341.7
#Mann= 3 , 0 , 0
       0      .1       0   44.62     .04       0   52.83     .08       0
Levee=0,,,-1,92.49,341.2,,
#Block Obstruct= 4 ,-1
   59.43   78.12 343.258  149.97  150.06 344.342       0    4.56 349.801
   53.34   53.64   340.6
Bank Sta=44.62,52.83
XS Rating Curve= 0 ,0
Exp/Cntr=0.3,0.1

Type RM Length L Ch R = 1 ,15928.39,11.22,11.51,11.57
XS GIS Cut Line= 5
    -611031.7622   -1045918.1087-611049.80559999   -1045880.3034
-611056.15569999   -1045858.6076    -611071.9197   -1045799.5853
    -611077.0852   -1045749.5899
#Sta/Elev= 30
       0  347.05    8.29  346.63     9.1  346.31   13.59  345.81   17.18   345.8
      22  342.27   26.51  341.52   32.82  341.17   39.07  341.29   45.43  341.19
   46.03  341.27   46.08  338.01   48.85  337.88    51.9  338.18   54.17  339.91
   60.29  340.13   78.62  340.28   83.85  340.75   83.91  340.06   89.64  340.57
   89.67  340.72   89.75   341.4   92.41  341.32   92.42  340.78   96.68  341.22
  109.85  340.91  119.02  340.95  140.36  341.27     154   341.3  175.85  341.58
#Mann= 3 , 0 , 0
       0      .1       0   46.03     .04       0   54.17     .08       0
Levee=0,,,-1,90.76,341.32,,
#Block Obstruct= 3 ,-1
   64.47   71.72 343.188  151.25  163.51 344.364   54.76   55.06  340.53
Bank Sta=46.03,54.17
XS Rating Curve= 0 ,0
Exp/Cntr=0.3,0.1

Type RM Length L Ch R = 1 ,15916.88,28.68,28.89,29.62
XS GIS Cut Line= 5
    -611049.8937   -1045915.0428    -611060.9182    -1045881.891
    -611064.3608   -1045872.7106    -611083.0196   -1045801.8009
-611091.84849999   -1045749.5303
#Sta/Elev= 30
       0  346.99     .14  346.97    1.35  346.23    3.51   344.3    7.42  344.34
    11.8  344.15   14.85  342.27   27.72  341.29    36.4  340.97   37.45  341.06
   37.46  339.45   37.49  337.94   40.08  337.77   43.05  338.06   45.05  339.83
   50.76     340   59.07  339.79   69.07  339.79   69.08  341.04   73.71  340.94
   74.31   340.2   91.65  341.44   93.35  340.37  101.08   340.6   101.5  340.85
  101.99   340.7   135.2   341.3  147.48  341.31  160.85  341.59  171.08   341.6
#Mann= 3 , 0 , 0
       0      .1       0   37.45     .04       0   45.05     .08       0
Levee=0,,,-1,90.21,341.11,,
#XS Ineff= 2 , 0
Permanent Ineff=
       F       F
#Block Obstruct= 3 ,-1
   54.77   62.06 342.853   14.11    27.7 345.008   44.99   45.29  340.38
Bank Sta=37.45,45.05
XS Rating Curve= 0 ,0
Exp/Cntr=0.3,0.1

Type RM Length L Ch R = 1 ,15887.99,19.91,19.84,18.61
XS GIS Cut Line= 5
-611071.43079999   -1045929.3784-611088.29679999   -1045890.3326
    -611096.8689   -1045865.3553-611110.03889999   -1045807.9662
    -611116.1349   -1045740.2327
#Sta/Elev= 30
       0  344.74    2.26  343.88    3.95  343.53    7.45  343.19   16.91  342.89
   19.54  341.39   37.06  341.14   42.53  340.89   48.17  340.31   48.32   340.3
   48.34  339.64   48.37  337.84   51.28   337.8   54.44  337.95   55.65  338.34
   56.33  338.74   56.93  339.54   57.62  339.62   60.71  339.53   88.27  341.12
   95.85  341.24   97.72   340.7  104.95  340.26   139.8  341.23  169.22  341.63
  171.87  342.41     177  342.32  177.61  341.99  181.85  341.71  195.83  341.61
#Mann= 3 , 0 , 0
       0      .1       0   48.17     .04       0   57.62     .08       0
Levee=0,,,-1,92.49,340.98,,
#Block Obstruct= 3 ,-1
   18.39   27.61 344.688  170.83  189.02 344.885   56.76   57.06  340.21
Bank Sta=48.17,57.62
XS Rating Curve= 0 ,0
Exp/Cntr=0.3,0.1

Type RM Length L Ch R = 1 ,15868.15,11.59,11.46,10.73
XS GIS Cut Line= 3
    -611095.4338     -1045938.72    -611118.9712   -1045855.5772
    -611134.9309   -1045739.7811
#Sta/Elev= 30
       0  345.36    6.39  345.07    15.9  341.83   16.52  341.76   22.12   341.3
   44.21  340.84   47.53  340.47   51.66  340.25   51.88  339.92   54.14  337.79
   57.39  337.61   60.06  337.77   60.93  338.11   61.01  339.08   61.71  339.96
   61.91  339.84   65.86  340.06   78.61  340.24   86.31  340.66   95.28  340.87
   96.69   340.7  110.47  340.46  142.47  341.33  155.79  341.33  172.16  341.58
  183.48  341.57  187.98  341.41  198.16  341.57  202.07  341.54   203.3  341.38
#Mann= 3 , 0 , 0
       0      .1       0   47.53     .04       0   61.91     .08       0
Levee=0,,,-1,92.67,340.75,,
#Block Obstruct= 3 ,-1
  112.31  122.04343.6905    31.5   38.97344.0612   61.71   79.25343.1169
Bank Sta=47.53,61.91
XS Rating Curve= 0 ,0
Exp/Cntr=0.3,0.1

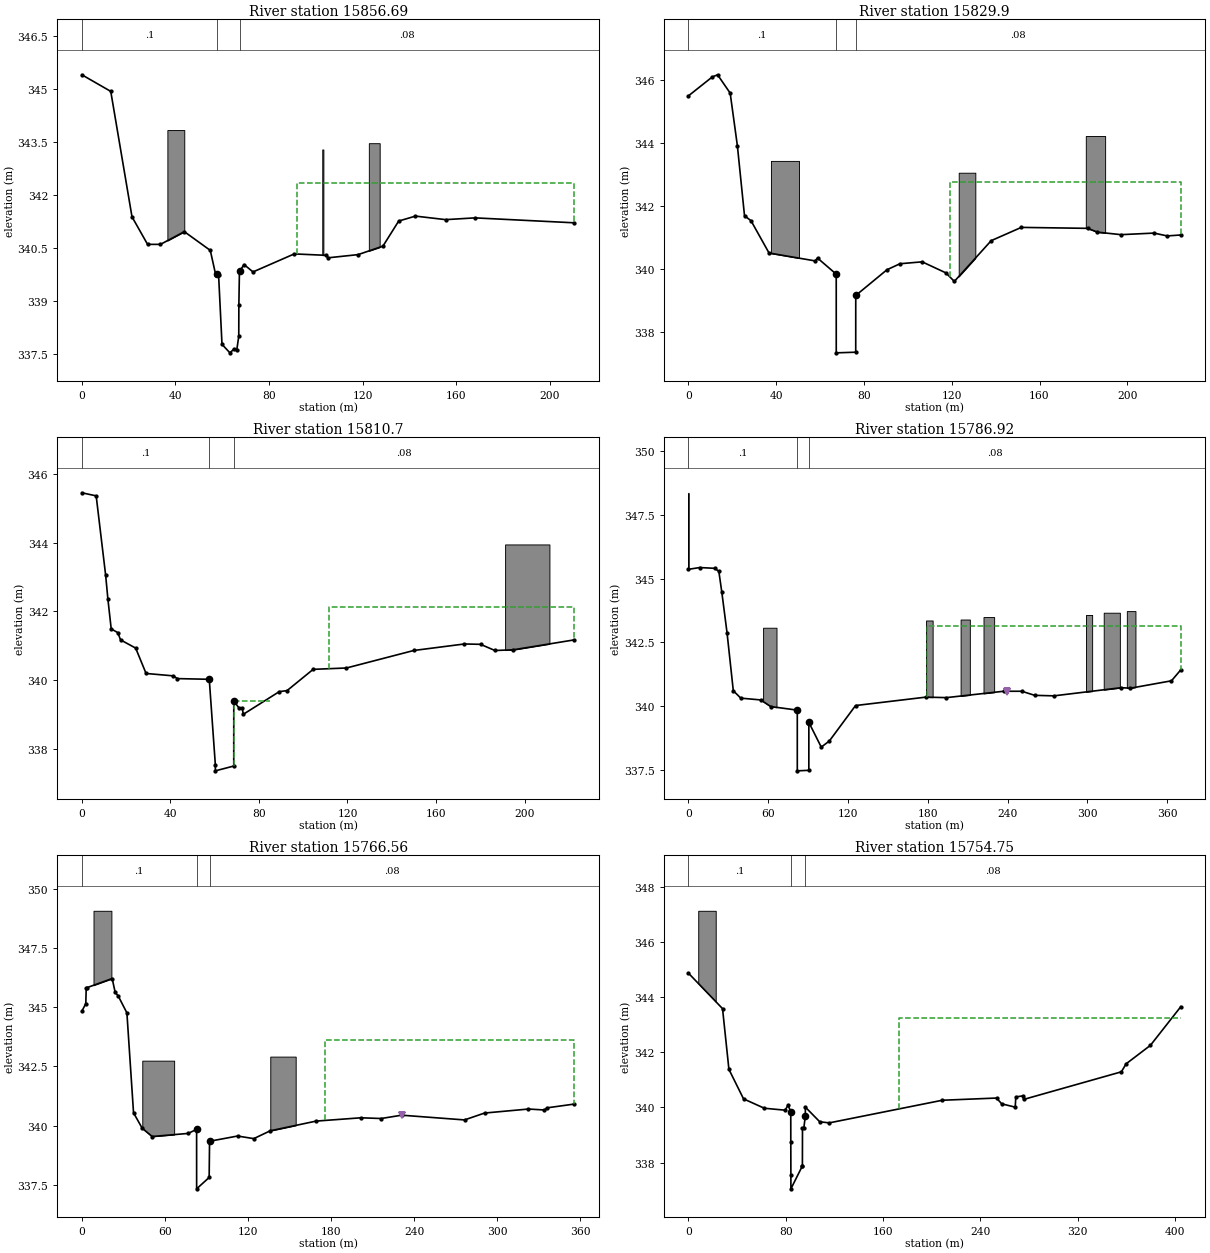
Type RM Length L Ch R = 1 ,15856.69,26.05,26.8,27.68
XS GIS Cut Line= 4
    -611103.5637   -1045946.2449-611120.18499999   -1045894.0618
    -611124.3476   -1045877.4141     -611151.067   -1045741.3785
#Sta/Elev= 30
       0  345.39   12.36  344.92   21.44  341.37    28.1  340.59   33.62  340.59
   43.81  340.95   54.91  340.42   57.26  339.72   57.88  339.75   58.46  339.73
   59.92  337.76   63.31  337.52   64.92  337.62   66.21  337.59   67.09  337.99
   67.13  338.88   67.38  339.83   67.49  339.83   69.33  340.02   73.18  339.81
   90.82  340.32  104.41  340.28   105.3  340.21  118.11   340.3  128.73  340.54
  135.47  341.25  142.63  341.39  155.53  341.29  168.07  341.34  210.56   341.2
#Mann= 3 , 0 , 0
       0      .1       0   57.88    .035       0   67.49     .08       0
#XS Ineff= 2 , 0
                           92.09          342.32
Permanent Ineff=
       F       F
#Block Obstruct= 3 ,-1
   122.7  127.34343.4536  102.78  103.27 343.276   36.57   43.79343.8254
Bank Sta=57.88,67.49
XS Rating Curve= 0 ,0
Exp/Cntr=0.3,0.1

Type RM Length L Ch R = 1 ,15829.9 ,19.46,19.19,18.61
XS GIS Cut Line= 4
-611127.02369999   -1045962.5109-611145.18809999   -1045901.2055
    -611151.8026   -1045882.0232    -611169.1645    -1045742.966
#Sta/Elev= 28
       0  345.48   10.89  346.08   13.33  346.15   19.07  345.57   22.36   343.9
    25.6  341.69   28.57  341.53   36.77  340.51   57.75  340.26   58.86  340.35
   67.39  339.84    67.4  337.35   76.27  337.37   76.28  339.16   76.36  339.17
   90.51  339.98   96.45  340.17  106.54  340.23  117.37  339.88  121.19  339.61
  137.99   340.9  151.71  341.32  181.95  341.29  186.38  341.17  197.12  341.09
  212.17  341.14   218.2  341.05  224.37  341.08
#Mann= 3 , 0 , 0
       0      .1       0   67.39    .035       0   76.36     .08       0
#XS Ineff= 2 , 0
                          119.08          342.76
Permanent Ineff=
       F       F
#Block Obstruct= 3 ,-1
  123.19  130.76343.0505  181.09   189.9344.2119   37.64   50.42343.4244
Bank Sta=67.39,76.36
XS Rating Curve= 0 ,0
Exp/Cntr=0.3,0.1

Type RM Length L Ch R = 1 ,15810.7 ,23.98,23.78,23.78
XS GIS Cut Line= 4
-611147.12029999   -1045960.8525-611163.70899999   -1045907.1587
-611169.66209999   -1045887.9764    -611188.3553   -1045742.9866
#Sta/Elev= 29
       0  345.46    6.47  345.37   10.74  343.06   11.78  342.35   13.26  341.49
   16.26  341.38   17.47  341.17   24.31  340.93   29.01  340.19    41.3  340.12
   43.17  340.04   57.56  340.02   60.31  337.52   60.32  337.35   68.62  337.49
   68.63  339.39   71.01  339.18   72.44  339.17   72.96     339   89.18  339.66
    92.7  339.69  104.49  340.31  119.55  340.35  149.92  340.86   172.8  341.05
   180.1  341.04  186.59  340.86  194.88  340.88  222.47  341.17
#Mann= 3 , 0 , 0
       0      .1       0   57.56     .04       0   68.63     .08       0
#XS Ineff= 2 ,-1
   68.59   84.79  339.38  111.43  222.47  342.12
Permanent Ineff=
       T       T
#Block Obstruct= 1 ,-1
   191.2  211.22343.9536
Bank Sta=57.56,68.63
XS Rating Curve= 0 ,0
Exp/Cntr=0.3,0.1

Type RM Length L Ch R = 1 ,15786.92,22.11,20.36,18.99
XS GIS Cut Line= 4
     -611165.032   -1045987.8568    -611187.5216   -1045911.1275
-611192.15179999    -1045894.591    -611251.6831   -1045628.0227
#Sta/Elev= 27
       0  345.36    8.56  345.43   19.87   345.4   22.95  345.28   25.17  344.47
   29.12  342.87   33.82   340.6   39.46  340.31   54.42  340.24   61.97  339.98
   81.93  339.84   81.94  337.46   90.61  337.48   90.62  339.36   99.95  338.39
  106.03  338.63  125.74  340.02  178.62  340.35  194.02  340.33  237.09  340.58
  250.73  340.58  260.41  340.42  274.87   340.4  325.38  340.72  332.41   340.7
  363.26  340.99  370.26  341.42
#Mann= 3 , 0 , 0
       0      .1       0   81.93    .035       0   90.62     .08       0
Levee=0,,,-1,239.72,340.57,,
#XS Ineff= 2 ,-1
   90.71  120.11  339.35  179.68  370.26  343.15
Permanent Ineff=
       T       T
#Block Obstruct= 8 ,-1
   56.21    66.3343.0709  221.93  229.93343.4889  329.69  336.18343.7225
  312.31  324.45343.6595     299  303.61343.5717       0     .15348.3615
  178.74  183.69343.3546  204.71  211.66343.3929
Bank Sta=81.93,90.62
XS Rating Curve= 0 ,0
Exp/Cntr=0.3,0.1

Type RM Length L Ch R = 1 ,15766.56,12.99,11.81,8.6
XS GIS Cut Line= 5
-611198.10489999   -1045995.1328-611208.68829999   -1045916.4191
    -611210.0111   -1045897.2368    -611247.7144   -1045771.5595
-611252.34459999   -1045645.8821
#Sta/Elev= 30
       0  344.83    2.84  345.15    3.15   345.8    3.42  345.82   21.89  346.21
   24.06  345.63    26.3  345.47   32.53  344.76   37.32  340.54   43.57  339.89
   50.72  339.54   76.73  339.67   82.87  339.84   82.88  337.33   91.93  337.81
   92.22  339.34   92.26  339.34  112.46  339.56  124.16  339.45     136  339.78
  169.11  340.19  201.46  340.33  216.15   340.3  230.96  340.44  276.32  340.24
  290.78  340.53  322.52   340.7  334.03  340.66  335.86  340.75  355.62  340.91
#Mann= 3 , 0 , 0
       0      .1       0   82.87    .035       0   92.26     .08       0
Levee=0,,,-1,230.94,340.44,,
#XS Ineff= 2 , 0
                          175.29          343.61
Permanent Ineff=
       F       F
#Block Obstruct= 3 ,-1
    8.41   21.34349.0717   43.63   66.65 342.743  136.06  154.41342.9142
Bank Sta=82.87,92.26
XS Rating Curve= 0 ,0
Exp/Cntr=0.3,0.1

Type RM Length L Ch R = 1 ,15754.75,11.28,11.29,11.04
XS GIS Cut Line= 6
     -611230.918   -1045995.6999    -611231.2355   -1045970.9348
    -611221.0212    -1045885.914    -611257.3088   -1045780.7867
    -611261.6351    -1045742.032    -611258.0872   -1045598.3207
#Sta/Elev= 30
       0  344.87   28.12  343.58   33.36  341.38   45.38  340.31    62.5  339.97
    79.6   339.9   81.88  340.08   84.19  339.85   84.22  338.74   84.29  337.54
    84.3  337.05   93.74  337.88   93.75  337.89   93.83  339.24   94.91  339.25
   96.15  339.68   96.21  340.01  108.01  339.48  115.83  339.44  208.71  340.26
  253.27  340.34  257.54  340.13  268.64  340.01  269.15  340.38  275.01  340.42
   275.6  340.29  355.89  341.29  359.79  341.58  379.77  342.25  404.72  343.65
#Mann= 3 , 0 , 0
       0      .1       0   84.19    .035       0   96.15     .08       0
#XS Ineff= 2 , 0
                          172.92          343.25
Permanent Ineff=
       F       F
#Block Obstruct= 1 ,-1
    8.14   22.52347.1254
Bank Sta=84.19,96.15
XS Rating Curve= 0 ,0
Exp/Cntr=0.5,0.3

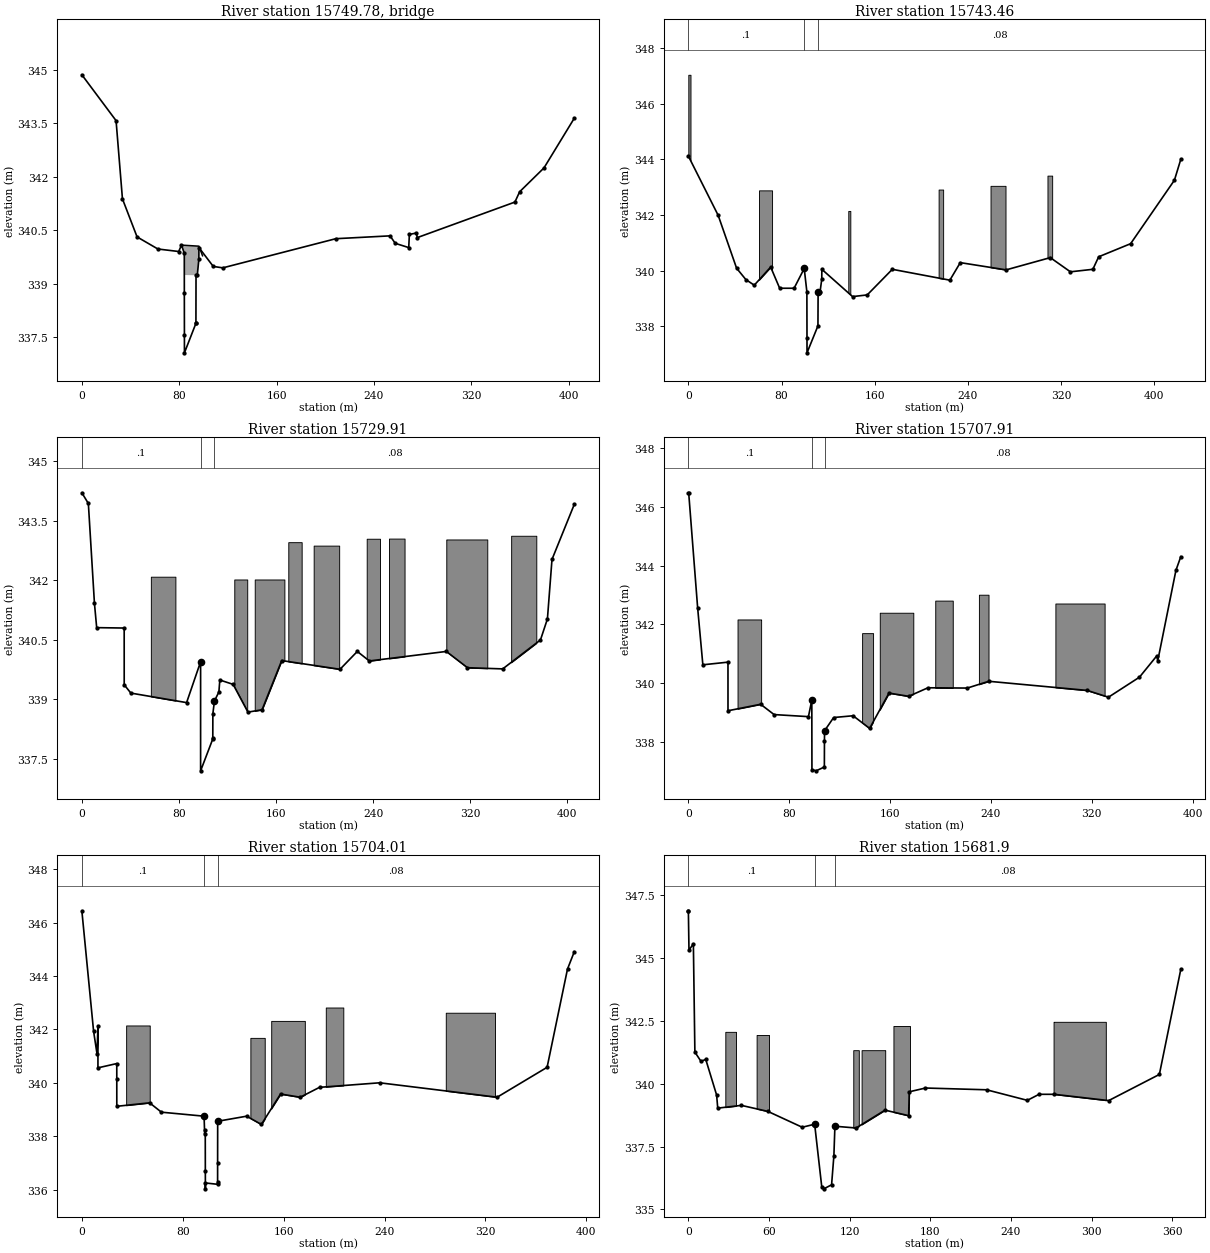
Type RM Length L Ch R = 3 ,15749.78,,,
Bridge Culvert--1,0,-1,-1, 0
Deck Dist Width WeirC Skew NumUp NumDn MinLoCord MaxHiCord MaxSubmerge Is_Ogee
0.5,10.4,1.4,0, 3, 2, , , 0.98, 0, 0,0,,
   81.88   96.21   99.18
  340.08  340.05  339.78
  339.24  339.23  339.78
   99.48   114.6
  340.08  340.05
  339.24  339.23
BR Coef=-1 , 0 , 0 ,, 0 ,,,0.8,0,,0,
WSPro=,,,, 1 ,,,, 0 ,,,, 0 ,,,,-1 ,-1 ,-1 , 0 , 0 , 0 , 0 , 0
BC Design=,, 0 ,, 0 ,,,,,,
BC Use User HTab Curves=0
BC User HTab FreeFlow(D)= 0

Type RM Length L Ch R = 1 ,15743.46,14.98,13.54,10.62
XS GIS Cut Line= 6
    -611270.7595   -1046004.5644    -611232.9684    -1045916.367
-611231.32099999   -1045898.0854-611268.45829999   -1045778.8404
    -611272.7846   -1045740.0857    -611269.2368   -1045596.3744
#Sta/Elev= 30
       0  344.12   25.61  341.99   41.43  340.09   49.41  339.68    56.6  339.48
   70.68  340.13   78.41  339.37   90.78  339.37   99.48  340.08  101.76  339.24
  101.86  337.58  101.87  337.05  111.26  338.02   111.4  339.23  113.07  339.24
  114.55   339.7   114.6  340.05  140.98  339.07  153.54  339.13  175.09  340.05
  224.48  339.66  233.43  340.29  272.77  340.03  310.69  340.47  327.95  339.96
  347.21  340.05  352.21   340.5  379.62  340.97  417.22  343.25  422.69     344
#Mann= 3 , 0 , 0
       0      .1       0   99.48    .035       0   111.4     .08       0
#Block Obstruct= 6 ,-1
   137.3  139.05342.1466  214.83  218.71342.9147   60.66   71.88342.8853
  308.26  312.29343.4149  259.38  272.25 343.048       0    1.87347.0369
Bank Sta=99.48,111.4
XS Rating Curve= 0 ,0
Exp/Cntr=0.5,0.3

Type RM Length L Ch R = 1 ,15729.91,23.06,22.01,19.38
XS GIS Cut Line= 6
    -611281.7885   -1046000.8759-611247.89779999   -1045913.8258
    -611243.0385   -1045896.2879    -611241.4543   -1045878.3214
    -611273.2296   -1045770.2109    -611285.8491   -1045607.2642
#Sta/Elev= 30
       0   344.2    5.36  343.93   10.38  341.41   12.22   340.8   34.88  340.79
    34.9  339.36   40.38  339.15    86.3  338.91   97.84  339.94   97.85  337.19
  107.83  337.99  107.89  338.03  107.94  338.63  109.25  338.95  112.92  339.18
  113.68  339.48  124.63  339.37  136.84  338.67  148.48  338.73  164.67  339.97
  212.71  339.75  226.96   340.2  236.88  339.96   300.3   340.2  317.72  339.79
  346.77  339.76  377.88  340.49   383.6  341.02  387.37  342.52  405.77  343.91
#Mann= 3 , 0 , 0
       0      .1       0   97.84    .035       0  109.25     .08       0
#Block Obstruct= 9 ,-1
  125.59  136.26342.0143  142.44  166.88342.0143     191  212.02 342.868
   56.85   77.08342.0844  300.27  334.05343.0232  253.06  265.89343.0455
  353.72  374.44343.1166  170.09  181.11342.9549   234.7  245.66343.0414
Bank Sta=97.84,109.25
XS Rating Curve= 0 ,0
Exp/Cntr=0.3,0.1

Type RM Length L Ch R = 1 ,15707.91,3.89,3.89,3.9
XS GIS Cut Line= 6
    -611297.0154   -1045997.0692-611269.98739999   -1045907.1252
    -611262.9829    -1045890.143    -611257.7215   -1045872.5269
    -611281.2811   -1045780.8493    -611297.0154   -1045616.4002
#Sta/Elev= 30
       0  346.46     .29  346.47     7.4  342.56   11.53  340.63   31.45  340.72
   31.46  339.07   57.35  339.29   68.02  338.94   95.25  338.87   97.93  339.43
   98.03  337.07   101.3  337.03  107.88  337.16  107.95  338.03  108.02  338.39
  115.25  338.84  130.67   338.9  143.77  338.47  159.13  339.67  174.73  339.56
  190.03  339.85  221.21  339.84  238.26  340.07  316.29  339.76  333.17  339.53
  357.76  340.21  371.62  340.94  372.23  340.76  386.69  343.84  390.53   344.3
#Mann= 3 , 0 , 0
       0      .1       0   97.93    .035       0  108.02     .08       0
#Block Obstruct= 6 ,-1
   39.03   57.74342.1694  291.09  330.12342.7108  195.81   209.7342.8094
  151.82  178.41342.3976  137.81  146.51341.7051  230.44  238.06343.0097
Bank Sta=97.93,108.02
XS Rating Curve= 0 ,0
Exp/Cntr=0.3,0.1

Type RM Length L Ch R = 1 ,15704.01,5.49,5.67,5.52
XS GIS Cut Line= 6
    -611300.6086    -1045995.581    -611273.5806   -1045905.6369
-611266.57609999   -1045888.6548    -611261.3147   -1045871.0387
    -611284.8744   -1045779.3611    -611300.6086    -1045614.912
#Sta/Elev= 30
       0  346.44    9.31  341.93   12.04  341.08   12.75  342.14   12.76  340.56
   27.69  340.72    27.7  340.14   27.71  339.12   53.73  339.25   63.09   338.9
   96.92  338.75   97.39  338.08   97.86  338.22   97.92   336.7   97.97  336.03
   97.99  336.25  107.58   336.2  107.65  336.28  107.66  336.99  107.71  338.56
  130.67  338.75  142.36  338.44  157.56  339.58  173.15  339.46  188.47  339.83
  236.17     340  329.33  339.46  368.94  340.58  385.12  344.26  390.53  344.91
#Mann= 3 , 0 , 0
       0      .1       0   96.92    .035       0  107.71     .08       0
#Block Obstruct= 5 ,-1
   35.12   53.83342.1467  288.59  327.61342.6234  193.44  207.33342.8185
  150.16  176.82342.3174  133.64  145.02341.6818
Bank Sta=96.92,107.71
XS Rating Curve= 0 ,0
Exp/Cntr=0.3,0.1

Type RM Length L Ch R = 1 ,15681.9 ,45.84,50,51.56
XS GIS Cut Line= 4
-611311.56309999   -1045988.0799    -611292.5808   -1045894.7576
-611286.29859999   -1045878.4296-611316.05409999   -1045626.6029
#Sta/Elev= 30
       0  346.88     .04  346.88     .49  345.31    3.76  345.57    4.88  341.26
    9.43  340.89   12.96  340.97   21.06  339.55   21.88  339.03   39.45  339.14
    59.2   338.9   84.71  338.27   93.97  338.39   99.23  335.91  100.76  335.82
  106.56  335.98  108.28  337.14  109.04  338.31  124.79  338.24  146.31  338.95
   163.9  338.73  164.34  339.68  176.38  339.83   221.8  339.76  252.17  339.34
  260.89  339.58  272.13  339.58  312.67  339.33  350.37  340.37  366.31  344.55
#Mann= 3 , 0 , 0
       0      .1       0   93.97    .035       0  109.04     .08       0
#Block Obstruct= 6 ,-1
   27.52   35.49342.0646    50.8   60.03341.9404  122.69  126.81341.3354
  128.89  146.45341.3354  152.57  164.87342.2979  271.67  310.54342.4639
Bank Sta=93.97,109.04
XS Rating Curve= 0 ,0
Exp/Cntr=0.3,0.1

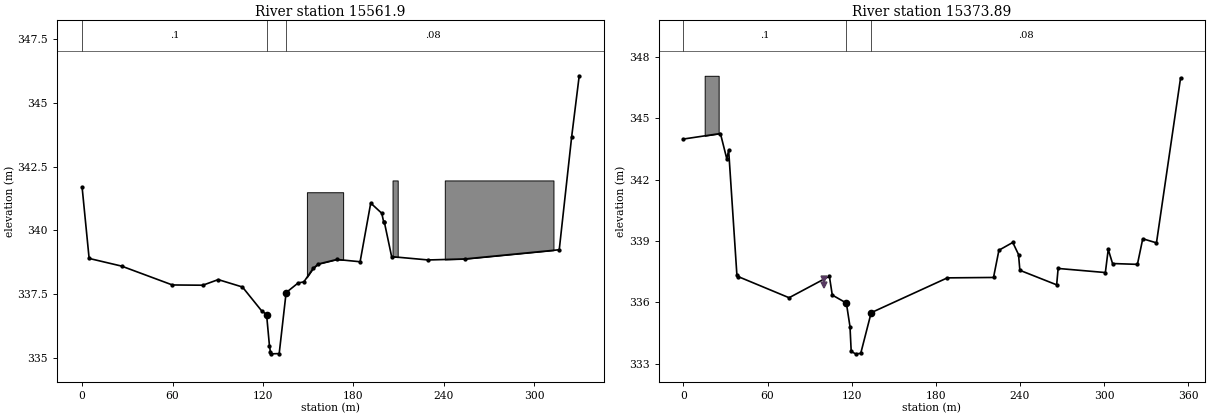
Type RM Length L Ch R = 1 ,15561.9 ,53.46,64.01,67.42
XS GIS Cut Line= 4
    -611358.8707   -1045988.0799    -611405.7524    -1045878.675
    -611406.3202   -1045860.2644    -611458.7895   -1045675.2631
#Sta/Elev= 30
       0   341.7    4.67   338.9   26.16   338.6   59.88  337.86   80.08  337.85
   90.31  338.07  106.36  337.78  119.03  336.85  122.37   336.7  124.27  335.48
  124.95  335.22  125.54  335.16  130.74  335.17  135.33  337.56  143.34  337.94
  147.09  337.98  153.27  338.51  156.65  338.68  168.99  338.86  184.41  338.77
  191.45  341.07  198.78  340.67  200.07  340.32   200.5  340.32  205.32  338.97
  229.63  338.84  253.98  338.88  316.49  339.24  324.73  343.67  329.74  346.06
#Mann= 3 , 0 , 0
       0      .1       0  122.37     .05       0  135.33     .08       0
#Block Obstruct= 3 ,-1
  205.92  209.34341.9575  240.57  312.66341.9575  149.11  173.16341.4943
Bank Sta=122.37,135.33
XS Rating Curve= 0 ,0
Exp/Cntr=0.3,0.1

Type RM Length L Ch R = 1 ,15373.89,10.94,373.89,55.99
XS GIS Cut Line= 4
    -611518.3532   -1046080.6446    -611558.4674   -1045974.2846
    -611559.0168   -1045956.5783    -611651.2961   -1045753.4009
#Sta/Elev= 30
       0  343.98   26.39  344.25   30.94  343.01   32.25  343.44   38.14  337.33
   39.14  337.26   75.35  336.23  104.09  337.28  106.16  336.36   116.2  335.97
  118.79  334.82  119.65  333.61  122.73  333.49  126.44  333.51   133.9   335.5
  188.19   337.2  221.15  337.22     225  338.55  234.88  338.93  238.98  338.34
  239.94  337.57  266.18  336.86  267.23  337.66  300.91  337.46  302.96  338.59
  306.04   337.9  323.77  337.86  327.58  339.11  337.36  338.91  354.54  346.96
#Mann= 3 , 0 , 0
       0      .1       0   116.2     .05       0   133.9     .08       0
Levee=-1,100.23,336.87,0,,,,
#Block Obstruct= 1 ,-1
   15.15   25.12347.0693
Bank Sta=116.2,133.9
XS Rating Curve= 0 ,0
Exp/Cntr=0.3,0.1
LCMann Table=0